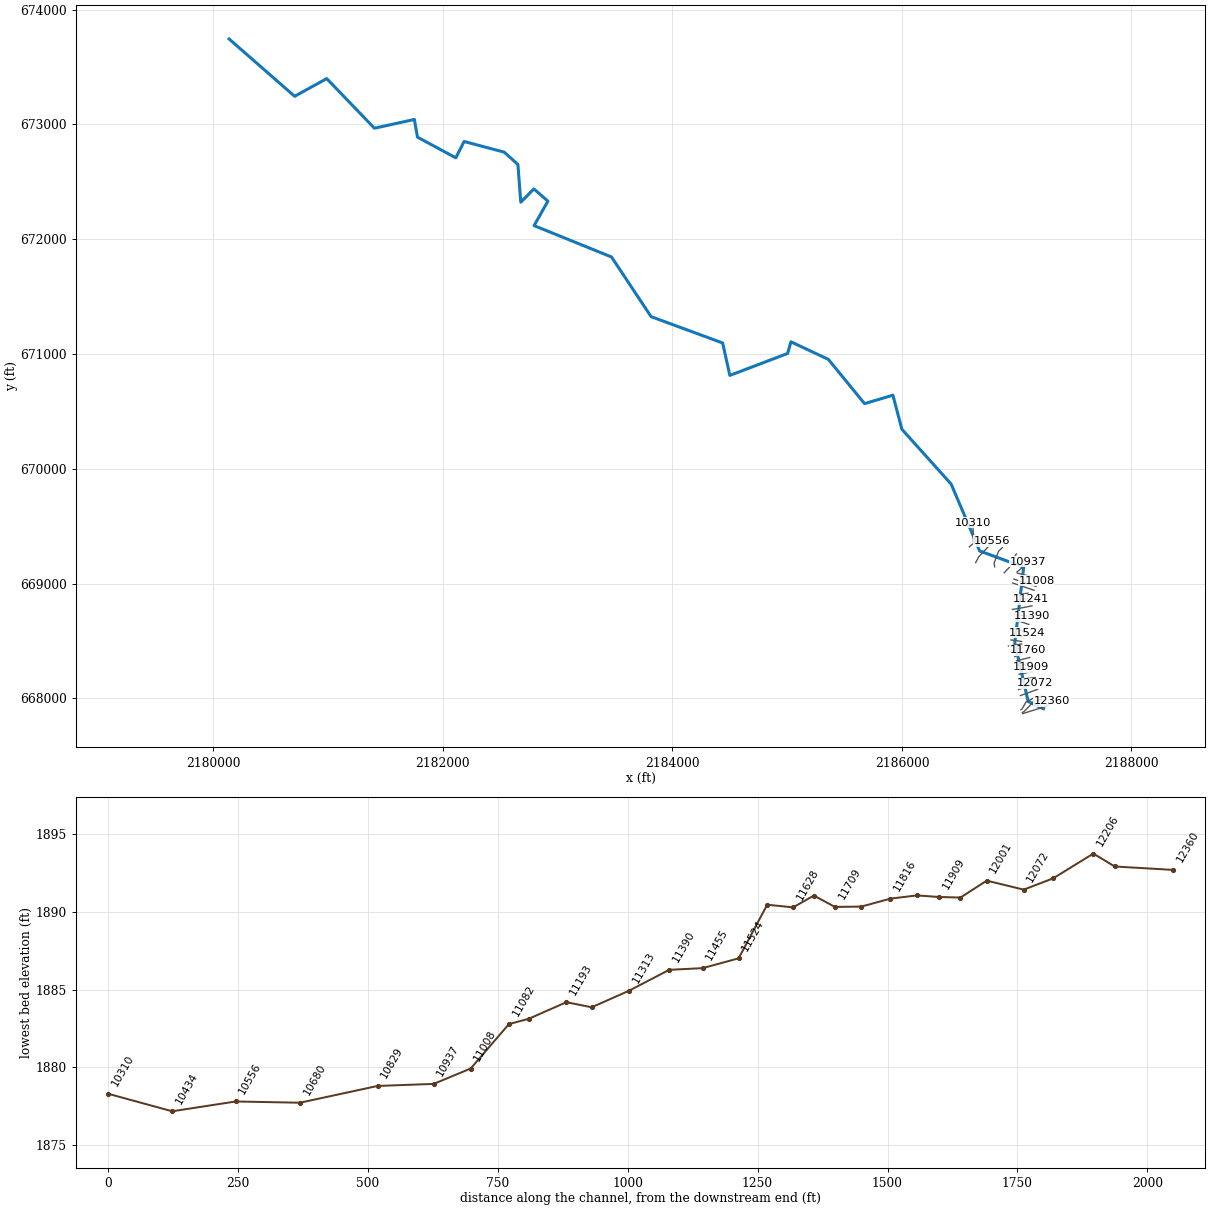
--- QUEENSFK.prj (project) ---

Proj Title=QUEENSFK
Current Plan=p01
Default Exp/Contr=0,0
English Units
Geom File=g01
Flow File=f01
Plan File=p01
BEGIN DESCRIPTION:
---------- MODELED AS PART OF WVEMD CTP PROGRAM, 2023----------
Stream Name: Queens Fork
Flood Zone:  AFH
Upshur County, WV
HEC-RAS Version: RAS 6.3
Vertical Datum: NAVD88
Projection: NAD 1983 StatePlane West Virginia S FIPS 4702 (US Feet)
Terrain: 1-meter LIDAR (FEMA Region III 3DEP collected 2016-2018)
Land Use: 2019 NLCD
Hydrologic Method:
WV SIR2010-5033 regression equations
Additional Model Notes:
None
END DESCRIPTION:
DSS Export Rating Curves= 0
DSS Export Rating Curve Sorted= 0
DSS Export Volume Flow Curves= 0
DXF OffsetX= 0
DXF OffsetY= 0
DXF ScaleX= 0
DXF ScaleY= 0

--- QUEENSFK.p01 (plan) ---

Plan Title=Floodplain
Program Version=6.30
Short Identifier=Floodplain
Geom File=g01
Flow File=f01
Subcritical Flow
K Sum by GR= 0
Std Step Tol= 0.01
Critical Tol= 0.01
Num of Std Step Trials= 20
Max Error Tol= 0.3
Flow Tol Ratio= 0.001
Split Flow NTrial= 30
Split Flow Tol= 0.02
Split Flow Ratio= 0.02
Log Output Level= 0
Friction Slope Method= 1
Unsteady Friction Slope Method= 2
Unsteady Bridges Friction Slope Method= 1
Parabolic Critical Depth
Global Vel Dist= 0 , 0 , 0
Global Log Level= 0
CheckData=False
Encroach Param=-1 ,0,0, 0
Mapping Interval=1HOUR
Computation Time Step Use Courant=        0
Computation Time Step Use Time Series=    0
Computation Time Step Count To Double=0
Computation Time Step Max Doubling=0
Computation Time Step Max Halving=0
Computation Time Step Residence Courant=0
Run HTab= 0
Run UNet= 0
Run Sediment= 0
Run PostProcess= 0
Run WQNet= 0
Run RASMapper=-1
UNET Theta= 0
UNET Theta Warmup= 0
UNET ZTol= 0
UNET ZSATol= 0
UNET MxIter= 0
UNET Max Iter WO Improvement= 0
UNET MaxInSteps= 0
UNET DtIC= 0
UNET DtMin= 0
UNET MaxCRTS= 0
UNET WFStab= 0
UNET SFStab= 0
UNET WFX= 1
UNET SFX= 1
UNET Gravity=32.17405
UNET 1D Methodology=Finite Difference
UNET DSS MLevel= 1
UNET Pardiso=0
UNET DZMax Abort= 0
UNET Use Existing IB Tables= 0
UNET Froude Reduction=False
UNET Froude Limit= 0
UNET Froude Power= 0
UNET D1 Cores= 0
UNET WindReference=Eulerian
UNET WindDragFormulation=Hsu (1988)
UNET D2 Coriolis=0
UNET D2 Cores= 0
UNET D2 Theta= 1
UNET D2 Theta Warmup= 1
UNET D2 Z Tol= 0.01
UNET D2 Volume Tol= 0.01
UNET D2 Max Iterations= 20
UNET D2 Equation= 0
UNET D2 RampUpFraction=0.1
UNET D2 TimeSlices= 1
UNET D2 Turbulence Formulation=Non-Conservative (original)
UNET D2 Eddy Viscosity=0.3
UNET D2 Transverse Eddy Viscosity=0.1
UNET D2 Smagorinsky Mixing=0
UNET D2 BCVolumeCheck=0
UNET D2 Cores=0
UNET D2 SolverType=PARDISO (Direct)
UNET D2 Minimum Iterations= 3
UNET D2 Maximum Iterations= 30
UNET D2 Restart Number= 10
UNET D2 Relaxation Coeff=1.3
UNET D2 SOR Precondition Iterations= 10
UNET D2 ILUT Maximum Fill= 8
UNET D2 ILUT Tolerance=1E-08
UNET D2 Convergence Tolerance=0.00001
UNET D1D2 MaxIter= 0
UNET D1D2 ZTol=0.01
UNET D1D2 QTol=0.1
UNET D1D2 MinQTol=1
Write IC File= 0
Write IC File at Fixed DateTime=0
Write IC File at Sim End=0
Echo Input=False
Echo Parameters=False
Echo Output=False
Write Detailed= 0
HDF Write Warmup=0
HDF Write Time Slices=0
HDF Flush=0
HDF Compression= 1
HDF Chunk Size= 1
HDF Spatial Parts= 1
HDF Use Max Rows=0
HDF Fixed Rows= 1
Calibration Method= 0
Calibration Iterations= 20
Calibration Max Change=0.05
Calibration Tolerance=0.2
Calibration Maximum=1.5
Calibration Minimum=0.5
Calibration Optimization Method= 1
WQ AD Non Conservative
WQ ULTIMATE=-1
WQ Max Comp Step=1HOUR
WQ Output Interval=15MIN
WQ Output Selected Increments= 0
WQ Output face flow=0
WQ Output face velocity=0
WQ Output face area=0
WQ Output face dispersion=0
WQ Output cell volume=0
WQ Output cell surface area=0
WQ Output cell continuity=0
WQ Output cumulative cell continuity=0
WQ Output face conc=0
WQ Output face dconc_dx=0
WQ Output face courant=0
WQ Output face peclet=0
WQ Output face adv mass=0
WQ Output face disp mass=0
WQ Output cell mass=0
WQ Output cell source sink temp=0
WQ Output nsm pathways=0
WQ Output nsm derived pathways=0
WQ Create Restart=0
WQ Fixed Restart=0
WQ System Summary=0
WQ Write To DSS=0
Sorting and Armoring Iterations= 10
XS Update Threshold= 0.02
Bed Roughness Predictor= 0
Hydraulics Update Threshold= 0.02
Energy Slope Method= 1
Volume Change Method= 1
Sediment Retention Method= 0
Sediment TS Multiplier= 1
Warm Up Method= 0
XS Weighting Method= 0
Number of US Weighted Cross Sections= 1
Number of DS Weighted Cross Sections= 1
Upstream XS Weight=0
Main XS Weight=1
Downstream XS Weight=0
Number of DS XS's Weighted with US Boundary= 1
Upstream Boundary Weight= 1
Weight of XSs Associated with US Boundary= 0
Number of US XS's Weighted with DS Boundary= 1
Downstream Boundary Weight= 0.5
Weight of XSs Associated with DS Boundary= 0.5
Percentile Method= 0
Sediment Output Level= 3
Mass or Volume Output= 0
Output Increment Type= 1
Profile and TS Output Increment= 1
Transport Output Increment 1
XS Output Flag= 0
XS Output Increment= 10
Read HDF5 Sediment Hotstart= 0
Sediment Hotstart Type= 0
Write Gradation File= 0
Read Gradation Hotstart= 0
Write HDF5 File= 1
Write Binary Output= 1
Write DSS Sediment File= 0
DSS Sediment Output Type= 1
SV Curve= 0
Specific Gage Flag= 0
Subcell Erosion Methods= 0
Subcell Deposition Methods= 0
Advection Scheme= 1
Matrix Solver= 0
Implicit Weighting Factor= 1
Maximum Outer Loop Convergence Iterations= 5
Convergence Maximum Absolute= 0.001
Convergence RMSE= 0.0001
Grain Fractions Max Abs Error= 0.001
Max Subgrid Regions= 1
Max Subgrid Length Scale= 3.402823E+38
Initial Layer Thickness= 3.402823E+38
Min Layer Thickness= 3.402823E+38
Max Layer Thickness= 3.402823E+38
Number of Layers= 5

--- QUEENSFK.f01 (steady flow) ---

Flow Title=Flows
Program Version=6.30
Number of Profiles= 1
Profile Names=01pct
River Rch & RM=QUEENSFK,Main,12360
     470
River Rch & RM=QUEENSFK,Main,7145
     545
River Rch & RM=QUEENSFK,Main,5299
     626
Boundary for River Rch & Prof#=QUEENSFK,Main            , 1
Up Type= 0
Dn Type= 3
Dn Slope=0.02893
DSS Import GetInterval= 0
DSS Import GetPeak= 0
DSS Import FillOption= 0

--- QUEENSFK.g01 (geometry) ---

Geom Title=Geometry
Program Version=6.31

River Reach=QUEENSFK        ,Main
Reach XY= 30
     2187232.849      667909.721     2187099.382      667972.991
     2186982.856      668484.395     2187060.865      669143.802
     2186677.376      669283.822     2186428.614      669866.681
     2185999.311       670344.46     2185921.074      670640.869
     2185674.114      670567.525     2185358.905      670952.873
      2185032.85      671106.171     2185003.804      671004.726
     2184500.356      670813.397     2184437.457      671096.012
     2183814.393      671325.172     2183469.393      671844.903
     2182794.619      672118.333     2182915.294      672331.296
     2182792.644       672437.72      2182678.78      672321.652
     2182653.826      672651.113     2182534.095      672758.195
     2182184.804      672851.141     2182112.805      672708.603
     2181778.766      672888.772     2181751.552      673042.842
     2181403.605      672966.694     2180987.895      673398.916
      2180708.77      673244.702     2180137.215      673743.915

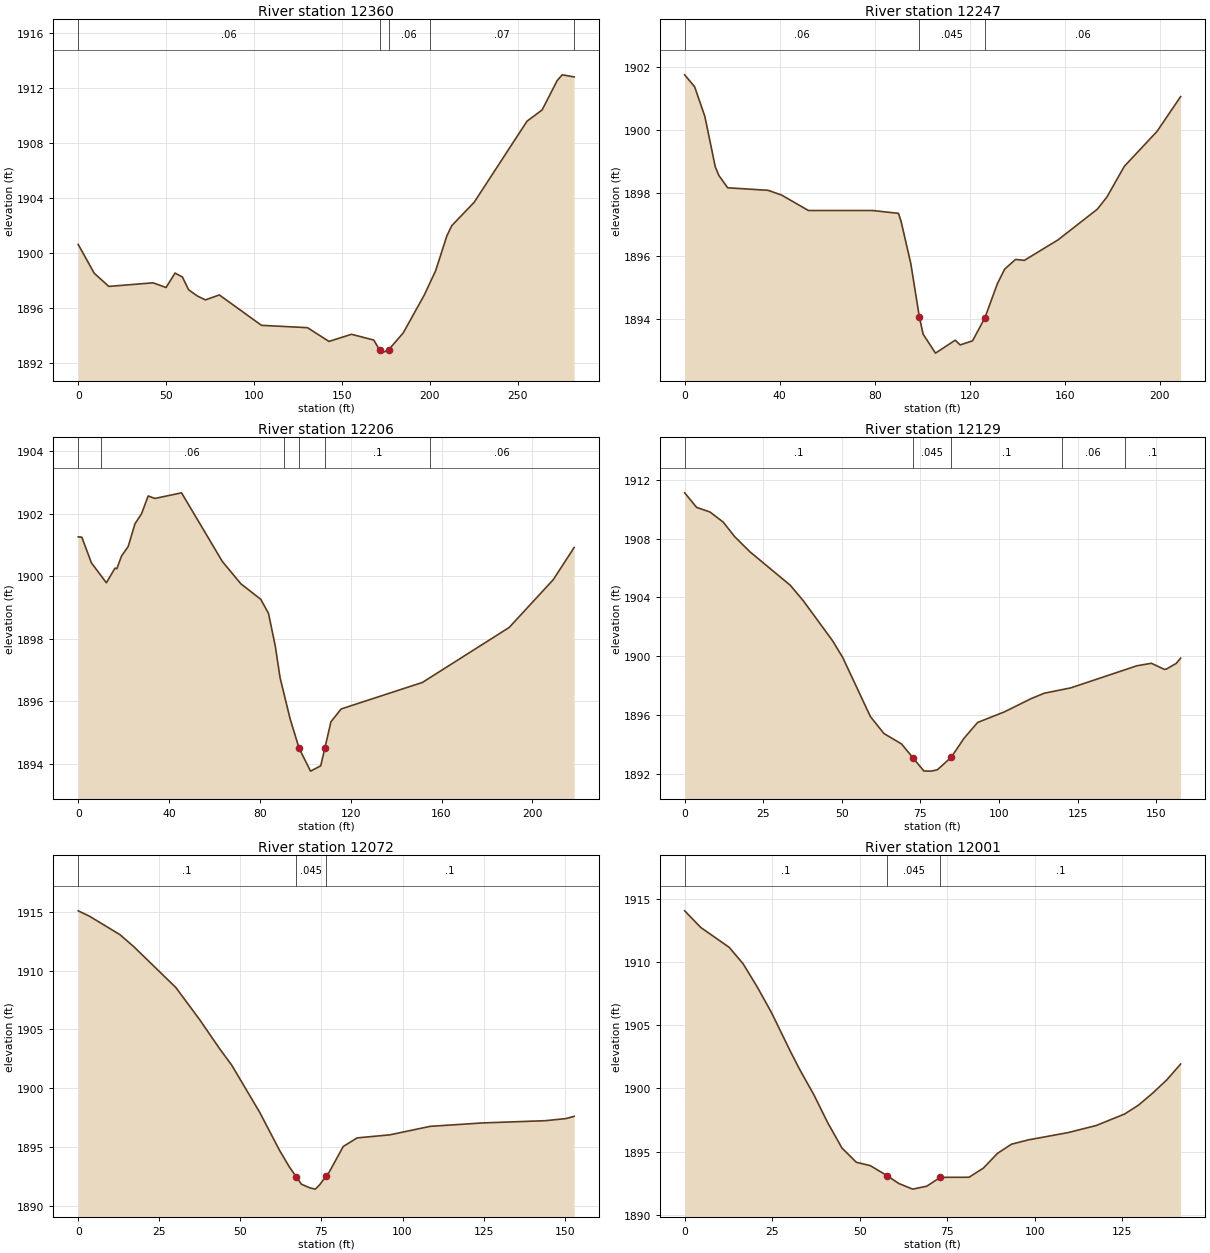
Type RM Length L Ch R = 1 ,12360   ,113,113,113
XS GIS Cut Line= 3
2187051.51272357667867.2532628862187251.58134516667929.415576122
2187309.56467936667973.294856053
#Sta/Elev= 30
       0 1900.61     9.1 1898.52    17.4 1897.56    42.6 1897.82      50 1897.48
    55.1 1898.53    59.3 1898.24    62.8 1897.32    67.7 1896.87    72.4 1896.58
    80.3 1896.94   104.3 1894.73   130.5 1894.56   142.7 1893.56   155.5 1894.08
   168.2 1893.66   171.61892.918   172.4 1892.71   176.6 1892.94     185 1894.19
     197 1896.95   203.4  1898.7   209.8 1901.24   212.6 1901.98   225.3 1903.67
   255.4 1909.57     264 1910.39   272.6 1912.53   275.4 1912.94   282.2 1912.79
#Mann= 5 ,-1,0
       0     .06       0   171.6    .045       0   176.6     .06       0
     200     .07       0  282.22     .06       0
Bank Sta=171.6,176.6
XS Rating Curve= 0 ,0
Exp/Cntr(USF)=0,0
Exp/Cntr=0.3,0.1

Type RM Length L Ch R = 1 ,12247   ,43.8,41.1,38
XS GIS Cut Line= 6
2187048.25913477667877.8272996262187061.59991044  667883.2660712
 2187111.4007574667933.4286978352187143.11962494667971.541944407
2187166.13546782667980.2362946312187214.34880217667991.402389767
#Sta/Elev= 30
       0 1901.75     4.2 1901.37     8.5 1900.43    12.9 1898.83    14.4 1898.56
    18.1 1898.17    35.1 1898.09    40.8 1897.94    52.1 1897.45    79.1 1897.45
      90 1897.36    91.1 1897.11    95.2 1895.77    98.8 1894.08   100.4 1893.53
   105.6 1892.93   113.9 1893.34     116 1893.19   121.2 1893.32   126.4 1894.05
   131.6 1895.12   134.7 1895.59   139.3  1895.9     143 1895.87   157.2 1896.52
   173.7 1897.49   177.8 1897.88   185.1 1898.85   198.9 1899.96   208.8 1901.06
#Mann= 3 ,-1,0
       0     .06       0    98.8    .045       0   126.4     .06       0
Bank Sta=98.8,126.4
XS Rating Curve= 0 ,0
Exp/Cntr(USF)=0,0
Exp/Cntr=0.3,0.1

Type RM Length L Ch R = 1 ,12206   ,76.5,77.2,73.8
XS GIS Cut Line= 6
2187037.07295749 667902.038808252187046.35911595667908.001131117
2187080.50518432667968.4207056172187094.55566991667975.042542826
2187153.25000022668006.4246105742187208.35830207668015.542881655
#Sta/Elev= 30
       0 1901.26     1.6 1901.25     5.8 1900.43    12.4 1899.79    16.2 1900.26
      17 1900.24    19.1 1900.65      22 1900.95      25 1901.68    27.9    1902
    30.8 1902.57    33.8 1902.49    45.5 1902.67    63.5 1900.47    71.6 1899.76
    80.4 1899.26    83.8 1898.81    86.8 1897.76    88.9 1896.75    93.3 1895.44
    97.31894.487   102.3 1893.76   106.8 1893.93   108.61894.494   111.3 1895.34
   115.8 1895.75   151.6  1896.6   189.8 1898.36   209.2 1899.89   218.4 1900.92
#Mann= 6 ,-1,0
       0      .1       0      10     .06       0   90.44      .1       0
    97.3    .045       0   108.6      .1       0  154.92     .06       0
Bank Sta=97.3,108.6
XS Rating Curve= 0 ,0
Exp/Cntr(USF)=0,0
Exp/Cntr=0.3,0.1

Type RM Length L Ch R = 1 ,12129   ,56.5,56.8,57.3
XS GIS Cut Line= 2
2187032.58536136668024.4040877712187180.91332115668078.146102189
#Sta/Elev= 30
       0 1911.11     3.8 1910.12     8.1  1909.8    12.3 1909.11    15.9 1908.13
    20.8 1907.09    33.6 1904.82    37.8 1903.75    47.1 1901.03    50.3  1899.9
    59.1 1895.88    63.4 1894.73      69 1894.02    72.7 1893.06    76.1 1892.18
    78.4 1892.17    80.4 1892.26    84.8 1893.11    88.9 1894.41    93.2 1895.48
   101.7  1896.2   110.2  1897.1   114.4 1897.47   122.9 1897.84   143.9 1899.34
   148.5 1899.51   152.7 1899.09   153.3 1899.12   156.4  1899.5   157.8 1899.86
#Mann= 5 ,-1,0
       0      .1       0    72.7    .045       0    84.8      .1       0
     120     .06       0     140      .1       0
Bank Sta=72.7,84.8
XS Rating Curve= 0 ,0
Exp/Cntr(USF)=0,0
Exp/Cntr=0.3,0.1

Type RM Length L Ch R = 1 ,12072   ,73,71.1,69.3
XS GIS Cut Line= 2
2187016.13297675668076.6990922142187158.56037298668132.431551609
#Sta/Elev= 26
       0 1915.07     3.5 1914.61    12.9 1913.04    17.2 1912.01    30.1 1908.56
    37.5 1905.81    43.6 1903.36    47.3 1901.98    55.9 1897.99    62.1 1894.72
    65.2 1893.28    67.2  1892.5    68.8 1891.86    71.4 1891.55    73.1 1891.44
    74.5 1891.83    76.41892.535    77.4 1892.89    81.7 1895.06      86 1895.79
    96.1 1896.05   108.5 1896.77   124.6 1897.06     144 1897.25   150.4 1897.43
   152.9 1897.62
#Mann= 3 ,-1,0
       0      .1       0    67.2    .045       0    76.4      .1       0
Bank Sta=67.2,76.4
XS Rating Curve= 0 ,0
Exp/Cntr(USF)=0,0
Exp/Cntr=0.3,0.1

Type RM Length L Ch R = 1 ,12001   ,49.8,50.6,51.1
XS GIS Cut Line= 2
2187019.58741666668164.0830109652187160.06379712668181.854119337
#Sta/Elev= 30
       0 1914.07     4.6 1912.75    12.7 1911.18    16.7 1909.87    20.8    1908
    24.8    1906    30.1 1902.98    32.8 1901.52    36.9 1899.49    40.9 1897.25
    44.9 1895.28      49 1894.15      53 1893.88    57.91893.071    61.1 1892.47
    65.1 1892.02    69.1 1892.25      731892.954    81.2 1892.96    85.3 1893.69
    89.3 1894.85    93.3 1895.58    98.1 1895.92   109.5  1896.5   117.5 1897.06
   125.6 1897.97   129.6 1898.68   133.6 1899.62   137.7 1900.69   141.6 1901.93
#Mann= 3 ,-1,0
       0      .1       0    57.9    .045       0      73      .1       0
Bank Sta=57.9,73
XS Rating Curve= 0 ,0
Exp/Cntr(USF)=0,0
Exp/Cntr=0.3,0.1

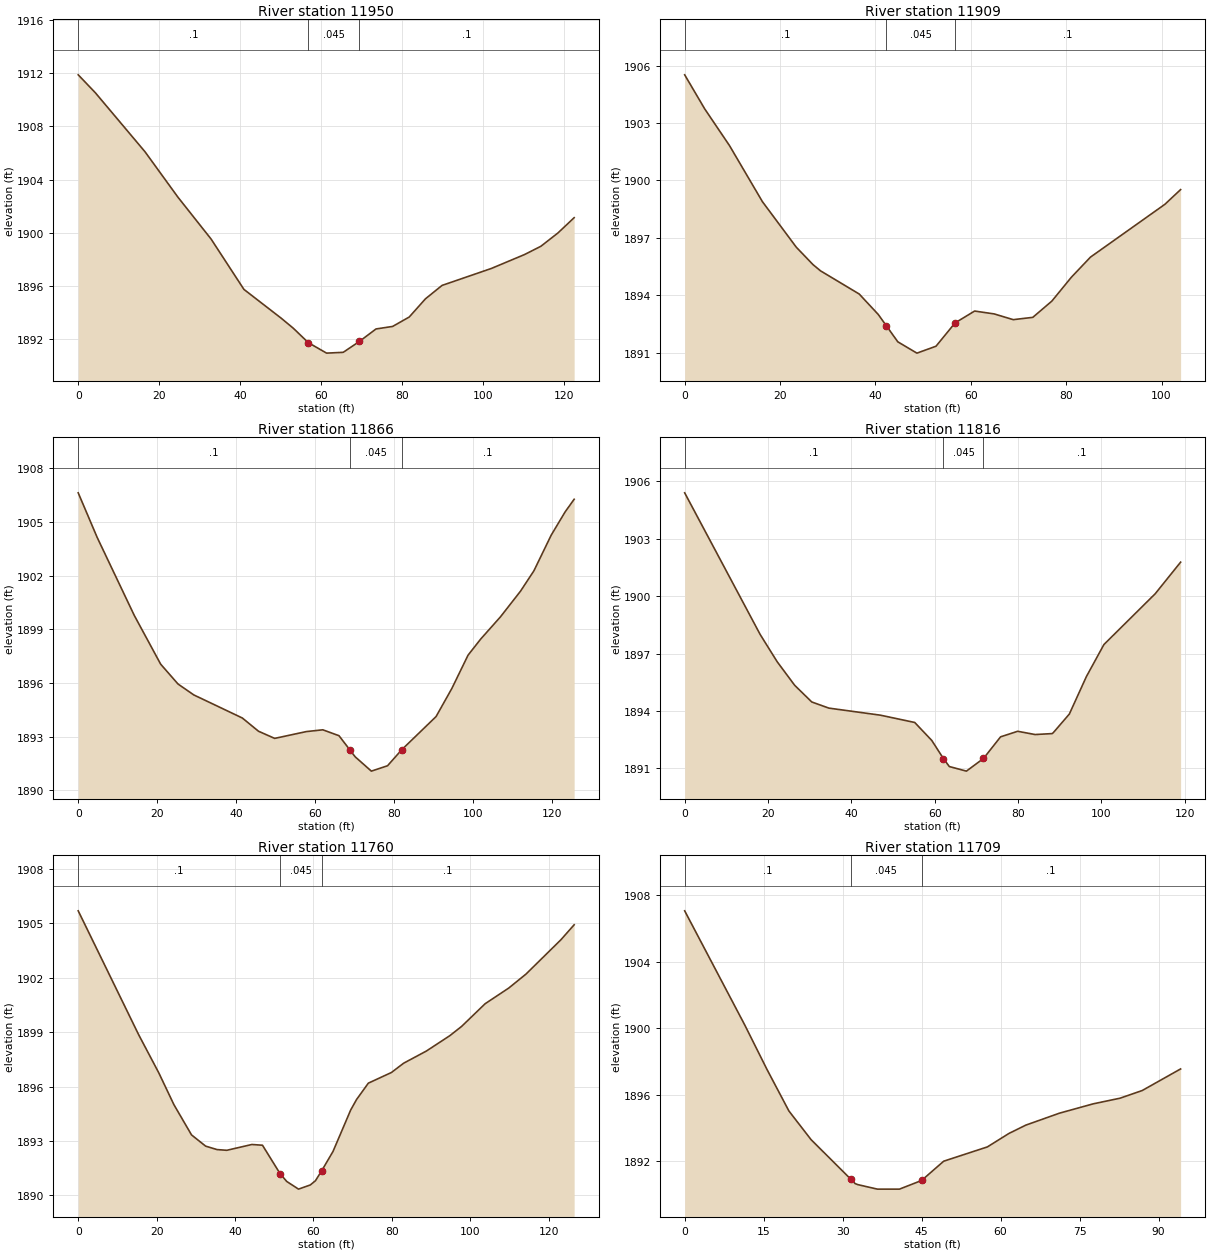
Type RM Length L Ch R = 1 ,11950   ,41.6,41.6,40.8
XS GIS Cut Line= 2
2187020.01053828668210.6263900352187140.17708061 668233.89807957
#Sta/Elev= 22
       0 1911.89     4.2 1910.55    16.5 1906.09    24.6 1902.68    32.8 1899.52
    40.9 1895.73    50.1 1893.56    53.1  1892.8    56.81891.717    61.3 1890.93
    65.4 1890.99    69.4 1891.81    73.5 1892.75    77.6 1892.94    81.7 1893.65
    85.7 1895.02    89.8 1896.03     102 1897.31   110.2 1898.36   114.2 1898.98
   118.4 1899.98   122.4 1901.13
#Mann= 3 ,-1,0
       0      .1       0    56.8    .045       0    69.4      .1       0
Bank Sta=56.8,69.4
XS Rating Curve= 0 ,0
Exp/Cntr(USF)=0,0
Exp/Cntr=0.3,0.1

Type RM Length L Ch R = 1 ,11909   ,41.2,42.4,41.5
XS GIS Cut Line= 2
2187024.03013571668254.6389329652187126.84869129668270.252121035
#Sta/Elev= 23
       0 1905.52     4.2 1903.74     9.4 1901.82    16.3 1898.89    23.4 1896.51
    26.9  1895.6    28.5 1895.27    36.6 1894.06    40.6 1892.99    42.31892.397
    44.7 1891.56    48.7 1890.97    52.7 1891.33    56.71892.549    60.8 1893.17
    64.9 1893.02    68.9 1892.72      73 1892.84      77 1893.69    81.1 1894.94
    85.1 1895.99   100.7 1898.75     104 1899.52
#Mann= 3 ,-1,0
       0      .1       0    42.3    .045       0    56.7      .1       0
Bank Sta=42.3,56.7
XS Rating Curve= 0 ,0
Exp/Cntr(USF)=0,0
Exp/Cntr=0.3,0.1

Type RM Length L Ch R = 1 ,11866   ,49.3,50.9,50.9
XS GIS Cut Line= 2
2187011.46342336668285.1036901752187134.46488059668310.998733803
#Sta/Elev= 27
       0 1906.63     4.8 1904.14    14.2 1899.78    20.9 1897.05    25.3 1895.94
    29.3 1895.33    41.6 1894.04    45.7  1893.3    49.8  1892.9    57.8 1893.28
      62 1893.38    66.1 1893.05    68.81892.273    70.2 1891.87    74.3 1891.07
    78.4 1891.37      821892.266    90.7 1894.12    94.7 1895.69    98.8 1897.55
     102 1898.45     107 1899.69   112.1 1901.13   115.5 1902.27   119.9 1904.27
   123.4 1905.56   125.7 1906.27
#Mann= 3 ,-1,0
       0      .1       0    68.8    .045       0      82      .1       0
Bank Sta=68.8,82
XS Rating Curve= 0 ,0
Exp/Cntr(USF)=0,0
Exp/Cntr=0.3,0.1

Type RM Length L Ch R = 1 ,11816   ,53.7,55.9,58
XS GIS Cut Line= 2
2186998.60037683668327.438866084 2187114.0998876668356.228061647
#Sta/Elev= 23
       0 1905.39    18.1    1898    22.2 1896.57    26.4 1895.34    30.5 1894.47
    34.6 1894.15      47 1893.78    55.2  1893.4    59.3 1892.46    62.1 1891.51
    63.5  1891.1    67.6 1890.86    71.7 1891.52    75.8 1892.65    79.9 1892.94
    84.1 1892.77    88.2 1892.82    88.5 1892.88    92.3 1893.84    96.4  1895.8
   100.6 1897.47   112.9 1900.12     119 1901.77
#Mann= 3 ,-1,0
       0      .1       0    62.1    .045       0    71.7      .1       0
Bank Sta=62.1,71.7
XS Rating Curve= 0 ,0
Exp/Cntr(USF)=0,0
Exp/Cntr=0.3,0.1

Type RM Length L Ch R = 1 ,11760   ,54,50.9,49.2
XS GIS Cut Line= 3
2186982.49213645 668363.082632022187063.71879536668405.238239808
2187095.24981907668420.318294627
#Sta/Elev= 30
       0 1905.69    15.4 1898.87    20.6 1896.74    24.4 1895.01    28.9 1893.34
    32.5 1892.72    35.4 1892.53    37.9 1892.49    44.3 1892.81      47 1892.77
    51.5  1891.2    53.2 1890.77    56.2 1890.35    59.2 1890.58    60.5 1890.81
    62.1 1891.36      65 1892.43    69.5 1894.71      71 1895.29      74 1896.19
    79.9 1896.78      83 1897.29    88.8 1897.96    94.8 1898.81    97.8 1899.32
   103.8 1900.57   109.8 1901.43   114.2  1902.2   123.1 1904.09   126.5 1904.92
#Mann= 3 ,-1,0
       0      .1       0    51.5    .045       0    62.1      .1       0
Bank Sta=51.5,62.1
XS Rating Curve= 0 ,0
Exp/Cntr(USF)=0,0
Exp/Cntr=0.3,0.1

Type RM Length L Ch R = 1 ,11709   ,42.2,40.2,38.5
XS GIS Cut Line= 2
2186961.28162385668414.7884606112187051.12967324668442.996569138
#Sta/Elev= 20
       0 1907.07    11.4 1900.21    15.6 1897.55    19.8 1895.03      24 1893.31
    31.61890.912    32.4 1890.66    32.9  1890.6    36.6 1890.33    40.8 1890.33
      45 1890.85    49.2 1892.01    57.5 1892.87    61.6 1893.68    64.8 1894.18
    71.2  1894.9    77.6 1895.46    82.7  1895.8    86.9 1896.26    94.2 1897.56
#Mann= 3 ,-1,0
       0      .1       0    31.6    .045       0      45      .1       0
Bank Sta=31.6,45
XS Rating Curve= 0 ,0
Exp/Cntr(USF)=0,0
Exp/Cntr=0.3,0.1

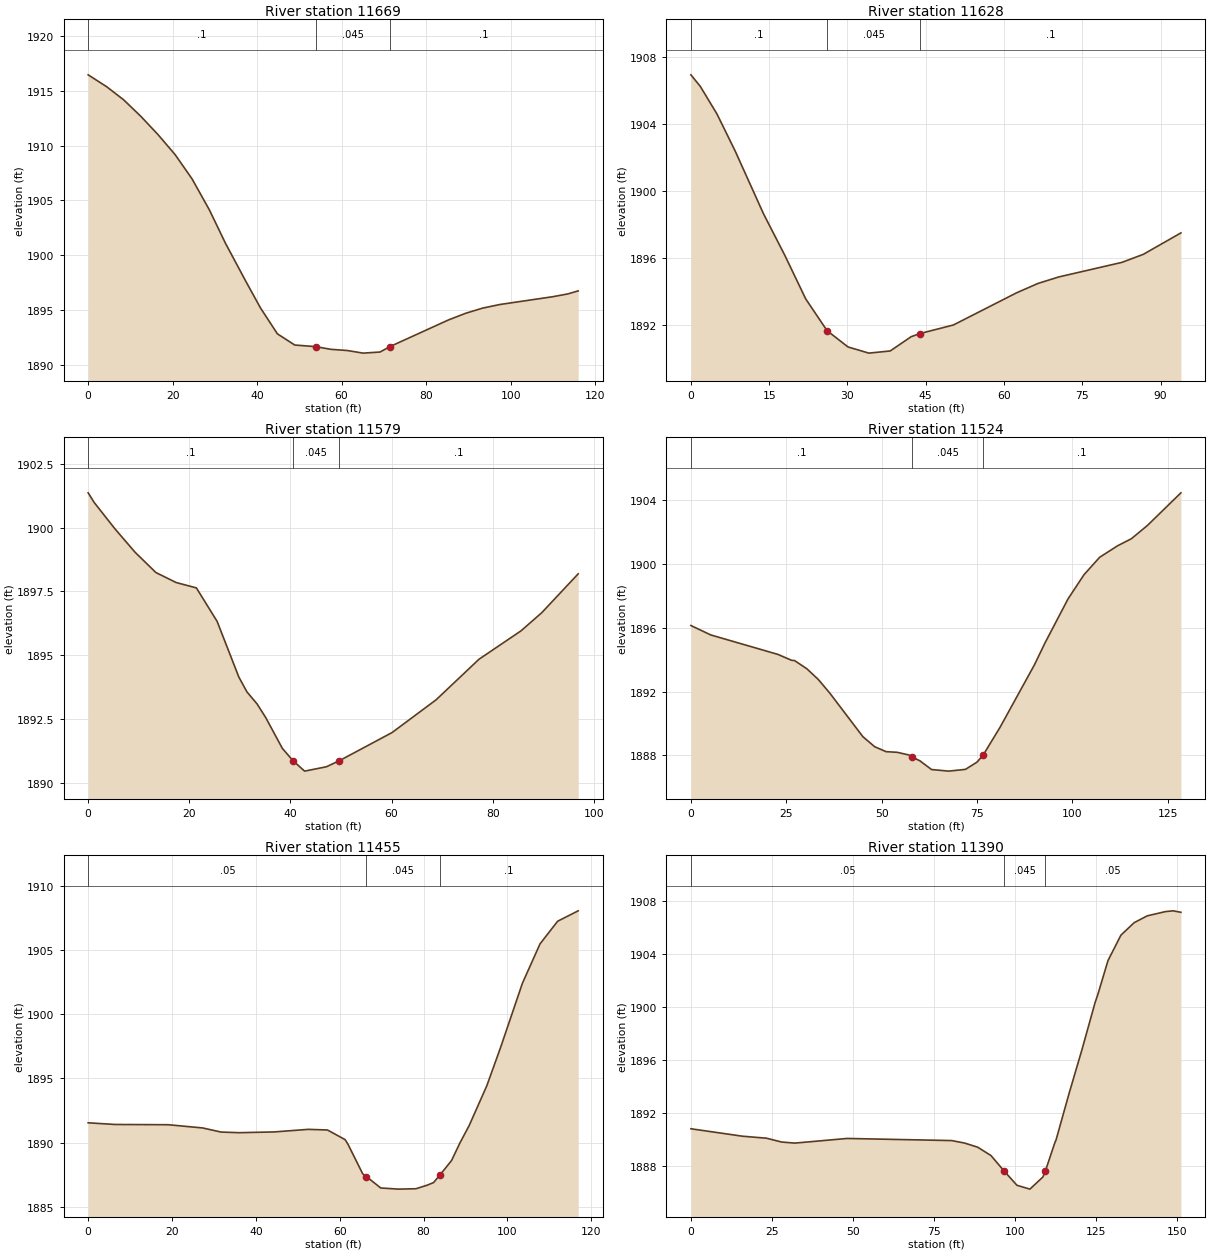
Type RM Length L Ch R = 1 ,11669   ,43.9,40.1,36.1
XS GIS Cut Line= 2
2186927.84979153668456.0558786422187042.46764272668473.736016387
#Sta/Elev= 26
       0 1916.46     4.4 1915.37     8.4 1914.18    12.5 1912.66    16.5 1911.02
    20.6 1909.17    24.6 1906.96    28.7 1904.13    32.5 1901.09    37.3 1897.63
    40.8 1895.18    44.8 1892.82    48.9  1891.8    53.9 1891.65    57.4 1891.41
    61.3  1891.3    65.1 1891.06    69.1 1891.16    71.4 1891.65    85.3 1894.09
    89.4  1894.7    93.4 1895.17    97.5  1895.5     110 1896.21   113.5 1896.46
     116 1896.74
#Mann= 3 ,-1,0
       0      .1       0    53.9    .045       0    71.4      .1       0
Bank Sta=53.9,71.4
XS Rating Curve= 0 ,0
Exp/Cntr(USF)=0,0
Exp/Cntr=0.3,0.1

Type RM Length L Ch R = 1 ,11628   ,54,49.8,46.5
XS GIS Cut Line= 2
2186950.38689733668509.0326229722187043.30859573668495.697056312
#Sta/Elev= 20
       0 1906.92     1.8 1906.23       5 1904.58     8.5 1902.36    13.9 1898.63
      18 1896.14      22 1893.54    26.1 1891.64    30.1 1890.67    34.1  1890.3
    38.2 1890.43    42.2 1891.28    43.9 1891.47    50.3 1891.98    62.4  1893.9
    66.5 1894.46    70.5 1894.85    82.6 1895.72    86.7  1896.2    93.9 1897.48
#Mann= 3 ,-1,0
       0      .1       0    26.1    .045       0    43.9      .1       0
Bank Sta=26.1,43.9
XS Rating Curve= 0 ,0
Exp/Cntr(USF)=0,0
Exp/Cntr=0.3,0.1

Type RM Length L Ch R = 1 ,11579   ,55.3,55,55
XS GIS Cut Line= 4
2186962.95360968668560.441900763 2186988.8486533668556.633806112
2187032.64174179668538.3549517862187055.10950023668532.262000344
#Sta/Elev= 23
       0 1901.36     1.2 1900.98     5.3 1899.95     9.3 1899.03    13.4 1898.24
    17.4 1897.85    21.4 1897.64    25.5 1896.33    29.8 1894.15    31.4 1893.57
    33.4  1893.1    35.1 1892.57    38.4 1891.36    40.5 1890.88    42.8 1890.47
    47.1 1890.64    49.7 1890.88    60.1 1891.98    68.8 1893.26    77.3 1894.85
    85.6 1895.96    89.7 1896.67    96.9 1898.19
#Mann= 3 ,-1,0
       0      .1       0    40.5    .045       0    49.7      .1       0
Bank Sta=40.5,49.7
XS Rating Curve= 0 ,0
Exp/Cntr(USF)=0,0
Exp/Cntr=0.3,0.1

Type RM Length L Ch R = 1 ,11524   ,67,69.2,71
XS GIS Cut Line= 4
2186975.41850584668603.1270354992186999.47804785668613.922983835
2187062.71145953668581.5351388262187092.63165921668573.206835824
#Sta/Elev= 30
       0 1896.15     5.2 1895.56    22.8 1894.34    26.4 1893.97    27.2 1893.95
    30.4 1893.44    33.4 1892.77    36.4 1891.92    45.1 1889.18    48.2 1888.55
    51.2 1888.24    54.1  1888.2    57.2 1888.03      58 1887.91    60.1 1887.66
    63.1 1887.12    67.6 1887.02      72 1887.13      75 1887.58    76.6 1888.01
    81.1 1889.78    90.1 1893.69    92.8 1895.03    98.9 1897.82   103.1 1899.34
   107.2 1900.43   111.9 1901.15   115.5 1901.59   119.7 1902.42   128.5 1904.47
#Mann= 3 ,-1,0
       0      .1       0      58    .045       0    76.6      .1       0
Bank Sta=58,76.6
XS Rating Curve= 0 ,0
Exp/Cntr(USF)=0,0
Exp/Cntr=0.3,0.1

Type RM Length L Ch R = 1 ,11455   ,62.2,64.4,67.3
XS GIS Cut Line= 2
2186994.12088548668681.7200491742187104.85150585668644.112147824
#Sta/Elev= 28
       0 1891.55     6.4 1891.42    19.1  1891.4    27.3 1891.15    31.7 1890.83
      36 1890.78    44.4 1890.84    52.5 1891.04    57.1 1890.99    61.3 1890.24
      62 1889.87    65.5 1887.58    66.4 1887.36    69.8 1886.48      74 1886.39
    78.2 1886.42    80.9  1886.7    82.4  1886.9      84 1887.52    86.7 1888.62
    88.7 1889.99    90.9 1891.34    95.1 1894.43    98.4 1897.42   103.6 1902.41
   107.8 1905.47     112 1907.23   116.9 1908.04
#Mann= 3 ,-1,0
       0     .05       0    66.4    .045       0      84      .1       0
Bank Sta=66.4,84
XS Rating Curve= 0 ,0
Exp/Cntr(USF)=0,0
Exp/Cntr=0.3,0.1

Type RM Length L Ch R = 1 ,11390   ,74.4,77.6,81.2
XS GIS Cut Line= 4
2186984.42126612668731.7395645882187055.41268056668721.655463383
2187106.82195835668716.5145356042187134.58296836668714.458164493
#Sta/Elev= 28
       0 1890.83    15.9 1890.27    23.3 1890.12      28 1889.83    32.1 1889.75
    48.2  1890.1    80.5 1889.94    84.5 1889.75    88.5 1889.44    92.6 1888.81
    96.6 1887.66   100.6 1886.57   104.6 1886.28   108.6 1887.19   109.4 1887.66
   112.2 1889.71   112.7 1890.01   116.7  1893.5   120.7 1896.82   124.7 1900.33
   125.6 1900.98   128.7 1903.51   132.7 1905.43   136.8 1906.37   140.8 1906.88
   146.4  1907.2   148.8 1907.26   151.2 1907.15
#Mann= 3 ,-1,0
       0     .05       0    96.6    .045       0   109.4     .05       0
Bank Sta=96.6,109.4
XS Rating Curve= 0 ,0
Exp/Cntr(USF)=0,0
Exp/Cntr=0.3,0.1

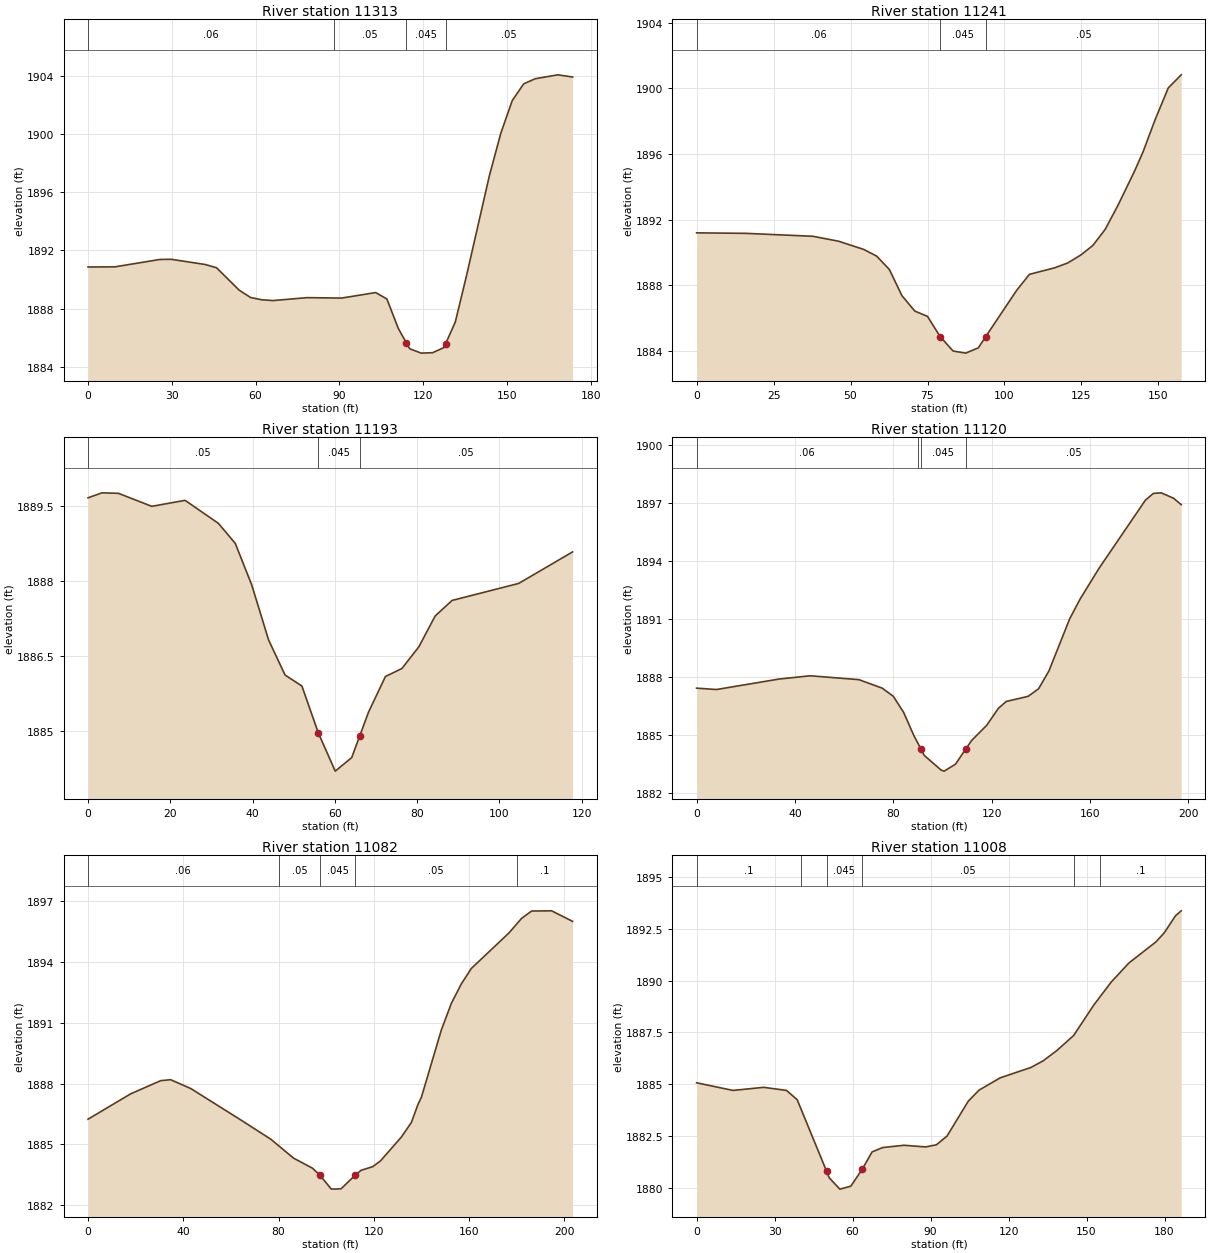
Type RM Length L Ch R = 1 ,11313   ,70.9,71.6,72.2
XS GIS Cut Line= 4
2186962.67375084668775.1500413982187010.27493398 668782.00461177
2187108.52377598668801.0450850262187133.27639122668806.376417538
#Sta/Elev= 30
       0 1890.86     9.6 1890.87    25.8 1891.38    29.8 1891.39      42 1891.03
      46 1890.81    54.1 1889.27    58.2 1888.76    62.3  1888.6    66.3 1888.55
    78.5 1888.75    90.8 1888.72     103  1889.1     107 1888.66   111.1 1886.63
   113.9 1885.66   115.2 1885.23   119.3 1884.93   123.4 1884.96   127.4 1885.31
     1281885.562   131.5 1887.07   135.6 1890.33   143.7 1897.14   147.8 1900.07
   151.9 1902.32     156 1903.47   160.1 1903.82   168.2 1904.09   173.5 1903.94
#Mann= 4 ,-1,0
       0     .06       0   88.09     .05       0   113.9    .045       0
     128     .05       0
Bank Sta=113.9,128
XS Rating Curve= 0 ,0
Exp/Cntr(USF)=0,0
Exp/Cntr=0.3,0.1

Type RM Length L Ch R = 1 ,11241   ,49.6,48.5,47.5
XS GIS Cut Line= 3
2186967.62427389668838.3644126082187088.34087433668869.971598213
 2187120.3288694668863.497837306
#Sta/Elev= 29
       0  1891.2    15.9 1891.17    37.8 1890.99    46.1 1890.69    54.3 1890.19
    58.5 1889.78    62.6 1888.97    66.7 1887.37    70.9 1886.43      75 1886.11
    79.1 1884.88    83.3    1884    87.4 1883.87    91.5 1884.19    93.91884.873
   103.9 1887.68   108.1 1888.67   116.3 1889.07   120.5 1889.36   124.8 1889.85
   128.7 1890.43   132.1 1891.26   132.8 1891.44   136.9 1892.89   142.3 1894.98
     145 1896.13   148.9 1898.08   153.2 1900.03   157.4 1900.83
#Mann= 3 ,-1,0
       0     .06       0    79.1    .045       0    93.9     .05       0
Bank Sta=79.1,93.9
XS Rating Curve= 0 ,0
Exp/Cntr(USF)=0,0
Exp/Cntr=0.3,0.1

Type RM Length L Ch R = 1 ,11193   ,76.3,72.5,68.4
XS GIS Cut Line= 2
2186980.83168133 668897.987076732187097.19012901668916.604428358
#Sta/Elev= 23
       0 1889.66     3.4 1889.76     7.4 1889.75    15.5 1889.49    23.6 1889.61
    31.7 1889.15    35.8 1888.75    39.8 1887.92    43.9 1886.82    47.9 1886.12
      52  1885.9      56 1884.96    60.1  1884.2    64.1 1884.47      661884.892
    68.2 1885.38    72.3 1886.09    76.3 1886.25    80.4 1886.68    84.4  1887.3
    88.5 1887.61   104.7 1887.95   117.8 1888.58
#Mann= 3 ,-1,0
       0     .05       0      56    .045       0      66     .05       0
Bank Sta=56,66
XS Rating Curve= 0 ,0
Exp/Cntr(USF)=0,0
Exp/Cntr=0.3,0.1

Type RM Length L Ch R = 1 ,11120   ,38.9,38.1,37.2
XS GIS Cut Line= 2
2186964.47159056669005.2121554492187151.06822847668941.743911262
#Sta/Elev= 30
       0 1887.42     8.1 1887.35    33.5 1887.89    46.2 1888.06      66 1887.86
    75.5 1887.42      80    1887    84.2 1886.17    88.4 1884.96    91.2 1884.29
    92.6 1883.94    99.5 1883.18   100.7 1883.13   105.3 1883.49   109.5 1884.28
   111.9 1884.72     118  1885.5   122.7 1886.37   125.9 1886.73   134.9    1887
   139.1 1887.39   143.3 1888.31   151.8 1891.02     156 1892.03   163.7 1893.62
   182.6 1897.15   185.8 1897.49     189 1897.52     194 1897.24   197.1 1896.91
#Mann= 4 ,-1,0
       0     .06       0      90     .05       0    91.2    .045       0
   109.5     .05       0
Bank Sta=91.2,109.5
XS Rating Curve= 0 ,0
Exp/Cntr(USF)=0,0
Exp/Cntr=0.3,0.1

Type RM Length L Ch R = 1 ,11082   ,71.9,73.6,74.3
XS GIS Cut Line= 2
2186975.17395136669039.1261248972187168.53392863668975.643628328
#Sta/Elev= 30
       0 1886.24    17.9 1887.49    30.5 1888.14    34.7 1888.19    43.2 1887.75
    64.2  1886.2    76.8 1885.25    86.3 1884.32    94.3 1883.82    97.51883.465
   102.1  1882.8   103.8 1882.79   106.3 1882.81   112.3 1883.49   114.7 1883.72
   119.6  1883.9   122.8 1884.18   131.6 1885.36   135.8 1886.08   138.6 1886.98
     140 1887.32   148.4 1890.65   152.6 1891.96   156.8 1892.92     161 1893.68
   176.7 1895.42   182.1 1896.15   186.3 1896.51   194.7 1896.52   203.5    1896
#Mann= 5 ,-1,0
       0     .06       0      80     .05       0    97.5    .045       0
   112.3     .05       0     180      .1       0
Bank Sta=97.5,112.3
XS Rating Curve= 0 ,0
Exp/Cntr(USF)=0,0
Exp/Cntr=0.3,0.1

Type RM Length L Ch R = 1 ,11008   ,60.5,71.3,84
XS GIS Cut Line= 3
2187006.55970338669090.6555527162187147.60024602669056.805822482
2187172.04727341669023.426227392
#Sta/Elev= 30
       0 1885.07      14  1884.7    25.8 1884.85    34.6  1884.7    38.7 1884.25
      501880.794      51 1880.48    55.1 1879.93    59.3 1880.07    63.71880.886
    67.5 1881.73    71.6 1881.94    79.8 1882.05      88 1881.97    92.2 1882.07
    96.3 1882.49   104.5 1884.18   108.6 1884.71   116.8 1885.31   128.6 1885.81
   133.3 1886.13   138.6 1886.63     145 1887.35   152.8 1888.83   159.5 1889.94
   166.3 1890.86   176.7 1891.88   179.9 1892.32   184.2 1893.14   186.4 1893.38
#Mann= 6 ,-1,0
       0      .1       0      40     .05       0      50    .045       0
    63.7     .05       0  145.05     .06       0  155.05      .1       0
Bank Sta=50,63.7
XS Rating Curve= 0 ,0
Exp/Cntr(USF)=0,0
Exp/Cntr=0.3,0.1

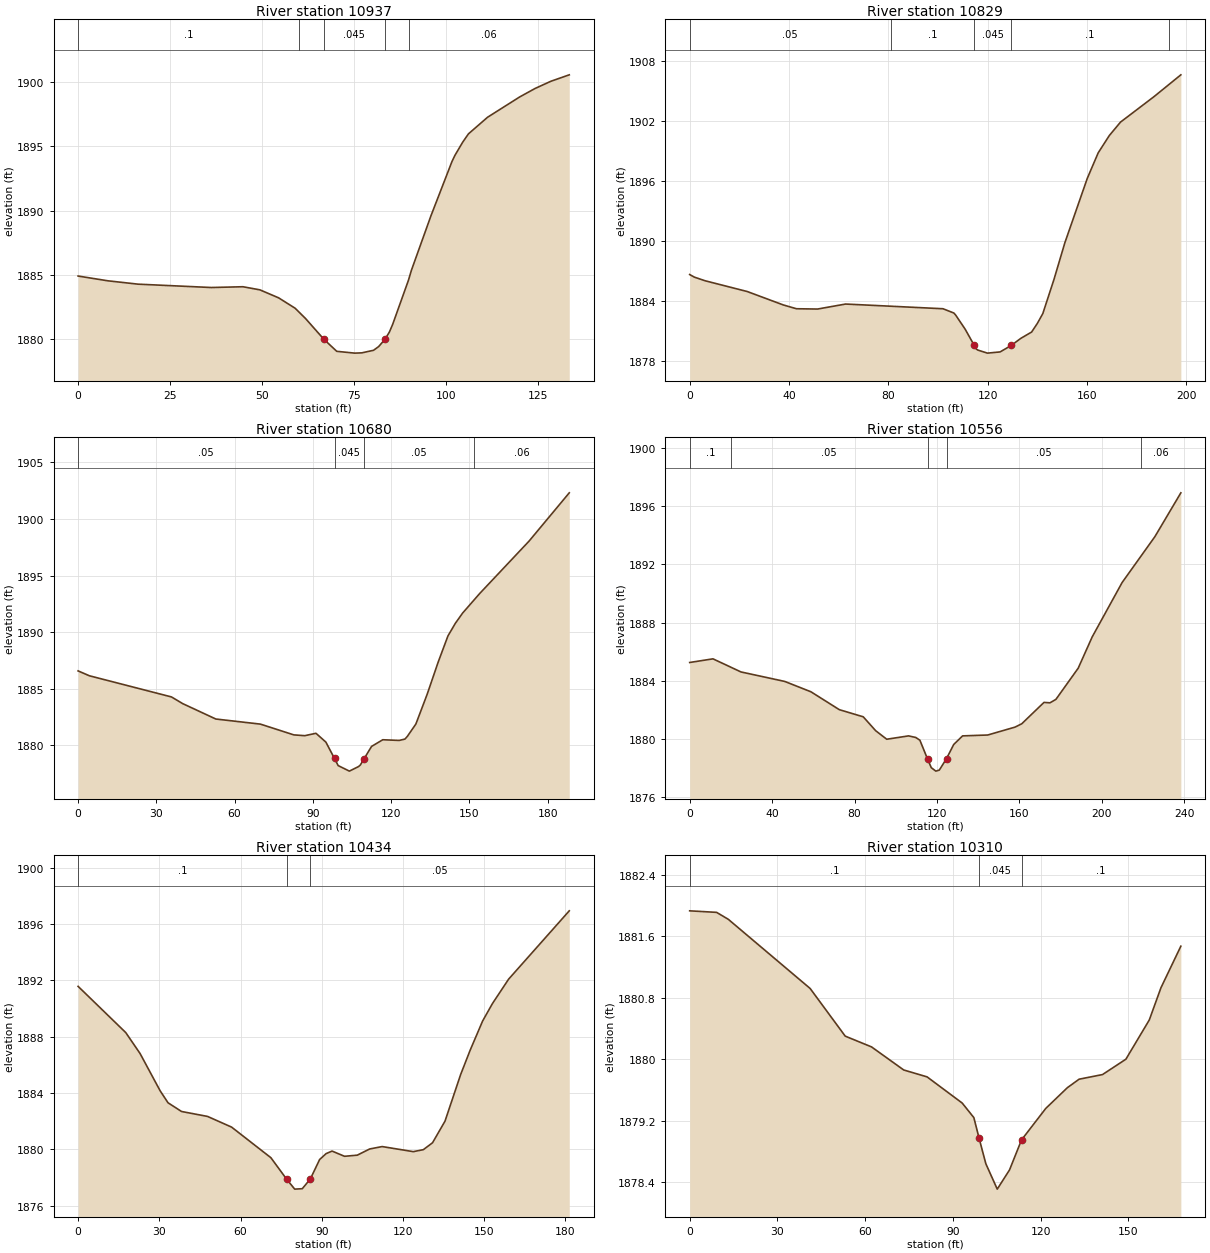
Type RM Length L Ch R = 1 ,10937   ,102.4,107.7,113.8
XS GIS Cut Line= 3
2187001.85835196  669100.52839072187092.59443439669174.339608014
 2187098.2360561669189.854067704
#Sta/Elev= 30
       0 1884.92     8.1 1884.55    16.3 1884.29    36.2 1884.03    44.8 1884.09
    49.4 1883.85    54.5 1883.23      59 1882.42    61.8 1881.63    66.81880.016
    70.3 1879.08    75.2 1878.94    77.1 1878.96    80.3 1879.16    81.7 1879.45
    83.4 1880.01    84.6 1880.57    85.5 1881.17    89.8  1884.6    90.6 1885.37
    95.9 1889.59   101.6 1893.79   102.4 1894.27   104.5 1895.29   106.1 1895.95
   111.3 1897.24     120 1898.81   124.2 1899.47   128.5 1900.03   133.5 1900.53
#Mann= 5 ,-1,0
       0      .1       0      60     .05       0    66.8    .045       0
    83.4     .05       0      90     .06       0
Bank Sta=66.8,83.4
XS Rating Curve= 0 ,0
Exp/Cntr(USF)=0,0
Exp/Cntr=0.3,0.1

Type RM Length L Ch R = 1 ,10829   ,147.7,149.5,150.4
XS GIS Cut Line= 4
2186890.86200957669093.6801815962186939.44264092669145.395047229
2186984.88903799669236.8102137542186996.38123036 669258.74985372
#Sta/Elev= 30
       0 1886.67     1.9 1886.41     6.2 1886.05    23.2 1884.97    37.7 1883.63
      43 1883.25    51.5 1883.22    62.8 1883.72     102 1883.25   106.4 1882.82
   107.1 1882.62   110.9 1881.22   114.61879.582   115.4 1879.22   116.1 1879.11
   119.9 1878.81     125 1878.93   129.51879.577   133.3 1880.28   137.7 1880.92
     140 1881.78   142.2 1882.76   146.7 1886.18   151.1 1889.86   160.1 1896.28
   164.5 1898.84     169 1900.58   173.5 1901.92     187 1904.47   197.8 1906.65
#Mann= 5 ,-1,0
       0     .05       0   80.95      .1       0   114.6    .045       0
   129.5      .1       0  193.04     .06       0
Bank Sta=114.6,129.5
XS Rating Curve= 0 ,0
Exp/Cntr(USF)=0,0
Exp/Cntr=0.3,0.1

Type RM Length L Ch R = 1 ,10680   ,126.5,123.4,118.8
XS GIS Cut Line= 4
2186807.80480113 669145.917419612186803.10344971669178.304507178
2186840.71426108669280.689493686 2186874.1460934669313.076581254
#Sta/Elev= 30
       0 1886.58     4.3 1886.15    35.8 1884.28    40.1 1883.69    52.8 1882.33
    69.9 1881.88    82.7 1880.93    86.9 1880.86    91.2 1881.07      95 1880.29
    98.31878.845    99.7 1878.22     104 1877.73   107.5 1878.13   108.2 1878.27
   109.71878.842   112.5 1879.91   116.8  1880.5   123.1 1880.44   125.3 1880.56
   126.2 1880.79   129.5 1881.89   133.8  1884.5   138.1 1887.39   141.8 1889.67
   144.6 1890.77   147.4 1891.68     154 1893.42   172.9 1898.04   188.3  1902.3
#Mann= 4 ,-1,0
       0     .05       0    98.3    .045       0   109.7     .05       0
   151.8     .06       0
Bank Sta=98.3,109.7
XS Rating Curve= 0 ,0
Exp/Cntr(USF)=0,0
Exp/Cntr=0.3,0.1

Type RM Length L Ch R = 1 ,10556   ,124.1,122.3,118.8
XS GIS Cut Line= 4
2186642.36347312669183.226081432 2186669.0044645669232.851457545
2186766.68809959669336.8035611932186786.53825004669370.757765902
#Sta/Elev= 30
       0 1885.27    11.3 1885.52    24.9 1884.62    46.1 1883.97    58.8 1883.26
    72.6 1882.03    84.2 1881.54    90.2 1880.59    95.6    1880   106.2 1880.23
   109.7 1880.12   111.7 1879.93   115.4 1878.64   117.2 1878.05   119.4 1877.81
   121.1 1877.88  124.61 1878.67   128.1 1879.64   132.4 1880.23   144.6 1880.29
   157.8 1880.83   161.1 1881.06   171.9 1882.53   174.8  1882.5   177.7 1882.74
   188.5 1884.88   195.3 1887.03   209.8 1890.76   225.7 1893.91   238.3 1896.92
#Mann= 5 ,-1,0
       0      .1       0      20     .05       0   115.4    .045       0
  124.61     .05       0  218.97     .06       0
Bank Sta=115.4,124.61
XS Rating Curve= 0 ,0
Exp/Cntr(USF)=0,0
Exp/Cntr=0.3,0.1

Type RM Length L Ch R = 1 ,10434   ,107.3,123.8,133.6
XS GIS Cut Line= 4
 2186586.8370292 669319.718961542186612.95564821669342.180973886
2186713.77351757669401.2090528422186738.84739182669417.924969006
#Sta/Elev= 30
       0 1891.57    17.6 1888.29    22.9  1886.8    30.3 1884.16    33.2 1883.31
    38.2 1882.69    47.8 1882.34    56.7 1881.58    71.2 1879.41      77 1877.89
      80 1877.18    82.8 1877.21    85.8 1877.91    89.2 1879.28    91.6  1879.7
    93.8 1879.88    98.4 1879.51   103.1 1879.59   107.7 1880.03   112.3  1880.2
   123.8 1879.84   127.5 1879.98   130.9 1880.47   135.5    1882   141.3 1885.32
   144.8 1887.04   149.4 1889.11     153 1890.34     159 1892.08   181.4 1896.93
#Mann= 3 ,-1,0
       0      .1       0      77    .045       0    85.8     .05       0
Bank Sta=77,85.8
XS Rating Curve= 0 ,0
Exp/Cntr(USF)=0,0
Exp/Cntr=0.3,0.1

Type RM Length L Ch R = 1 ,10310   ,20.8,20.6,21.4
XS GIS Cut Line= 5
2186622.80228638669363.9979380082186621.38665722669397.482007575
  2186620.969673669443.7249475192186619.26582536669496.873800346
2186618.90016469669531.935434501
#Sta/Elev= 23
       0 1881.93     9.2 1881.91    13.2 1881.82    41.2 1880.92    53.2  1880.3
    62.2 1880.16    73.2 1879.86    81.2 1879.77    93.2 1879.43    97.2 1879.24
      99 1878.97   101.3 1878.64   105.2 1878.31   109.4 1878.56   113.5 1878.95
   121.8 1879.36   129.2 1879.63   133.2 1879.74   141.2  1879.8   149.2    1880
   157.2 1880.51   161.2 1880.93     168 1881.47
#Mann= 3 ,-1,0
       0      .1       0      99    .045       0   113.5      .1       0
Bank Sta=99,113.5
XS Rating Curve= 0 ,0
Exp/Cntr(USF)=0,0
Exp/Cntr=0.3,0.1