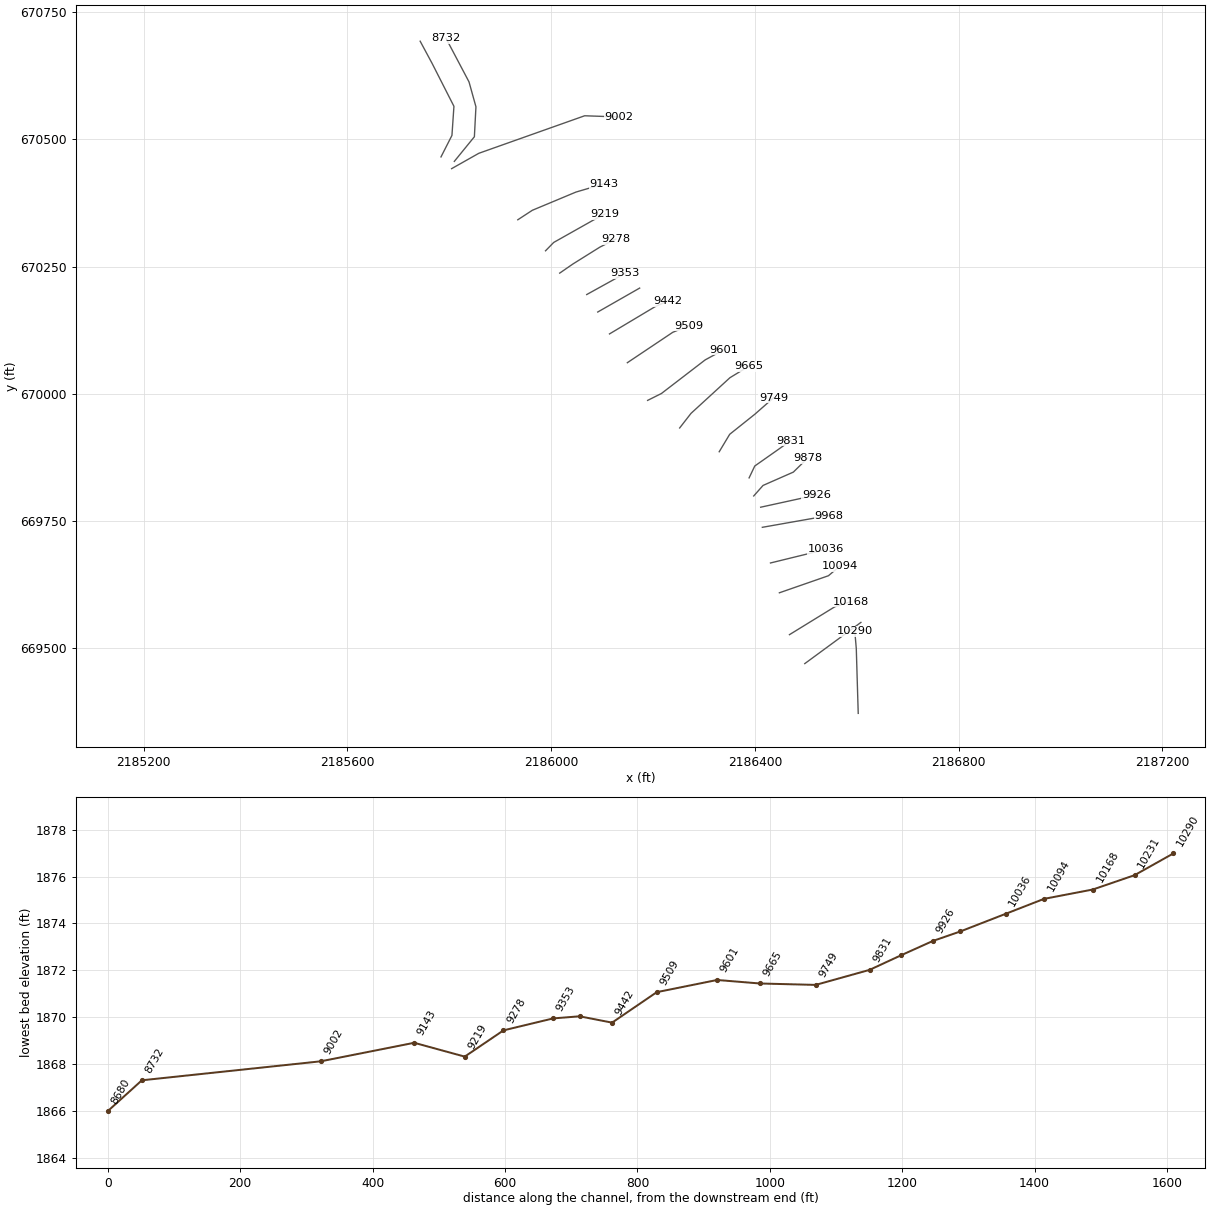
HEC-RAS study QUEENSFK.prj: QUEENSFK

--- QUEENSFK.g01 (geometry) --- (continued)

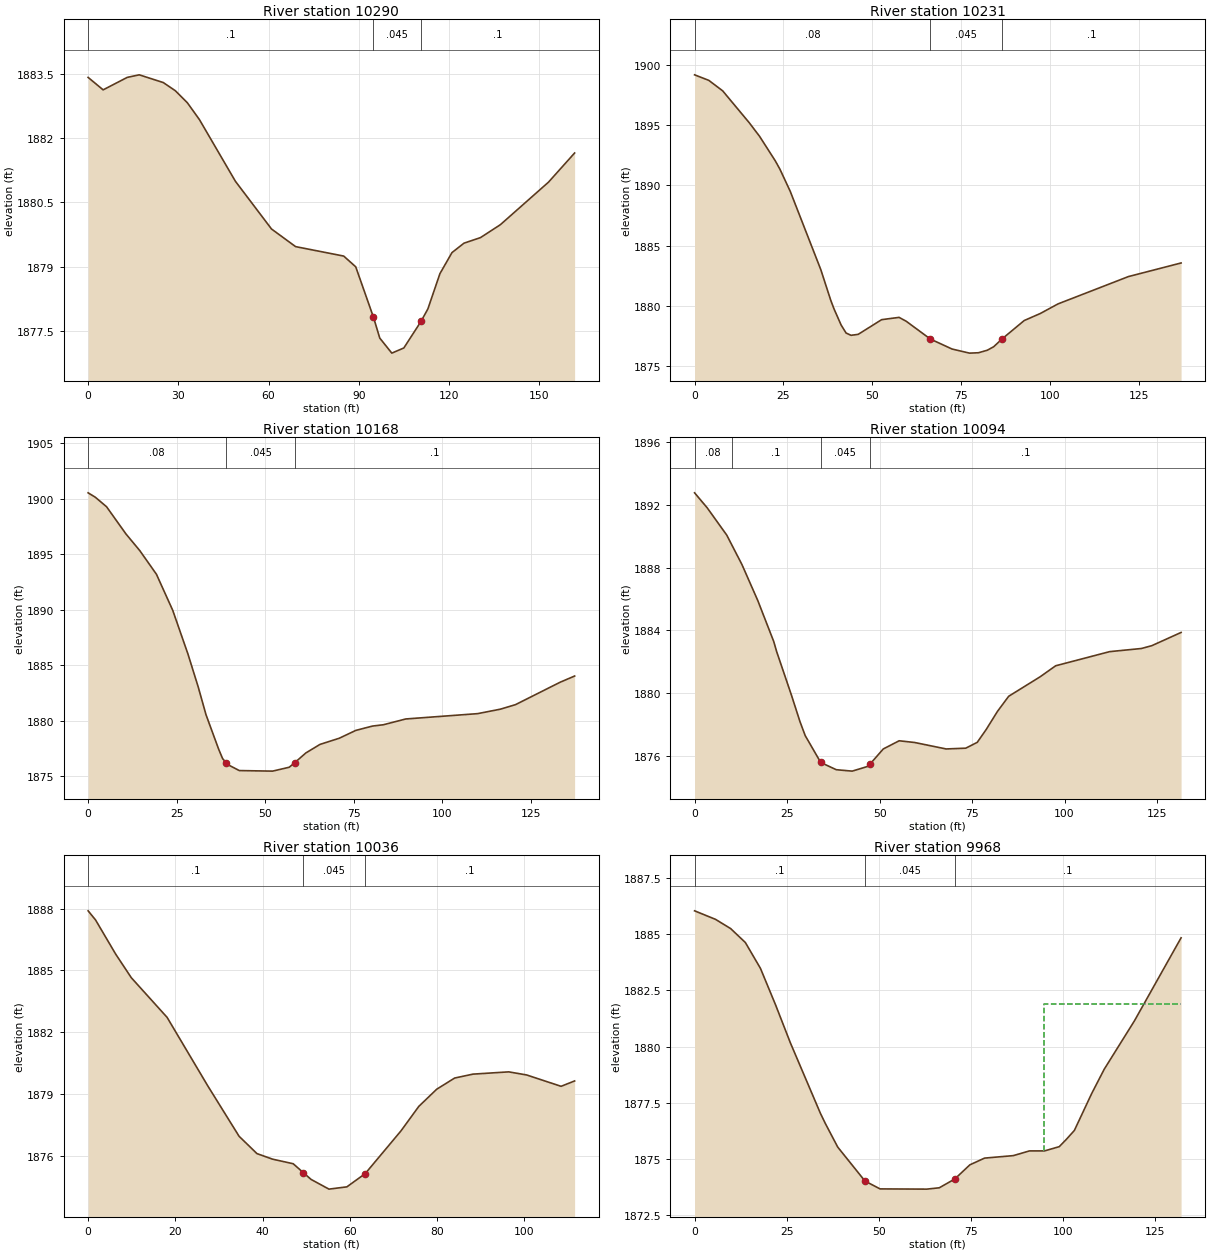
Type RM Length L Ch R = 1 ,10290   ,70.8,58.8,45.8
XS GIS Cut Line= 3
  2186602.775443  669372.21739242186598.96734835669499.577002405
2186596.00549695669533.849854267
#Sta/Elev= 26
       0 1883.41       5 1883.12      13 1883.41      17 1883.47      25 1883.29
      29  1883.1      33 1882.82      37 1882.43      49 1880.99      61 1879.88
      69 1879.47      85 1879.25      89    1879    94.91877.826      97 1877.34
     101 1876.99     105 1877.11   110.71877.727     113 1878.02     117 1878.84
     121 1879.33     125 1879.55   130.5 1879.68   137.1 1879.98   153.1 1880.97
   161.8 1881.65
#Mann= 3 ,-1,0
       0      .1       0    94.9    .045       0   110.7      .1       0
Bank Sta=94.9,110.7
XS Rating Curve= 0 ,0
Exp/Cntr(USF)=0,0
Exp/Cntr=0.3,0.1

Type RM Length L Ch R = 1 ,10231   ,64.1,62.9,62.3
XS GIS Cut Line= 2
 2186497.8403656669469.9559515962186608.06093781669550.923670518
#Sta/Elev= 30
       0 1899.18       4 1898.72     7.9 1897.85    15.4 1895.19    18.3 1894.06
    22.7 1892.03      24 1891.34    26.9  1889.5    35.5 1882.99    38.3 1880.44
    39.2 1879.74    41.2  1878.4    42.6 1877.73      44 1877.54      46 1877.62
    52.6 1878.84    57.5 1879.03    59.5 1878.71    66.3 1877.23    72.4  1876.4
    77.3 1876.06    79.8 1876.09    82.3  1876.3    84.1 1876.59    86.5 1877.25
    92.7 1878.77    97.2 1879.35   102.2 1880.15     122 1882.42   136.8 1883.55
#Mann= 3 ,-1,0
       0     .08       0    66.3    .045       0    86.5      .1       0
Bank Sta=66.3,86.5
XS Rating Curve= 0 ,0
Exp/Cntr(USF)=0,0
Exp/Cntr=0.3,0.1

Type RM Length L Ch R = 1 ,10168   ,77.5,73.8,71
XS GIS Cut Line= 3
2186467.77998555669526.8372542612186556.88940039669581.673817239
2186588.11577653669591.574863332
#Sta/Elev= 30
       0 1900.53       2 1900.14     5.2 1899.28    10.7 1896.82    14.6 1895.32
    19.3 1893.19    23.9 1889.94    28.2    1886    31.1 1883.03    33.3 1880.53
    36.9  1877.4      38 1876.57   39.08 1876.19    39.8 1875.98    42.7  1875.5
    52.1 1875.45    56.8  1875.8    58.31876.197    61.5 1877.09    65.5 1877.86
    70.9 1878.41    75.6 1879.12    80.3 1879.51    83.4 1879.63    89.7 1880.15
     110 1880.63   116.4 1881.03   120.7 1881.44   133.3 1883.46   137.4 1884.02
#Mann= 3 ,-1,0
       0     .08       0   39.08    .045       0    58.3      .1       0
Bank Sta=39.08,58.3
XS Rating Curve= 0 ,0
Exp/Cntr(USF)=0,0
Exp/Cntr=0.3,0.1

Type RM Length L Ch R = 1 ,10094   ,59.8,58.1,57.8
XS GIS Cut Line= 3
2186447.97789336669609.0920987282186544.32268804669642.603331659
2186566.79044648669661.643804915
#Sta/Elev= 30
       0 1892.75     3.4  1891.8     8.7 1890.06    12.8 1888.19    17.1 1885.89
    21.4 1883.29    22.2 1882.64    26.2 1879.87    28.5 1878.19    29.9 1877.31
    34.1  1875.6    38.3 1875.14    42.6 1875.05    46.8 1875.35    47.4 1875.49
      51 1876.46    55.3 1876.98    59.5 1876.87      68 1876.46    73.3 1876.51
    76.4 1876.88    78.8 1877.69    81.9 1878.86    84.9 1879.81    93.4 1881.05
    97.6 1881.75   112.2 1882.65   120.8 1882.85   123.6 1883.03   131.5 1883.87
#Mann= 4 ,-1,0
       0     .08       0      10      .1       0    34.1    .045       0
    47.4      .1       0
Bank Sta=34.1,47.4
XS Rating Curve= 0 ,0
Exp/Cntr(USF)=0,0
Exp/Cntr=0.3,0.1

Type RM Length L Ch R = 1 ,10036   ,69.2,68.3,67.5
XS GIS Cut Line= 2
2186430.54763297669667.678553627  2186538.815572669694.205740967
#Sta/Elev= 24
       0 1887.89     1.7 1887.45     6.3  1885.8     9.9 1884.65    18.1 1882.73
    27.4 1879.42    34.6 1876.97    38.7 1876.13    42.3 1875.86      47 1875.64
    49.31875.214    51.1 1874.88    55.2 1874.41    59.3 1874.52    63.5 1875.16
    71.7 1877.23    75.8 1878.42    79.9 1879.25      84 1879.79    88.2 1879.98
    96.4 1880.09   100.5 1879.94   108.4 1879.39   111.5 1879.65
#Mann= 3 ,-1,0
       0      .1       0    49.3    .045       0    63.5      .1       0
Bank Sta=49.3,63.5
XS Rating Curve= 0 ,0
Exp/Cntr(USF)=0,0
Exp/Cntr=0.3,0.1

Type RM Length L Ch R = 1 ,9968    ,42.2,41.8,42.4
XS GIS Cut Line= 2
 2186414.5413649669737.7214497222186544.76879927669760.758071687
#Sta/Elev= 27
       0 1886.04     5.7 1885.66     9.8 1885.25    13.8 1884.63    17.9 1883.48
      22 1881.86      26 1880.18    34.2 1877.03    35.5 1876.59    38.9 1875.53
    46.3 1874.02    50.4 1873.67    63.1 1873.66    66.5 1873.72    70.7 1874.11
    74.8 1874.74    78.8 1875.04    86.6 1875.15      91 1875.36    95.1 1875.36
    99.1 1875.55     101 1875.87   103.2 1876.27   107.9 1877.91   111.3 1878.99
   119.5 1881.14   132.2 1884.84
#Mann= 3 ,-1,0
       0      .1       0    46.3    .045       0    70.7      .1       0
#XS Ineff= 2 , 0
                           94.91         1881.89
Permanent Ineff=
       F       F
Bank Sta=46.3,70.7
XS Rating Curve= 0 ,0
Exp/Cntr(USF)=0,0
Exp/Cntr=0.3,0.1

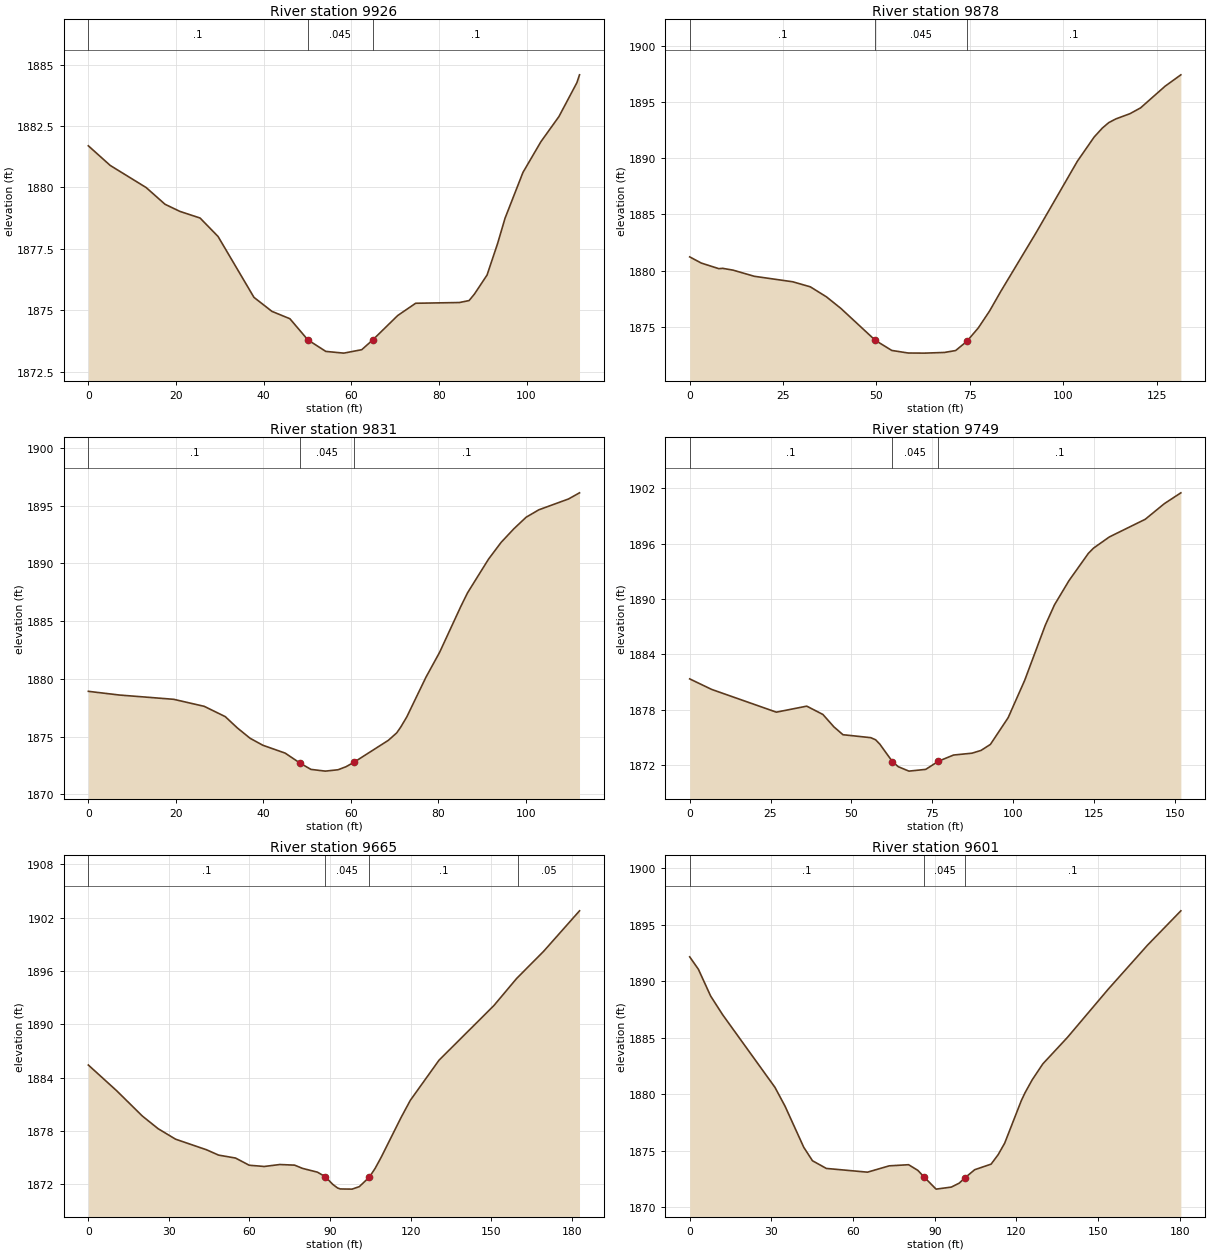
Type RM Length L Ch R = 1 ,9926    ,46.6,47.9,51.3
XS GIS Cut Line= 2
2186411.25041891669777.2128016612186520.79190702 669801.18969391
#Sta/Elev= 28
       0 1881.69       5 1880.89    13.2 1879.99    17.5 1879.31    20.9 1879.02
    25.5 1878.75    29.6    1878    37.8 1875.52    41.9 1874.95      46 1874.65
    50.1 1873.79    54.2 1873.32    58.3 1873.25    62.4 1873.39    64.91873.786
    70.6 1874.78    74.7 1875.28    84.7 1875.31    86.9 1875.39    88.1 1875.65
      91 1876.43    93.4 1877.71    95.1 1878.74    99.2 1880.61   103.3 1881.86
   107.4 1882.88   111.5 1884.26   112.1 1884.58
#Mann= 3 ,-1,0
       0      .1       0    50.1    .045       0    64.9      .1       0
Bank Sta=50.1,64.9
XS Rating Curve= 0 ,0
Exp/Cntr(USF)=0,0
Exp/Cntr=0.3,0.1

Type RM Length L Ch R = 1 ,9878    ,45.1,47.4,51
XS GIS Cut Line= 4
2186397.61649979669799.3091533412186415.95177033669819.995099595
2186475.44951847 669846.194580862186503.21052848669873.400370667
#Sta/Elev= 30
       0 1881.22     3.1 1880.67     7.8 1880.17     8.8  1880.2    11.6 1880.04
    17.3 1879.49    27.6    1879    32.3 1878.55    36.6 1877.66    40.5 1876.62
    49.7 1873.78    54.1 1872.88    58.5 1872.65    62.9 1872.64    68.2  1872.7
    71.2 1872.87    74.2 1873.69    77.3  1874.9    80.3  1876.4    83.3 1878.15
    92.7 1883.35   103.8 1889.75   108.3 1891.91   110.5 1892.71   112.2 1893.19
   114.1 1893.52   117.9 1893.99   120.7  1894.5   127.3 1896.44   131.5 1897.45
#Mann= 3 ,-1,0
       0      .1       0    49.7    .045       0    74.2      .1       0
Bank Sta=49.7,74.2
XS Rating Curve= 0 ,0
Exp/Cntr(USF)=0,0
Exp/Cntr=0.3,0.1

Type RM Length L Ch R = 1 ,9831    ,80.5,81.3,81.9
XS GIS Cut Line= 4
2186388.55755715669834.8125667572186399.66196115669858.131815163
2186447.41089836669891.7226372722186470.17492657669908.101633176
#Sta/Elev= 30
       0 1878.93     7.1 1878.61    19.5 1878.24    26.5 1877.63    31.3 1876.74
    34.1 1875.75      37 1874.86    39.9 1874.26      45 1873.58    48.5 1872.69
    50.9 1872.17    54.2 1872.02    57.1 1872.14    58.9  1872.4    60.7 1872.78
    68.6 1874.69    70.5 1875.33    71.4 1875.82    72.8 1876.71    77.2 1880.16
    80.3  1882.3    85.2 1886.31    86.7 1887.46    91.5 1890.38    94.4 1891.84
    97.3 1893.01   100.1 1894.01     103 1894.65   109.8 1895.59   112.3 1896.12
#Mann= 3 ,-1,0
       0      .1       0    48.5    .045       0    60.7      .1       0
Bank Sta=48.5,60.7
XS Rating Curve= 0 ,0
Exp/Cntr(USF)=0,0
Exp/Cntr=0.3,0.1

Type RM Length L Ch R = 1 ,9749    ,83.3,84.3,85
XS GIS Cut Line= 4
2186329.88501371 669886.165042822186350.44872483669920.437894681
2186399.80163151669959.851674322  2186436.473583669992.068155071
#Sta/Elev= 30
       0 1881.36     6.8 1880.22    26.8 1877.76    36.2 1878.41    41.2 1877.51
    44.6 1876.17    47.4 1875.32      56    1875    57.5 1874.77    58.8  1874.3
    62.7 1872.41    64.5 1871.86    67.8 1871.38      73 1871.57   76.92 1872.45
    81.6 1873.12    87.3 1873.32    90.1 1873.62      93 1874.27    98.5 1877.17
   103.6  1881.2     110 1887.19   112.8 1889.36   117.3 1891.99   123.3 1894.94
   124.9 1895.51   129.8 1896.72   140.9 1898.63   146.8 1900.32   151.9 1901.49
#Mann= 3 ,-1,0
       0      .1       0    62.7    .045       0   76.92      .1       0
Bank Sta=62.7,76.92
XS Rating Curve= 0 ,0
Exp/Cntr(USF)=0,0
Exp/Cntr=0.3,0.1

Type RM Length L Ch R = 1 ,9665    ,65.2,64.5,63.4
XS GIS Cut Line= 4
 2186252.2298054 669932.896534222186274.52278915 669961.55894191
2186350.95587633670031.6226051512186387.58006393670053.915588909
#Sta/Elev= 30
       0 1885.41    10.5 1882.53    20.1 1879.67      26 1878.24    32.5 1877.06
      44 1875.87    48.5 1875.27    54.8 1874.94    59.9 1874.13    65.5 1873.99
    71.3 1874.21    76.8 1874.14    79.7 1873.78    85.3 1873.35    88.2 1872.85
      91 1871.98    92.8 1871.57    93.8 1871.46    98.2 1871.44   100.9 1871.72
  104.67  1872.8   106.8 1873.78   109.1 1875.06   116.5 1879.53   119.9 1881.44
   130.6 1885.96     151  1892.1   159.5 1895.16   169.5  1898.2   182.9 1902.77
#Mann= 4 ,-1,0
       0      .1       0    88.2    .045       0  104.67      .1       0
     160     .05       0
Bank Sta=88.2,104.67
XS Rating Curve= 0 ,0
Exp/Cntr(USF)=0,0
Exp/Cntr=0.3,0.1

Type RM Length L Ch R = 1 ,9601    ,93,91.2,89.7
XS GIS Cut Line= 4
2186189.33174408669987.0366376342186216.40179578670000.571663487
2186302.38901885670066.6544367712186339.01320646670086.558886556
#Sta/Elev= 30
       0 1892.14     3.2 1891.04     7.7 1888.67    12.1 1887.02    31.3  1880.6
      35 1878.94    41.9 1875.29    45.1  1874.1    50.2 1873.42    65.3 1873.09
    73.3 1873.65    80.4 1873.75    83.8 1873.25    86.21872.636    90.5 1871.59
    96.1 1871.77      99 1872.12   101.11872.592   104.7 1873.31   110.7  1873.8
   113.3 1874.64   115.7 1875.66   121.8 1879.42   123.2 1880.13   125.8 1881.26
   129.7 1882.67   138.7    1885   153.7 1889.27   168.1 1893.16   180.4 1896.21
#Mann= 3 ,-1,0
       0      .1       0    86.2    .045       0   101.1      .1       0
Bank Sta=86.2,101.1
XS Rating Curve= 0 ,0
Exp/Cntr(USF)=0,0
Exp/Cntr=0.3,0.1

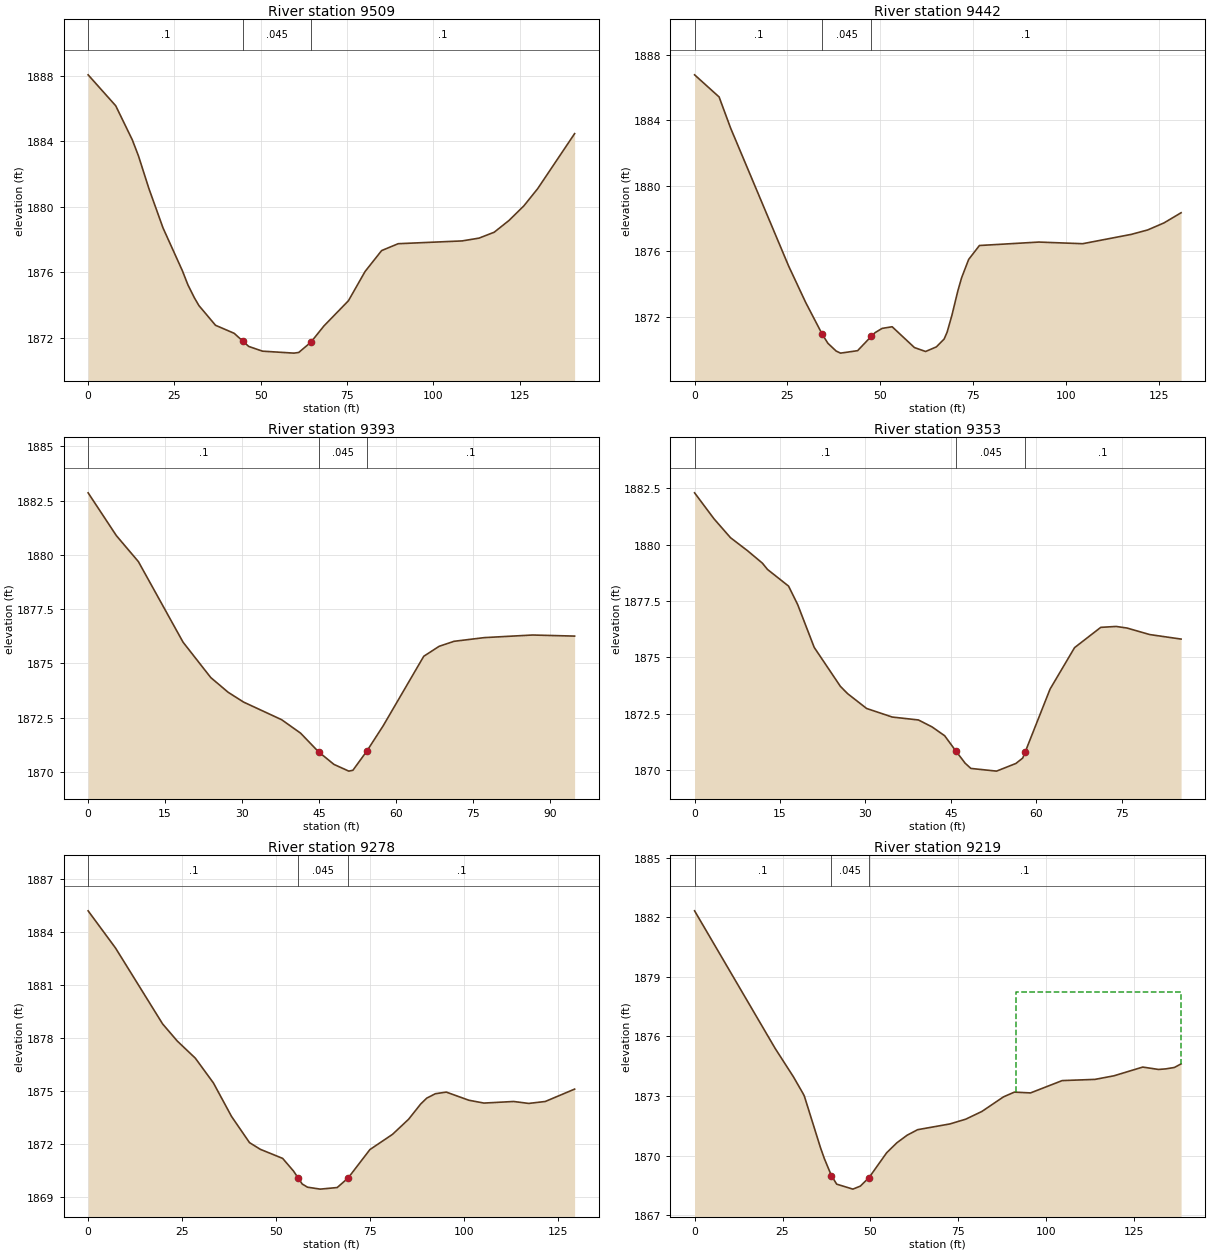
Type RM Length L Ch R = 1 ,9509    ,66.6,67.5,66.7
XS GIS Cut Line= 3
2186149.52284451670061.0811908322186238.69477954670120.794540185
2186269.74572121670133.533388047
#Sta/Elev= 30
       0 1888.06       8 1886.17    12.8 1884.09    14.6  1883.1    17.6 1881.12
    21.7 1878.71    27.3  1876.1    28.9 1875.24    30.8 1874.44    32.1 1873.97
    36.9 1872.77    42.3 1872.28    44.91871.785    46.5 1871.48    50.5 1871.19
    59.6 1871.07      61 1871.11    64.51871.732    68.3 1872.73    75.4 1874.27
    80.2 1876.05      85 1877.33    89.8 1877.75   108.3 1877.92   113.2 1878.09
   117.6 1878.45   121.9 1879.17   126.2 1880.06   130.2 1881.11   140.9 1884.47
#Mann= 3 ,-1,0
       0      .1       0    44.9    .045       0    64.5      .1       0
Bank Sta=44.9,64.5
XS Rating Curve= 0 ,0
Exp/Cntr(USF)=0,0
Exp/Cntr=0.3,0.1

Type RM Length L Ch R = 1 ,9442    ,49.8,49.1,48.5
XS GIS Cut Line= 3
2186114.49101289 670117.609828222186203.66294792670170.953753642
2186228.34446565670182.100245521
#Sta/Elev= 30
       0 1886.76     6.6 1885.41     9.7 1883.51    25.3  1875.1    29.9 1872.87
    34.41870.911    35.9 1870.37    38.1  1869.9    39.3 1869.77    43.9 1869.92
    47.6  1870.8    48.6 1871.02    50.5 1871.28    53.2 1871.38    59.2 1870.11
    62.2 1869.87    65.1 1870.15    67.2 1870.63      68 1871.05    69.3 1872.09
    70.9 1873.58    71.9 1874.37    73.8 1875.49    76.7 1876.34    92.7 1876.55
   104.5 1876.45   117.6 1877.02     122 1877.29   126.4 1877.72     131 1878.34
#Mann= 3 ,-1,0
       0      .1       0    34.4    .045       0    47.6      .1       0
Bank Sta=34.4,47.6
XS Rating Curve= 0 ,0
Exp/Cntr(USF)=0,0
Exp/Cntr=0.3,0.1

Type RM Length L Ch R = 1 ,9393    ,40,39.9,39.7
XS GIS Cut Line= 2
 2186091.4030056670160.6463298632186173.67665547670207.659844075
#Sta/Elev= 21
       0 1882.86     5.5 1880.89     9.8 1879.69    18.5 1875.98    23.9 1874.35
    27.3 1873.67    30.3 1873.22    37.7 1872.41    41.4 1871.79    44.9 1870.93
    47.9 1870.35    50.8 1870.04    51.6 1870.08    54.31870.959    57.5 1872.13
    65.4 1875.33    68.4 1875.79    71.3 1876.02    77.2 1876.19    86.6 1876.31
    94.8 1876.26
#Mann= 3 ,-1,0
       0      .1       0    44.9    .045       0    54.3      .1       0
Bank Sta=44.9,54.3
XS Rating Curve= 0 ,0
Exp/Cntr(USF)=0,0
Exp/Cntr=0.3,0.1

Type RM Length L Ch R = 1 ,9353    ,74.3,75,75
XS GIS Cut Line= 2
2186069.77678906670194.9661952382186144.52827666670236.338087745
#Sta/Elev= 30
       0  1882.3     3.4 1881.15     6.3 1880.31     9.3 1879.73    11.9 1879.18
    12.8  1878.9    16.5 1878.16    18.1 1877.34      21 1875.44    25.6 1873.71
    26.9 1873.38    30.2 1872.73    34.7 1872.35    39.3 1872.22    41.7 1871.91
    43.9 1871.52    45.9 1870.83    47.5  1870.3    48.5 1870.07      53 1869.95
    56.4 1870.29    57.6 1870.53      581870.777    62.4 1873.59    66.7 1875.43
    71.3 1876.33      74 1876.37    75.9  1876.3    79.9 1876.01    85.4 1875.81
#Mann= 3 ,-1,0
       0      .1       0    45.9    .045       0      58      .1       0
Bank Sta=45.9,58
XS Rating Curve= 0 ,0
Exp/Cntr(USF)=0,0
Exp/Cntr=0.3,0.1

Type RM Length L Ch R = 1 ,9278    ,58.3,58.5,58.5
XS GIS Cut Line= 4
2186016.70271049670237.0557113132186042.59775412670254.953756174
2186095.53026977 670288.084179642186127.13745538670304.078177175
#Sta/Elev= 30
       0 1885.19     7.3 1883.08    19.8 1878.79    23.7 1877.82    28.5 1876.85
    33.3 1875.45    38.1 1873.56    42.9 1872.07    45.8 1871.69    51.7 1871.18
    54.6 1870.46    55.91870.047    56.9 1869.73    58.3 1869.55    61.7 1869.44
    66.2 1869.53    69.1 1870.07    74.9 1871.68    80.9 1872.54    85.2  1873.4
    88.4 1874.26      90 1874.59    92.3 1874.84    95.2 1874.93   101.2 1874.47
   105.2 1874.31   113.1  1874.4   117.1 1874.29   121.5  1874.4   129.3  1875.1
#Mann= 3 ,-1,0
       0      .1       0    55.9    .045       0    69.1      .1       0
Bank Sta=55.9,69.1
XS Rating Curve= 0 ,0
Exp/Cntr(USF)=0,0
Exp/Cntr=0.3,0.1

Type RM Length L Ch R = 1 ,9219    ,76.4,76.3,75.3
XS GIS Cut Line= 4
2185988.91987542670280.9211028752186004.91387296670297.295909876
2186082.59900384670341.0889983652186105.82838121670353.274901249
#Sta/Elev= 30
       0 1882.32    22.9  1875.4    28.1 1873.97    30.8 1873.14    31.2    1873
    35.8  1870.4    36.9 1869.85    38.9    1869    40.4 1868.57      45 1868.32
    47.1 1868.47    49.6  1868.9    54.6 1870.15    57.5 1870.65    60.4 1871.03
    63.4 1871.31    72.6  1871.6    77.1 1871.84    81.7 1872.23    87.8 1872.96
    90.9  1873.2    95.5 1873.16   104.5 1873.78   113.8 1873.84   119.2 1874.02
   127.4 1874.46   131.9 1874.34     134 1874.37   136.4 1874.44   138.3 1874.62
#Mann= 3 ,-1,0
       0      .1       0    38.9    .045       0    49.6      .1       0
#XS Ineff= 2 , 0
                           91.24         1878.25
Permanent Ineff=
       F       F
Bank Sta=38.9,49.6
XS Rating Curve= 0 ,0
Exp/Cntr(USF)=0,0
Exp/Cntr=0.3,0.1

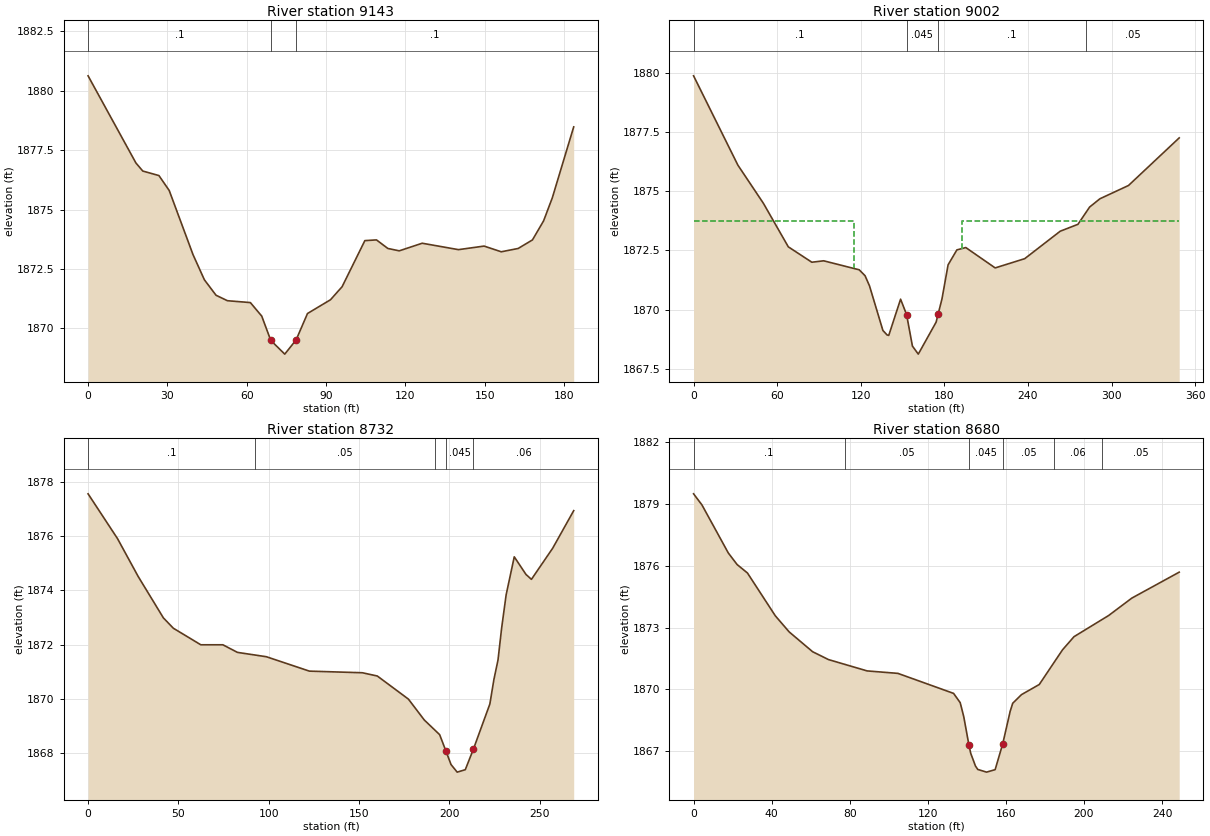
Type RM Length L Ch R = 1 ,9143    ,141.8,141.1,140.2
XS GIS Cut Line= 4
2185934.46412191670341.8506172952185963.02483179670360.510281086
2186048.70696145670396.3063708082186103.16271496670412.300368343
#Sta/Elev= 30
       0 1880.63    18.1 1876.96    20.7 1876.62    26.8 1876.43    30.7  1875.8
    39.7  1873.1      44 1872.04    48.4 1871.39    52.7 1871.16    61.4 1871.08
    65.7 1870.51    69.1 1869.49    74.4 1868.91    78.7 1869.51      83 1870.62
    91.7  1871.2    96.1 1871.75   104.7 1873.69   109.1 1873.72   113.4 1873.36
   117.7 1873.26   126.4 1873.58   140.1 1873.31   149.8 1873.46   156.3 1873.22
   162.7 1873.36   168.1 1873.72   172.3 1874.52   175.6 1875.49   183.7 1878.48
#Mann= 3 ,-1,0
       0      .1       0    69.1    .045       0    78.7      .1       0
Bank Sta=69.1,78.7
XS Rating Curve= 0 ,0
Exp/Cntr(USF)=0,0
Exp/Cntr=0.3,0.1

Type RM Length L Ch R = 1 ,9002    ,248.3,270.2,288.4
XS GIS Cut Line= 4
2185804.52339911670442.2518460842185857.92146464670472.433361381
2186065.70958919670546.1459083572186132.45717109670543.824253334
#Sta/Elev= 30
       0 1879.87    31.8  1876.1    50.1 1874.49      68 1872.65    84.9    1872
    93.4 1872.06   118.9 1871.68   123.1 1871.43   126.3    1871   135.9 1869.12
   138.9 1868.93   140.1 1868.91   148.6 1870.44   152.9 1869.79   157.1 1868.46
   161.3 1868.12   174.1 1869.47   175.6 1869.82   178.3 1870.45   182.7 1871.89
     189 1872.52   195.4 1872.62   216.5 1871.76   237.7 1872.15   263.2 1873.31
   275.9  1873.6   284.3 1874.33   291.7 1874.68   312.2 1875.24   348.6 1877.25
#Mann= 4 ,-1,0
       0      .1       0   152.9    .045       0   175.6      .1       0
  281.34     .05       0
#XS Ineff= 2 , 0
          114.85 1873.76   192.7         1873.72
Permanent Ineff=
       F       F
Bank Sta=152.9,175.6
XS Rating Curve= 0 ,0
Exp/Cntr(USF)=0,0
Exp/Cntr=0.3,0.1

Type RM Length L Ch R = 1 ,8732    ,51.2,51.7,51.7
XS GIS Cut Line= 5
2185809.84340895670456.5527402992185849.23001872 670504.94751889
2185852.28289663670563.8090914412185838.69599102670612.703146222
2185793.56301738 670698.26774209
#Sta/Elev= 30
       0 1877.56    16.3 1875.91    27.7 1874.52    41.7 1872.99    47.2 1872.61
    62.4    1872    74.6    1872    82.7 1871.72    98.7 1871.56   122.5 1871.03
   151.8 1870.97   160.1 1870.85   177.3    1870   186.1 1869.23   194.6 1868.69
198.01321868.098   200.9 1867.59   204.3 1867.31   208.8  1867.4213.31321868.162
   222.4 1869.82   224.6 1870.71   226.9 1871.44   228.9 1872.61   231.4 1873.84
   235.9 1875.24   242.4 1874.59   245.4 1874.41   257.2 1875.56   268.8 1876.94
#Mann= 5 ,-1,0
       0      .1       0    92.4     .05       0  192.08     .06       0
198.0132    .045       0213.3132     .06       0
Bank Sta=198.0132,213.3132
XS Rating Curve= 0 ,0
Exp/Cntr(USF)=0,0
Exp/Cntr=0.3,0.1

Type RM Length L Ch R = 1 ,8680    ,43,42.2,40.7
XS GIS Cut Line= 5
2185783.67997864670465.3307456772185805.18437252670507.600871071
2185809.07747707670564.7493617252185766.29517914670648.903552166
2185742.78842203670692.626120384
#Sta/Elev= 30
       0 1879.49     4.3 1878.95    17.8 1876.62    22.3 1876.06    27.6 1875.65
    41.9 1873.57      49 1872.79      61 1871.83    69.1 1871.45    88.9  1870.9
   104.7 1870.78   133.2 1869.81   136.6 1869.36   138.4 1868.69141.10621867.287
     142  1866.9   144.4 1866.29   145.6 1866.12   150.1 1865.99   154.5 1866.11
158.40621867.371   162.2 1868.94   163.5 1869.33     168 1869.75   177.1 1870.24
     189 1871.92   194.9 1872.56   212.7 1873.59   224.5 1874.43   248.8 1875.69
#Mann= 6 ,-1,0
       0      .1       0   77.43     .05       0141.1062    .045       0
158.4062     .05       0  184.71     .06       0  209.11     .05       0
Bank Sta=141.1062,158.4062
XS Rating Curve= 0 ,0
Exp/Cntr(USF)=0,0
Exp/Cntr=0.3,0.1