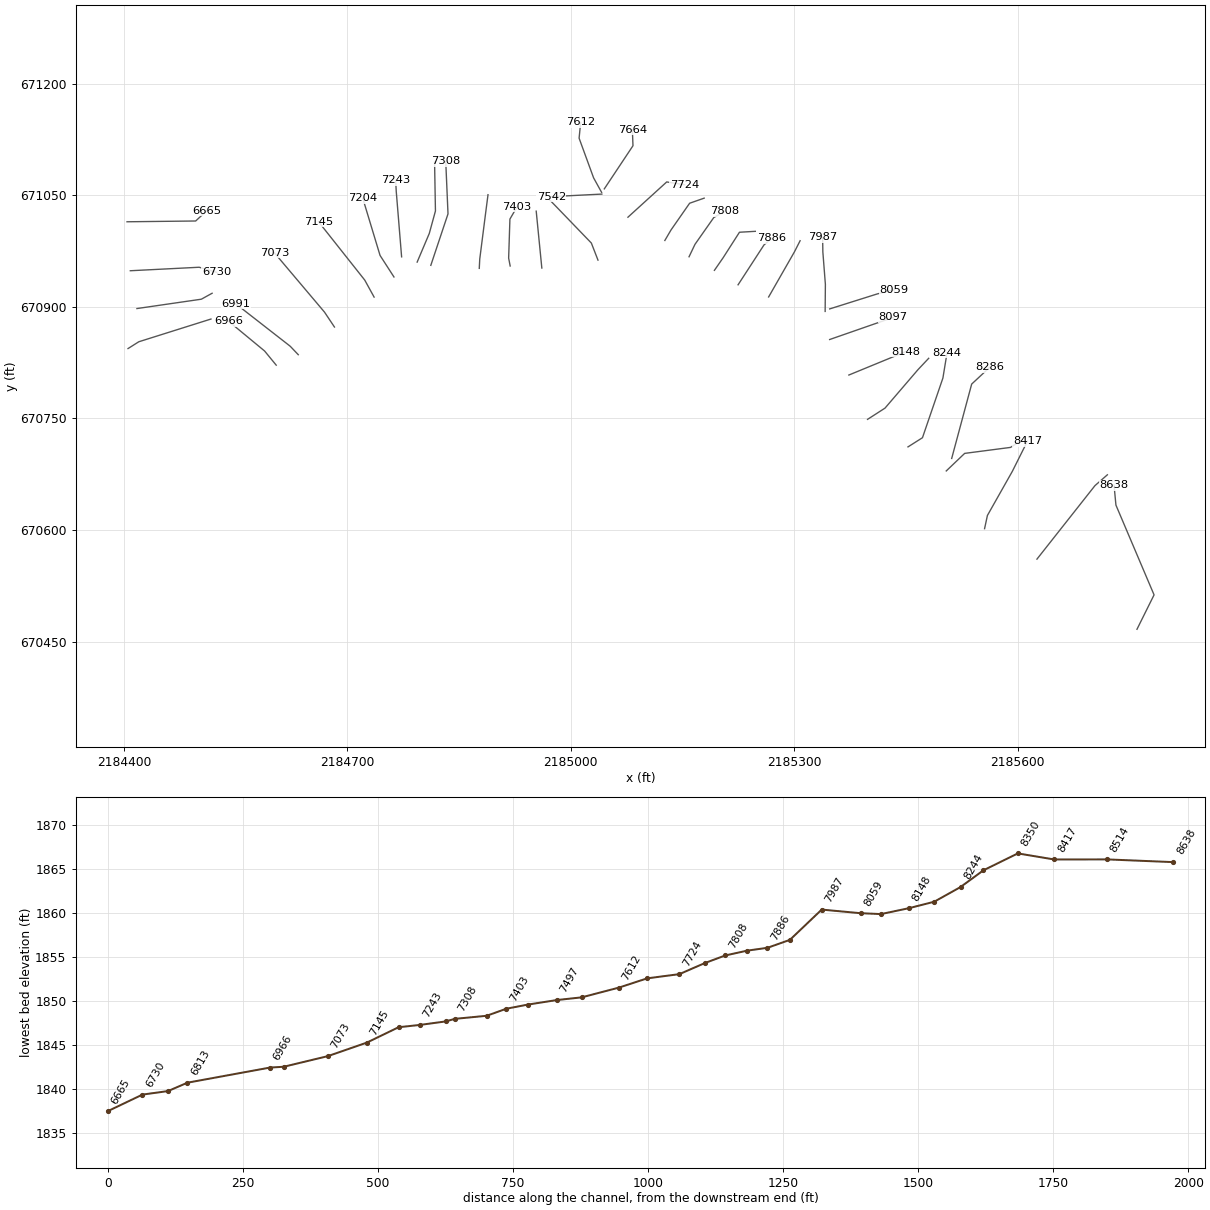
HEC-RAS study QUEENSFK.prj: QUEENSFK

--- QUEENSFK.g01 (geometry) --- (continued)

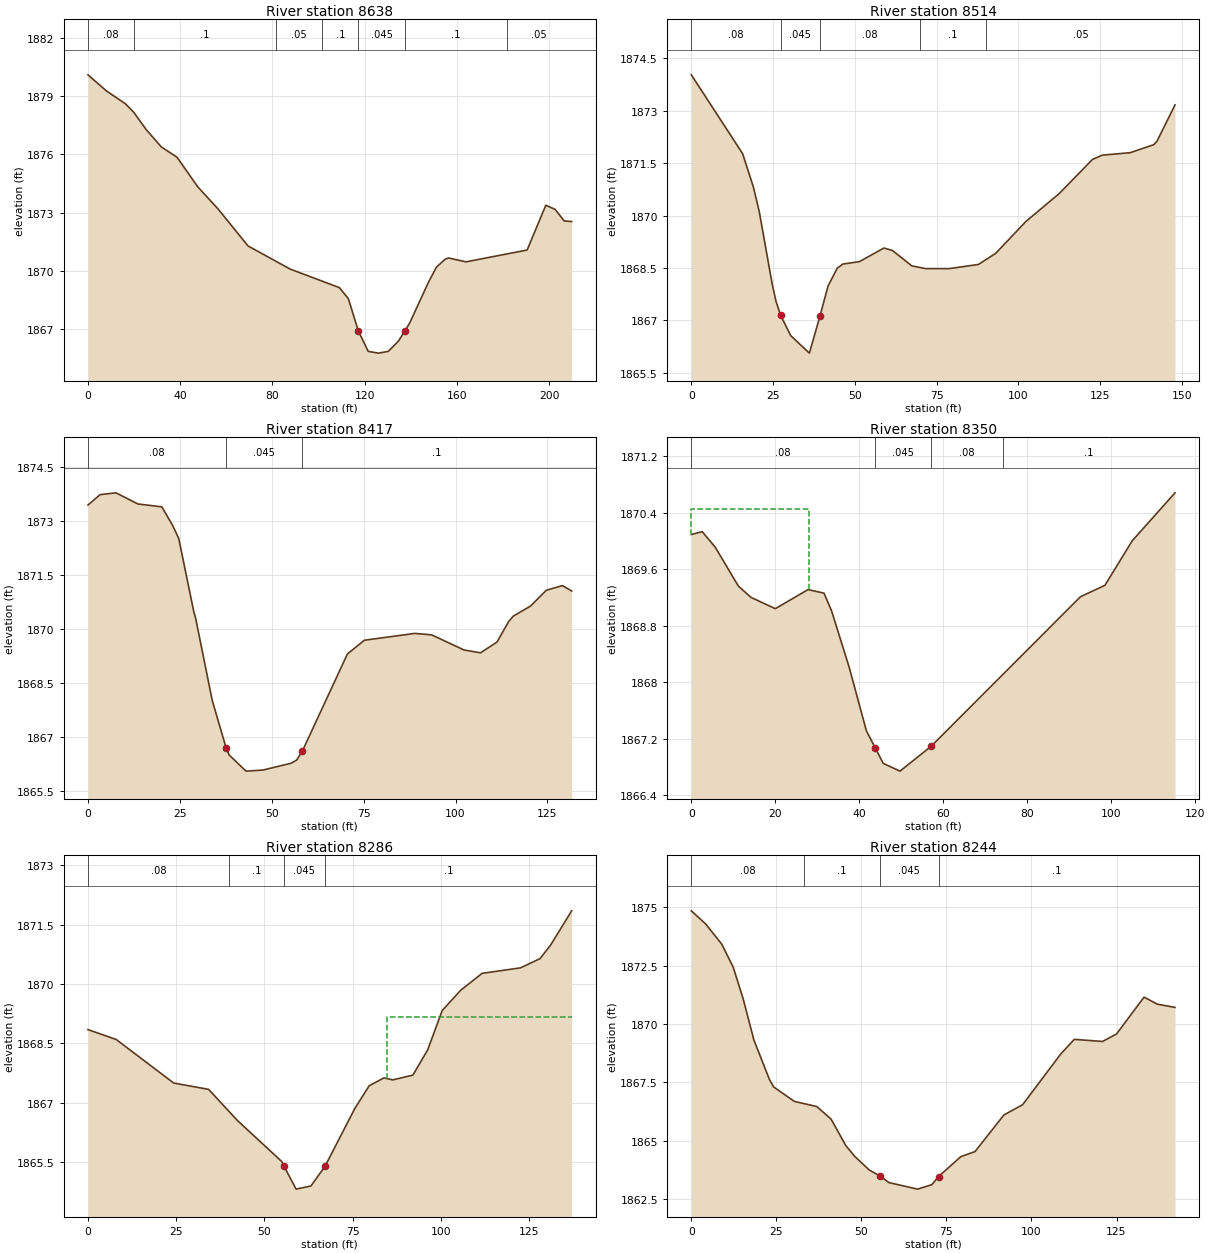
Type RM Length L Ch R = 1 ,8638    ,135.7,123.3,108.4
XS GIS Cut Line= 4
2185760.10478138670466.5687207042185783.04328748670512.790336965
2185731.85079422670633.4583567832185729.28481094670660.368873741
#Sta/Elev= 30
       0 1880.11       8 1879.28    16.3 1878.61    19.9 1878.17    25.2 1877.29
    31.8 1876.39    38.6 1875.86    47.6 1874.33    56.4 1873.19    69.4 1871.28
    87.6 1870.09     109 1869.13   112.9 1868.56   117.2  1866.9   121.5 1865.84
   125.9 1865.75   130.2 1865.84   134.6 1866.37   137.5 1866.91   139.5 1867.31
   147.6  1869.4   151.1 1870.19   154.8 1870.59   156.3 1870.66   163.9 1870.46
   190.4 1871.07   198.5 1873.38   202.5 1873.17   206.5 1872.57   209.7 1872.54
#Mann= 7 ,-1,0
       0     .08       0      20      .1       0    81.6     .05       0
   101.6      .1       0   117.2    .045       0   137.5      .1       0
   181.6     .05       0
Bank Sta=117.2,137.5
XS Rating Curve= 0 ,0
Exp/Cntr(USF)=0,0
Exp/Cntr=0.3,0.1

Type RM Length L Ch R = 1 ,8514    ,92.7,97.2,98.4
XS GIS Cut Line= 3
2185625.80920105 670560.84859594 2185703.6426857670659.576975791
2185720.35860186670674.203402436
#Sta/Elev= 29
       0 1874.03    15.7 1871.77      19 1870.81    20.8  1870.1    24.7 1868.05
    25.9 1867.54    27.31867.145    30.4 1866.56    36.1 1866.06    39.31867.109
    41.8 1867.98    44.6 1868.49    46.3 1868.61    51.4 1868.68    58.9 1869.07
    61.5    1869    67.4 1868.56    71.7 1868.48    78.8 1868.48    87.8  1868.6
    93.1 1868.92   102.3 1869.83   112.5 1870.63   122.7 1871.61   125.7 1871.73
   134.2  1871.8   141.4 1872.03   142.4 1872.13   147.9 1873.17
#Mann= 5 ,-1,0
       0     .08       0    27.3    .045       0    39.3     .08       0
      70      .1       0      90     .05       0
Bank Sta=27.3,39.3
XS Rating Curve= 0 ,0
Exp/Cntr(USF)=0,0
Exp/Cntr=0.3,0.1

Type RM Length L Ch R = 1 ,8417    ,81.3,67.5,56.1
XS GIS Cut Line= 4
  2185555.485108670601.7573819752185559.29320265670619.528490348
2185592.71981126670678.765518258 2185613.0296494 670719.38519454
#Sta/Elev= 30
       0 1873.45     3.3 1873.74     7.6 1873.79    13.6 1873.48    20.1  1873.4
      23 1872.89    24.7 1872.52    28.8 1870.48    29.3  1870.3    33.8 1868.02
    37.6 1866.69    38.4  1866.5      43 1866.05    47.6 1866.08    55.3 1866.27
    56.8 1866.36    58.31866.601    70.6 1869.31    75.2 1869.69    88.9 1869.88
    93.5 1869.84   102.3 1869.42   106.8 1869.34   111.3 1869.64   114.4  1870.2
   115.7 1870.36   120.4 1870.64   124.7 1871.08   129.1 1871.21   131.6 1871.06
#Mann= 3 ,-1,0
       0     .08       0    37.6    .045       0    58.3      .1       0
Bank Sta=37.6,58.3
XS Rating Curve= 0 ,0
Exp/Cntr(USF)=0,0
Exp/Cntr=0.3,0.1

Type RM Length L Ch R = 1 ,8350    ,50.3,63.7,76
XS GIS Cut Line= 4
2185504.04163809670679.373829427  2185528.748937670702.970687934
2185590.37837922670711.0213808372185606.20215492 670721.38549124
#Sta/Elev= 19
       0 1870.09     2.6 1870.13     5.7 1869.91    11.2 1869.36    14.2  1869.2
      20 1869.04    27.8 1869.31    31.6 1869.26    33.4 1869.01    37.6 1868.21
    41.7 1867.31    43.8 1867.07    45.7 1866.85    49.7 1866.74    57.11867.091
    92.7 1869.21    98.5 1869.37     105    1870   115.2 1870.68
#Mann= 4 ,-1,0
       0     .08       0    43.8    .045       0    57.1     .08       0
   74.17      .1       0
#XS Ineff= 2 , 0
           27.93 1870.45
Permanent Ineff=
       F       F
Bank Sta=43.8,57.1
XS Rating Curve= 0 ,0
Exp/Cntr(USF)=0,0
Exp/Cntr=0.3,0.1

Type RM Length L Ch R = 1 ,8286    ,43.8,42.4,41.6
XS GIS Cut Line= 3
2185511.33550675670696.1869470782185538.17114976670796.126583108
2185562.77308668670819.041252018
#Sta/Elev= 23
       0 1868.85       8  1868.6    24.3  1867.5    34.2 1867.34    42.4 1866.55
    54.9 1865.52    55.51865.409      59 1864.82    63.2  1864.9    67.21865.398
    75.6 1866.85    79.7 1867.43    83.9 1867.63    86.4 1867.58    92.1  1867.7
    96.3 1868.34   100.4 1869.33   105.6 1869.84   111.7 1870.27   122.6 1870.41
   128.1 1870.64   131.1 1870.98   137.1 1871.85
#Mann= 4 ,-1,0
       0     .08       0      40      .1       0    55.5    .045       0
    67.2      .1       0
#XS Ineff= 2 , 0
                           84.72         1869.17
Permanent Ineff=
       F       F
Bank Sta=55.5,67.2
XS Rating Curve= 0 ,0
Exp/Cntr(USF)=0,0
Exp/Cntr=0.3,0.1

Type RM Length L Ch R = 1 ,8244    ,56.7,48.7,44
XS GIS Cut Line= 4
2185452.66298908670711.6964582012185472.09569609670724.034684871
2185499.54825043 670804.233158232185505.10045243670838.163281573
#Sta/Elev= 30
       0 1874.85     4.2 1874.29     8.9 1873.43    12.3 1872.44    15.2  1871.1
    18.4 1869.31      23 1867.61    24.2  1867.3    30.3 1866.68    36.9 1866.46
    41.1 1865.92    45.4 1864.79      48 1864.33    52.3 1863.74    55.5 1863.48
    58.1  1863.2    66.5 1862.92    70.7 1863.11    72.7 1863.46    79.2 1864.31
    83.4 1864.53    91.9  1866.1    97.4 1866.54   108.7 1868.73   112.6 1869.34
   120.9 1869.25     125 1869.57   133.1 1871.15     137 1870.85   142.2 1870.71
#Mann= 4 ,-1,0
       0     .08       0   33.02      .1       0    55.5    .045       0
    72.7      .1       0
Bank Sta=55.5,72.7
XS Rating Curve= 0 ,0
Exp/Cntr(USF)=0,0
Exp/Cntr=0.3,0.1

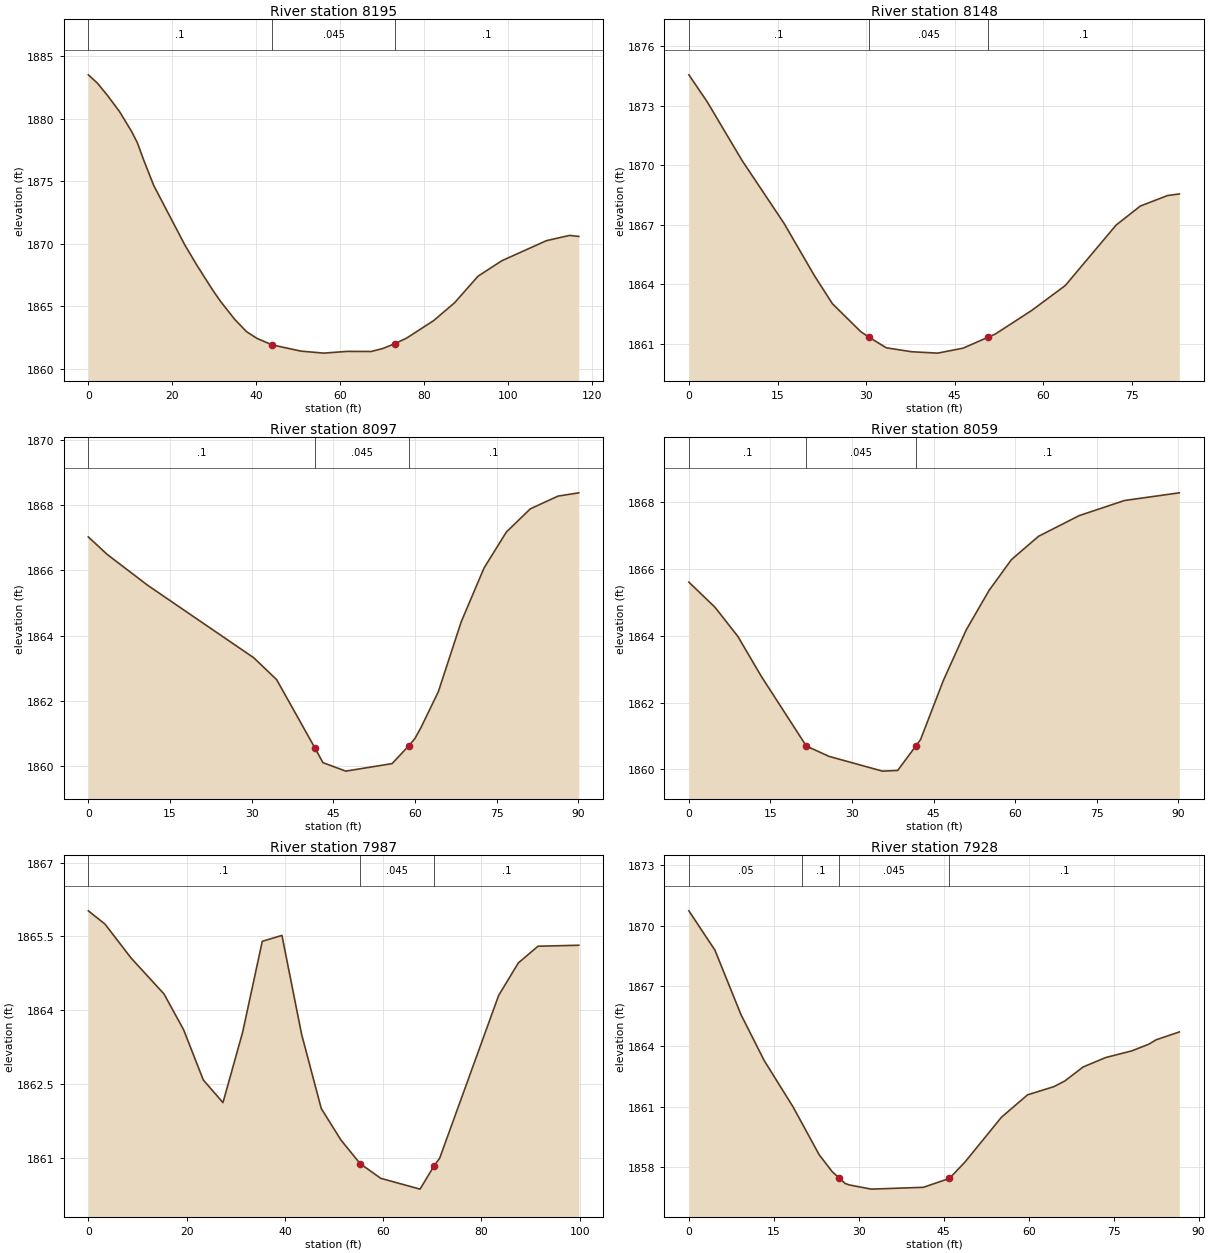
Type RM Length L Ch R = 1 ,8195    ,56.4,46.7,40.9
XS GIS Cut Line= 4
2185398.37479173670748.7111382122185421.81742241670763.825465884
2185465.92658276670815.3375622332185480.42399909670830.760345571
#Sta/Elev= 30
       0 1883.52     2.1 1882.88     4.5  1881.9     7.4  1880.6    10.3    1879
    11.7 1878.08    13.2  1876.7    15.6 1874.66      23 1869.91    25.9 1868.27
    29.7 1866.27    31.5  1865.4    34.9 1863.95    37.7 1862.97    40.2 1862.43
    43.8 1861.91    50.7 1861.41    56.1 1861.25    61.7 1861.39    67.4 1861.38
    70.2 1861.62    73.1 1862.01    75.9 1862.46    82.3 1863.85    87.3 1865.28
    92.9 1867.41    98.6 1868.65   109.2 1870.25   114.7 1870.67   116.9 1870.59
#Mann= 3 ,-1,0
       0      .1       0    43.8    .045       0    73.1      .1       0
Bank Sta=43.8,73.1
XS Rating Curve= 0 ,0
Exp/Cntr(USF)=0,0
Exp/Cntr=0.3,0.1

Type RM Length L Ch R = 1 ,8148    ,52.5,51.8,50.8
XS GIS Cut Line= 2
2185373.28646228670808.2953265522185450.03005887670839.895631031
#Sta/Elev= 20
       0 1874.56     3.1  1873.2       9 1870.24    16.1 1867.07    21.3  1864.4
    24.3 1863.01    29.1  1861.6    30.5 1861.32    33.4 1860.79    37.7 1860.59
    42.1 1860.52    46.4 1860.77    50.7 1861.33    51.9 1861.49      58 1862.67
    63.7 1863.93    72.3 1866.98    76.4 1867.94      81 1868.47      83 1868.55
#Mann= 3 ,-1,0
       0      .1       0    30.5    .045       0    50.7      .1       0
Bank Sta=30.5,50.7
XS Rating Curve= 0 ,0
Exp/Cntr(USF)=0,0
Exp/Cntr=0.3,0.1

Type RM Length L Ch R = 1 ,8097    ,39,37.8,37.7
XS GIS Cut Line= 2
2185347.49029536670856.018235357 2185432.6176462670885.683827317
#Sta/Elev= 19
       0 1867.02     3.5 1866.48    10.9 1865.54    30.4 1863.32    34.6 1862.65
    41.61860.568    43.1 1860.11    47.3 1859.85    55.8 1860.08    58.9 1860.63
      60 1860.85    61.1 1861.18    64.3 1862.28    68.5 1864.42    72.7 1866.07
    76.8 1867.17    81.2 1867.88    86.3 1868.27    90.1 1868.37
#Mann= 3 ,-1,0
       0      .1       0    41.6    .045       0    58.9      .1       0
Bank Sta=41.6,58.9
XS Rating Curve= 0 ,0
Exp/Cntr(USF)=0,0
Exp/Cntr=0.3,0.1

Type RM Length L Ch R = 1 ,8059    ,49.5,71.9,85.3
XS GIS Cut Line= 3
2185347.57728004670897.1725823412185411.55327018670917.355483993
2185434.02102862670922.686816505
#Sta/Elev= 18
       0  1865.6     4.8 1864.85       9 1863.98    13.3 1862.79    21.6  1860.7
    25.8 1860.39    35.6 1859.95    38.4 1859.97    41.71860.693    42.6 1860.89
    46.8 1862.66      51 1864.17    55.2 1865.35    59.3 1866.27    64.3 1866.97
    71.8 1867.59    80.1 1868.04    90.2 1868.27
#Mann= 3 ,-1,0
       0      .1       0    21.6    .045       0    41.7      .1       0
Bank Sta=21.6,41.7
XS Rating Curve= 0 ,0
Exp/Cntr(USF)=0,0
Exp/Cntr=0.3,0.1

Type RM Length L Ch R = 1 ,7987    ,67.1,58.9,49.2
XS GIS Cut Line= 4
2185341.44105585670893.7920767622185341.74951151 670930.18984544
2185338.35649918670973.6820944542185338.04804351670993.423257126
#Sta/Elev= 22
       0 1866.02     3.4 1865.75     8.7 1865.06    15.4 1864.33    19.4  1863.6
    23.4 1862.58    27.4 1862.12    31.4 1863.55    35.4  1865.4    39.4 1865.52
    43.4 1863.51    47.4    1862    51.4 1861.36    55.3 1860.88    59.5 1860.58
    67.5 1860.36    70.4 1860.84    71.5 1860.99    83.5  1864.3    87.5 1864.96
    91.5  1865.3    99.8 1865.32
#Mann= 3 ,-1,0
       0      .1       0    55.3    .045       0    70.4      .1       0
Bank Sta=55.3,70.4
XS Rating Curve= 0 ,0
Exp/Cntr(USF)=0,0
Exp/Cntr=0.3,0.1

Type RM Length L Ch R = 1 ,7928    ,42.3,41.5,41.4
XS GIS Cut Line= 3
2185265.56096182670913.224783768 2185300.1079965670973.682094454
2185307.81938817670988.796422125
#Sta/Elev= 24
       0 1870.73     4.6 1868.78     9.2 1865.58    13.3  1863.3    18.4    1861
      23 1858.63    25.3 1857.79    26.51857.482    27.6  1857.2    28.3 1857.13
    32.2 1856.92    41.4 1857.01      46 1857.45    48.8 1858.28    55.2 1860.49
    59.8  1861.6    64.4    1862    66.4 1862.29    69.6 1862.98    73.6 1863.45
    78.2 1863.78    81.2 1864.11    82.5 1864.33    86.6 1864.72
#Mann= 4 ,-1,0
       0     .05       0      20      .1       0    26.5    .045       0
      46      .1       0
Bank Sta=26.5,46
XS Rating Curve= 0 ,0
Exp/Cntr(USF)=0,0
Exp/Cntr=0.3,0.1

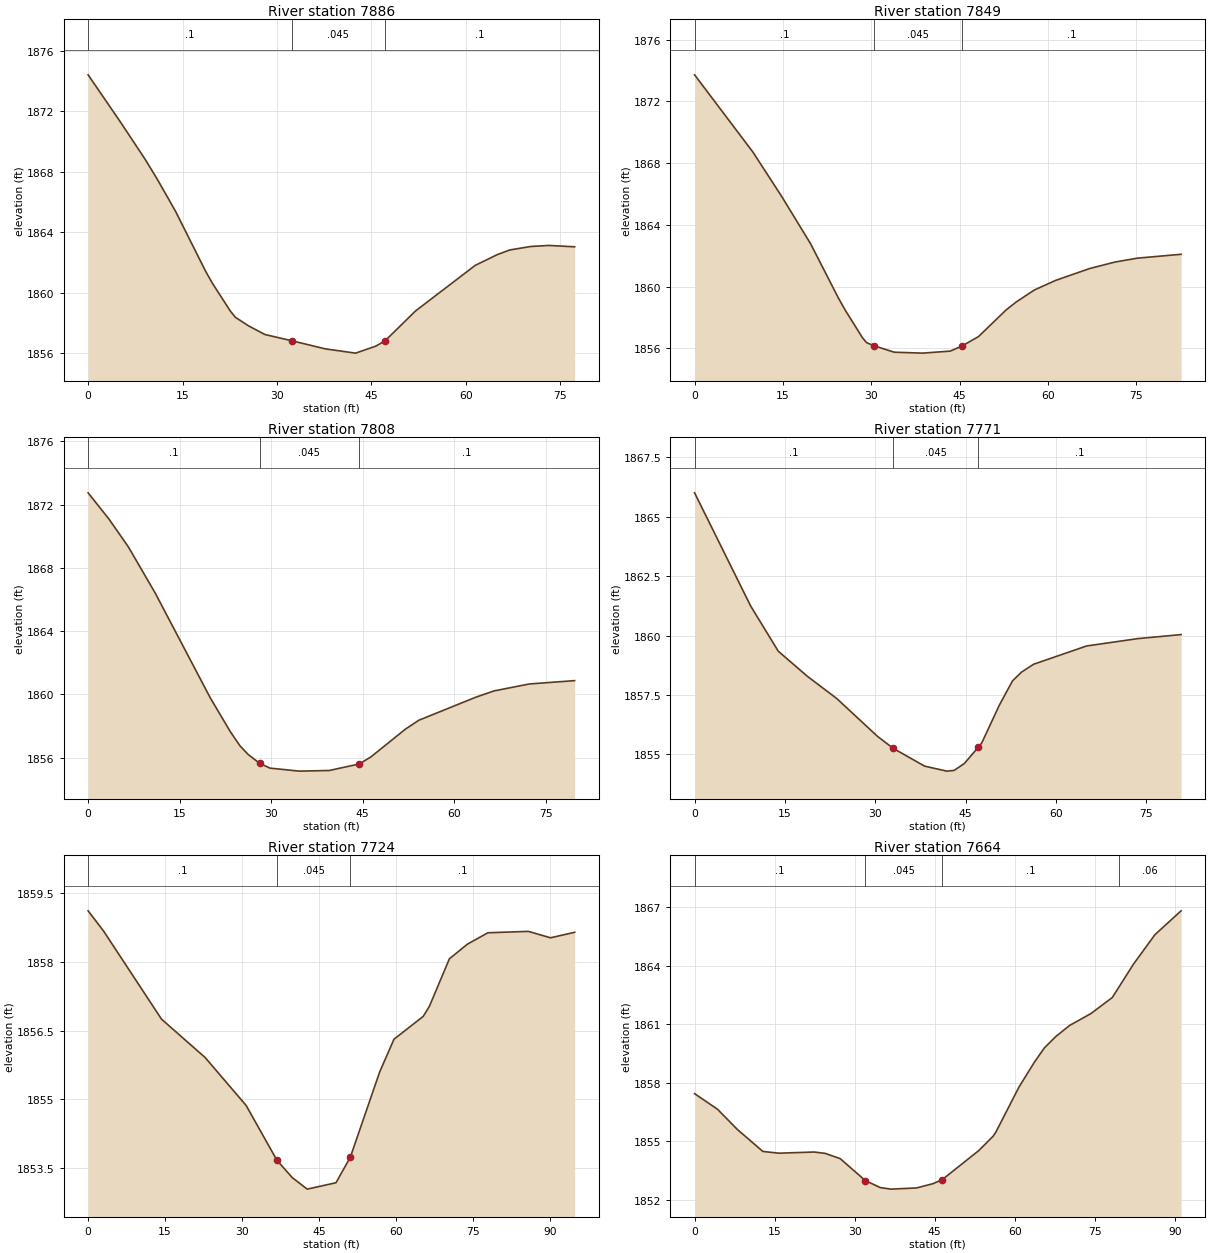
Type RM Length L Ch R = 1 ,7886    ,36.9,37.2,37.1
XS GIS Cut Line= 3
2185224.53635814670929.5729341072185259.39184849670983.244220123
2185269.57088549670991.880978793
#Sta/Elev= 23
       0 1874.42     5.2 1871.26     9.1 1868.81      11 1867.51    13.9 1865.39
    18.6 1861.49    19.7 1860.67    22.6  1858.8    23.4 1858.39    25.5 1857.82
    28.1 1857.25   32.321856.842    37.7  1856.3    42.5 1856.02    45.7 1856.48
    47.2 1856.84      52  1858.8    61.5 1861.82      65 1862.53      67 1862.84
    70.3 1863.07    73.2 1863.14    77.3 1863.05
#Mann= 3 ,-1,0
       0      .1       0   32.32    .045       0    47.2      .1       0
Bank Sta=32.32,47.2
XS Rating Curve= 0 ,0
Exp/Cntr(USF)=0,0
Exp/Cntr=0.3,0.1

Type RM Length L Ch R = 1 ,7849    ,41.7,41,40.5
XS GIS Cut Line= 4
2185192.76542447670949.005641113 2185204.4867398670965.970702785
2185226.38709214671000.2092817952185247.67053315671001.443104462
#Sta/Elev= 22
       0 1873.72     9.9 1868.72    14.8 1865.84    19.7 1862.78    24.4 1859.28
    25.6 1858.47    28.5  1856.7    29.2 1856.38   30.541856.167    33.9 1855.76
    38.7  1855.7    43.4 1855.83    45.4 1856.16    48.2 1856.77    52.9  1858.5
    54.6 1859.01    57.7 1859.79    61.3 1860.41    67.1 1861.18    71.4  1861.6
    75.2 1861.85    82.6  1862.1
#Mann= 3 ,-1,0
       0      .1       0   30.54    .045       0    45.4      .1       0
Bank Sta=30.54,45.4
XS Rating Curve= 0 ,0
Exp/Cntr(USF)=0,0
Exp/Cntr=0.3,0.1

Type RM Length L Ch R = 1 ,7808    ,37.8,37.6,37.7
XS GIS Cut Line= 4
2185158.71068428670967.2655837832185166.70585516670984.005472818
2185191.94061326671019.9837417892185206.93155867671028.478610852
#Sta/Elev= 20
       0 1872.74     3.4 1871.09     6.6 1869.32      11  1866.4      20 1859.79
    23.3 1857.64    24.9 1856.74    26.2 1856.21    28.1 1855.64    29.8 1855.34
    34.6 1855.15    39.5 1855.19    44.4  1855.6    46.3 1856.04      52 1857.81
    54.2 1858.37    63.5 1859.82    66.5 1860.22    72.3 1860.66    79.7 1860.87
#Mann= 3 ,-1,0
       0      .1       0    28.1    .045       0    44.4      .1       0
Bank Sta=28.1,44.4
XS Rating Curve= 0 ,0
Exp/Cntr(USF)=0,0
Exp/Cntr=0.3,0.1

Type RM Length L Ch R = 1 ,7771    ,50.3,47.2,44.8
XS GIS Cut Line= 4
2185126.22292802670989.1411365292185134.44841247671003.193005792
2185159.46759433671039.1795002482185179.00311989 671046.03407062
#Sta/Elev= 20
       0 1866.01     9.3 1861.25    13.9 1859.34    18.7 1858.29    23.6 1857.35
    30.4 1855.75      331855.248    38.2  1854.5    41.9 1854.29    43.1 1854.32
    44.8 1854.61    47.11855.291    47.7 1855.48    50.6 1857.06    52.8 1858.09
    54.3 1858.46    56.3 1858.79    65.1 1859.56    73.6 1859.87    80.8 1860.04
#Mann= 3 ,-1,0
       0      .1       0      33    .045       0    47.1      .1       0
Bank Sta=33,47.1
XS Rating Curve= 0 ,0
Exp/Cntr(USF)=0,0
Exp/Cntr=0.3,0.1

Type RM Length L Ch R = 1 ,7724    ,56.3,59.7,62.3
XS GIS Cut Line= 3
2185076.66815926671020.431789321 2185128.7121195671067.821411649
2185152.83005229671064.013316998
#Sta/Elev= 20
       0 1859.12       3 1858.68    14.3 1856.75    22.8 1855.91    30.8 1854.86
    36.8 1853.66    39.8 1853.28    42.7 1853.03    48.3 1853.17    51.1 1853.73
    56.8 1855.59    59.6 1856.31    65.3 1856.81    66.5 1857.03    70.4 1858.07
    73.9 1858.39    77.9 1858.64    85.8 1858.67    90.1 1858.53    94.8 1858.65
#Mann= 3 ,-1,0
       0      .1       0    36.8    .045       0    51.1      .1       0
Bank Sta=36.8,51.1
XS Rating Curve= 0 ,0
Exp/Cntr(USF)=0,0
Exp/Cntr=0.3,0.1

Type RM Length L Ch R = 1 ,7664    ,42.8,52.2,63.8
XS GIS Cut Line= 3
2185044.93403717671058.5127358352185083.43810531671116.480398861
2185082.59186205671138.059601886
#Sta/Elev= 27
       0 1857.44     4.3 1856.64       8 1855.61    12.8 1854.48    15.8 1854.39
    22.4 1854.45    24.5 1854.38    27.3 1854.11      32 1852.99    34.8 1852.63
    36.8 1852.55    41.6 1852.61    44.7 1852.83    46.4 1853.03    53.3 1854.53
      56 1855.27    56.5 1855.48    60.8 1857.77    63.7 1859.05    65.6 1859.79
    67.7 1860.36    70.3 1860.93    74.3 1861.54    78.3 1862.36    82.3 1864.08
    86.3 1865.58    91.2  1866.8
#Mann= 4 ,-1,0
       0      .1       0      32    .045       0    46.4      .1       0
   79.59     .06       0
Bank Sta=32,46.4
XS Rating Curve= 0 ,0
Exp/Cntr(USF)=0,0
Exp/Cntr=0.3,0.1

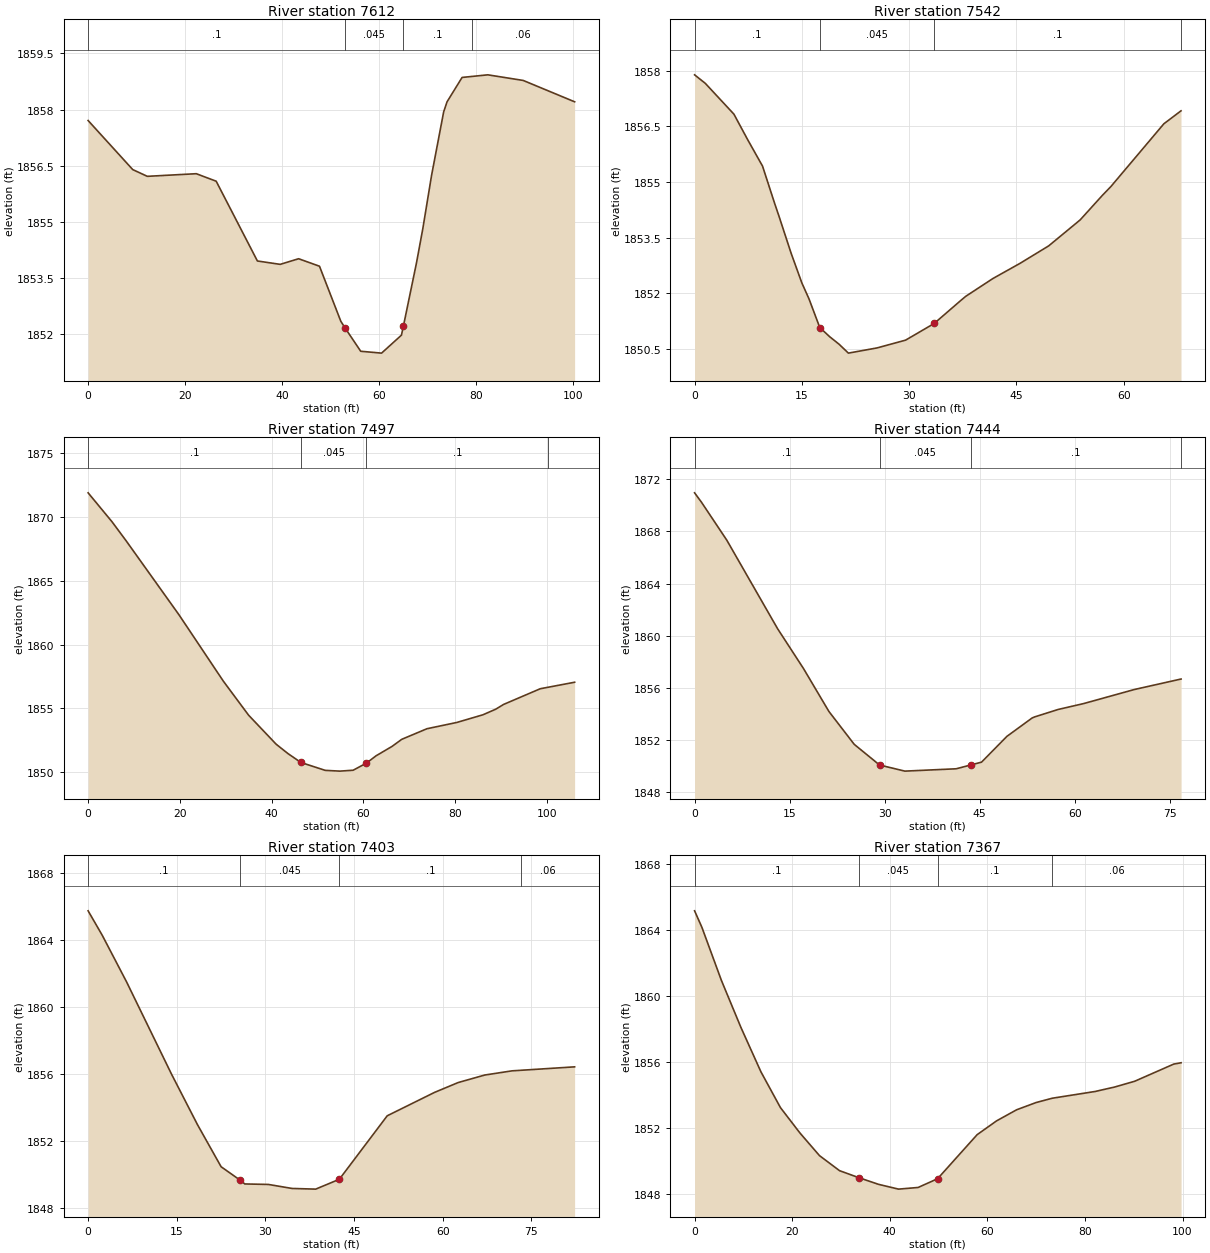
Type RM Length L Ch R = 1 ,7612    ,57.9,69.1,85.5
XS GIS Cut Line= 4
2185041.32072791671053.7897415922185030.54790182671073.321992812
2185011.08430693671126.6353179322185013.19991507671147.791399328
#Sta/Elev= 24
       0 1857.71     9.2  1856.4    12.2 1856.22    22.3 1856.29    26.4 1856.09
    34.9 1853.96    39.6 1853.87    43.4 1854.02    47.7 1853.82    52.1 1852.35
      531852.167    56.2 1851.55    60.5  1851.5    64.6 1851.98      65 1852.22
    67.7 1853.91      69 1854.82    70.8 1856.24    73.3 1857.94      74 1858.21
    77.1 1858.86    82.4 1858.93    89.7 1858.78   100.3 1858.21
#Mann= 4 ,-1,0
       0      .1       0      53    .045       0      65      .1       0
   79.06     .06       0
Bank Sta=53,65
XS Rating Curve= 0 ,0
Exp/Cntr(USF)=0,0
Exp/Cntr=0.3,0.1

Type RM Length L Ch R = 1 ,7542    ,57.1,45.4,36.1
XS GIS Cut Line= 2
2185041.64857989 671051.494777762184973.72833134671048.066965936
#Sta/Elev= 28
       0 1857.89     1.5 1857.66     5.5 1856.83     7.4 1856.15     9.5 1855.43
    11.2 1854.42    11.8 1854.08    13.5 1853.08      15 1852.28      16 1851.85
    17.5 1851.08    18.9 1850.83    20.2 1850.63    21.5 1850.39    25.5 1850.53
    29.5 1850.74    33.5 1851.19    37.1 1851.79    37.9 1851.92    41.7  1852.4
    45.5 1852.81    49.5 1853.28    53.9 1853.98      57 1854.64    57.5 1854.74
    58.2 1854.88    65.6 1856.57      68 1856.92
#Mann= 4 ,-1,0
       0      .1       0    17.5    .045       0    33.5      .1       0
   68.01     .06       0
Bank Sta=17.5,33.5
XS Rating Curve= 0 ,0
Exp/Cntr(USF)=0,0
Exp/Cntr=0.3,0.1

Type RM Length L Ch R = 1 ,7497    ,61.7,53.3,45.5
XS GIS Cut Line= 4
2185036.44765025670962.7275647992185027.53670876670985.690375547
2184981.95381579671032.9869111172184970.98650319671044.296952231
#Sta/Elev= 23
       0 1871.88     5.2 1869.62     8.3 1868.12    19.8 1862.34    29.5 1857.13
      35 1854.47      41  1852.2    43.6 1851.46    46.4 1850.77    51.7 1850.15
    54.9 1850.09    57.8 1850.16    60.71850.717    62.8 1851.29    66.3 1852.03
    68.4 1852.58    73.9 1853.41    80.4  1853.9    86.1  1854.5    88.9 1854.94
    90.6 1855.31    98.6 1856.54   106.1 1857.05
#Mann= 4 ,-1,0
       0      .1       0    46.4    .045       0    60.7      .1       0
  100.32     .06       0
Bank Sta=46.4,60.7
XS Rating Curve= 0 ,0
Exp/Cntr(USF)=0,0
Exp/Cntr=0.3,0.1

Type RM Length L Ch R = 1 ,7444    ,42.2,40.7,38.9
XS GIS Cut Line= 2
2184961.04737615670952.1029807222184953.50734874671028.531440375
#Sta/Elev= 19
       0 1870.97     1.1 1870.24     5.1 1867.32    13.1 1860.53    17.2 1857.46
    21.2 1854.17    25.2 1851.64    29.2 1850.05    33.2 1849.58    41.3 1849.76
   43.671850.062    45.3 1850.27    49.3 1852.25    53.3 1853.67    53.7 1853.75
    57.4 1854.32    61.4 1854.77    69.4 1855.85    76.8 1856.66
#Mann= 4 ,-1,0
       0      .1       0    29.2    .045       0   43.67      .1       0
    76.8     .06       0
Bank Sta=29.2,43.67
XS Rating Curve= 0 ,0
Exp/Cntr(USF)=0,0
Exp/Cntr=0.3,0.1

Type RM Length L Ch R = 1 ,7403    ,37.5,36.3,35.3
XS GIS Cut Line= 4
2184918.54903984670954.8448088712184916.49266873670965.469392948
2184918.20631132671017.9068562972184927.80270984671034.357825191
#Sta/Elev= 18
       0 1865.76     2.4 1864.29     6.5 1861.51    14.1 1855.99    18.5 1852.96
    22.5 1850.44    25.7 1849.64    26.5 1849.41    30.5 1849.38    34.5 1849.14
    38.5  1849.1    42.5 1849.69    50.6 1853.49    58.6 1854.89    62.6 1855.48
    67.1 1855.93    71.7 1856.18    82.3 1856.42
#Mann= 4 ,-1,0
       0      .1       0    25.7    .045       0    42.5      .1       0
   73.29     .06       0
Bank Sta=25.7,42.5
XS Rating Curve= 0 ,0
Exp/Cntr(USF)=0,0
Exp/Cntr=0.3,0.1

Type RM Length L Ch R = 1 ,7367    ,60.5,59,53.1
XS GIS Cut Line= 4
2184877.06459085670951.6532913642184877.68150219670963.991518034
2184885.39289385671024.4488287192184888.78590619671050.667560394
#Sta/Elev= 24
       0 1865.17     1.5 1864.17     5.5 1860.95     9.5  1858.1    13.6 1855.41
    17.6 1853.24    21.6  1851.7    25.6 1850.33    29.7 1849.42    33.7 1848.99
    37.7 1848.59    41.8  1848.3    45.8  1848.4    49.8 1848.93    57.9  1851.6
    61.9 1852.44      66 1853.11      70 1853.55    73.3 1853.81    82.1 1854.22
    86.1 1854.49    90.2 1854.84    98.2 1855.88    99.7 1855.96
#Mann= 4 ,-1,0
       0      .1       0    33.7    .045       0    49.8      .1       0
    73.3     .06       0
Bank Sta=33.7,49.8
XS Rating Curve= 0 ,0
Exp/Cntr(USF)=0,0
Exp/Cntr=0.3,0.1

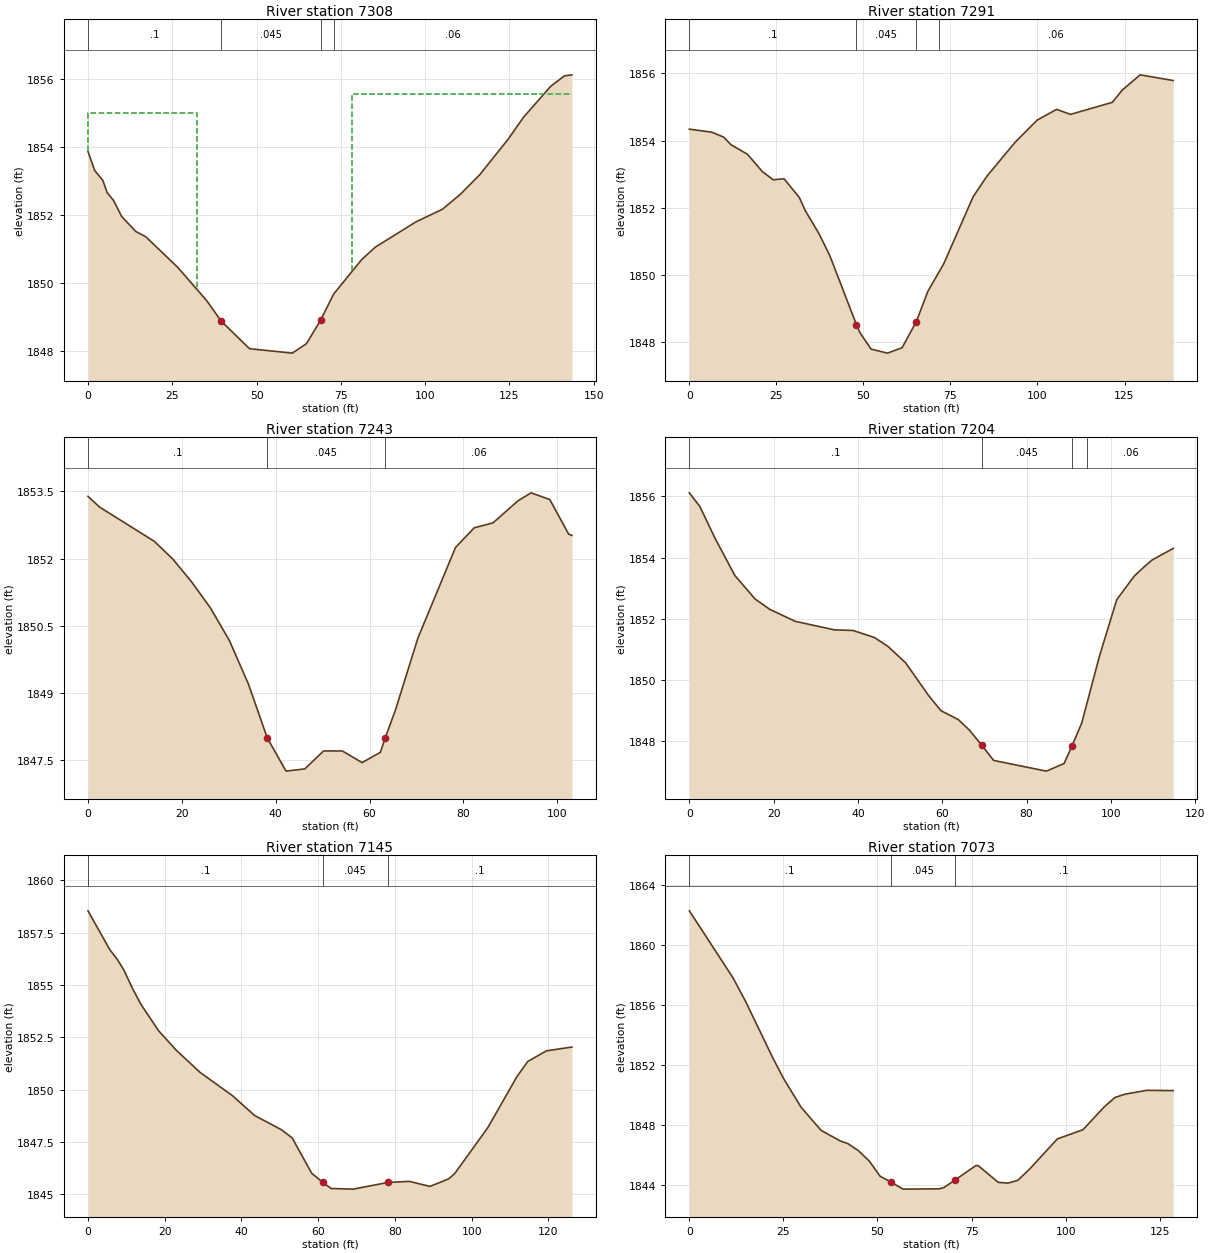
Type RM Length L Ch R = 1 ,7308    ,16.6,16.8,17.6
XS GIS Cut Line= 3
2184812.01104857670955.7288814552184835.08409105671024.926574423
2184832.03880562671095.406032184
#Sta/Elev= 27
       0 1853.87       2 1853.31     4.4 1853.02     5.7 1852.66     7.6 1852.43
      10 1851.96    14.2 1851.52    17.1 1851.37    26.6 1850.47    35.3 1849.48
    39.5 1848.89    47.9 1848.08    60.6 1847.95    64.8 1848.23      69 1848.92
    72.9 1849.69    81.2  1850.7    85.2 1851.06    97.2  1851.8   105.2 1852.18
   110.5 1852.62   116.2 1853.19   124.6 1854.23   129.2 1854.88   137.3 1855.79
   141.3 1856.09   143.5 1856.12
#Mann= 4 ,-1,0
       0      .1       0    39.5    .045       0      69      .1       0
   72.94     .06       0
#XS Ineff= 2 , 0
           32.21    1855   78.33         1855.55
Permanent Ineff=
       F       F
Bank Sta=39.5,69
XS Rating Curve= 0 ,0
Exp/Cntr(USF)=0,0
Exp/Cntr=0.3,0.1

Type RM Length L Ch R = 1 ,7291    ,42.8,47.9,52.5
XS GIS Cut Line= 4
2184793.67577802670960.1011382772184809.94245394670998.558192903
2184818.21683244671028.7878825432184817.04149459671094.653815956
#Sta/Elev= 30
       0 1854.34     6.4 1854.25     9.9  1854.1    11.9 1853.88    16.7 1853.59
      21 1853.07    24.1 1852.83    27.2 1852.86    31.6  1852.3    33.3 1851.91
    37.2 1851.23    40.3 1850.58      48 1848.51      49 1848.27    52.2 1847.78
    56.9 1847.66    61.1 1847.82    65.2  1848.6    68.5  1849.5    73.1 1850.33
    81.5 1852.32    85.5 1852.94    93.5 1853.94    99.9 1854.61   105.5 1854.93
   109.5 1854.78   121.5 1855.14   124.4 1855.51   129.5 1855.96     139 1855.79
#Mann= 4 ,-1,0
       0      .1       0      48    .045       0    65.2      .1       0
   71.76     .06       0
Bank Sta=48,65.2
XS Rating Curve= 0 ,0
Exp/Cntr(USF)=0,0
Exp/Cntr=0.3,0.1

Type RM Length L Ch R = 1 ,7243    ,35.6,39.3,41.8
XS GIS Cut Line= 3
2184772.79294524670967.1299891422184765.55756541671055.477785054
2184764.79594648671069.948544729
#Sta/Elev= 26
       0 1853.39     2.5 1853.15    14.1 1852.39    18.1 1851.99    22.1 1851.48
    26.1  1850.9    30.1 1850.18    34.2  1849.2    38.2    1848    42.2 1847.26
    46.2 1847.31    50.2 1847.71    54.2 1847.71    58.4 1847.45    62.3 1847.68
    63.31847.993    65.5 1848.62    70.3 1850.23    78.3 1852.25    82.3 1852.69
    86.3  1852.8    91.6 1853.29    94.4 1853.47    98.4 1853.32   102.4 1852.55
   103.1 1852.52
#Mann= 3 ,-1,0
       0      .1       0    38.2    .045       0    63.3     .06       0
Bank Sta=38.2,63.3
XS Rating Curve= 0 ,0
Exp/Cntr(USF)=0,0
Exp/Cntr=0.3,0.1

Type RM Length L Ch R = 1 ,7204    ,48.2,58.9,62.4
XS GIS Cut Line= 3
2184762.51108968670940.0925171182184743.85142589670969.034036468
2184720.62204852671045.957548425
#Sta/Elev= 28
       0 1856.12     2.5 1855.67     6.1 1854.63    10.8 1853.41    15.6 1852.64
    19.1  1852.3    25.1 1851.91    34.4 1851.63    38.8 1851.61    43.9 1851.38
    47.1 1851.09    51.3 1850.55    56.8 1849.47    59.7 1848.98    63.8 1848.69
    66.4 1848.35    69.41847.843    72.2 1847.35    84.7    1847    88.9 1847.25
    90.8 1847.83    93.1 1848.58    97.3 1850.77   101.4 1852.62   105.6  1853.4
   108.1 1853.72   109.8 1853.92   114.8  1854.3
#Mann= 4 ,-1,0
       0      .1       0    69.4    .045       0    90.8      .1       0
   94.44     .06       0
Bank Sta=69.4,90.8
XS Rating Curve= 0 ,0
Exp/Cntr(USF)=0,0
Exp/Cntr=0.3,0.1

Type RM Length L Ch R = 1 ,7145    ,70.9,71.9,72.1
XS GIS Cut Line= 3
2184735.85442713670913.0550450932184723.28771478670935.903613001
2184661.21577196671014.350362819
#Sta/Elev= 27
       0 1858.55     5.7 1856.69     7.6 1856.24     9.3 1855.74    11.6 1854.84
    13.8 1854.08    18.4 1852.82      23 1851.89    29.2 1850.83    37.7 1849.71
    43.4 1848.77    50.4 1848.09    53.2  1847.7    58.3 1846.01    61.21845.568
    63.4 1845.28    69.1 1845.25    78.11845.568    83.8 1845.62    89.1 1845.38
      94 1845.74    95.6    1846   104.2 1848.19   111.8 1850.63   114.6 1851.35
   119.5 1851.86   126.1 1852.04
#Mann= 3 ,-1,0
       0      .1       0    61.2    .045       0    78.1      .1       0
Bank Sta=61.2,78.1
XS Rating Curve= 0 ,0
Exp/Cntr(USF)=0,0
Exp/Cntr=0.3,0.1

Type RM Length L Ch R = 1 ,7073    ,80.3,81.9,83.5
XS GIS Cut Line= 3
 2184682.6164397670872.821577069 2184669.2911549670892.809504275
2184601.83190058670972.761213099
#Sta/Elev= 30
       0 1862.28    11.6 1857.81    14.9 1856.26    22.2 1852.46    25.1 1851.07
    29.7 1849.18      35 1847.64    40.2 1846.92    42.1 1846.76    44.9 1846.29
    47.8  1845.6    50.7 1844.58    53.5  1844.2    56.8 1843.72    66.4 1843.74
    67.7 1843.83    70.5 1844.31    76.2  1845.3    76.8 1845.28    82.1 1844.17
    84.7 1844.12    87.3 1844.31    90.4 1845.05    97.8 1847.07   104.6 1847.68
   110.2 1849.19   113.1 1849.83   115.9 1850.06   121.6 1850.31   128.6 1850.29
#Mann= 3 ,-1,0
       0      .1       0    53.5    .045       0    70.5      .1       0
Bank Sta=53.5,70.5
XS Rating Curve= 0 ,0
Exp/Cntr(USF)=0,0
Exp/Cntr=0.3,0.1

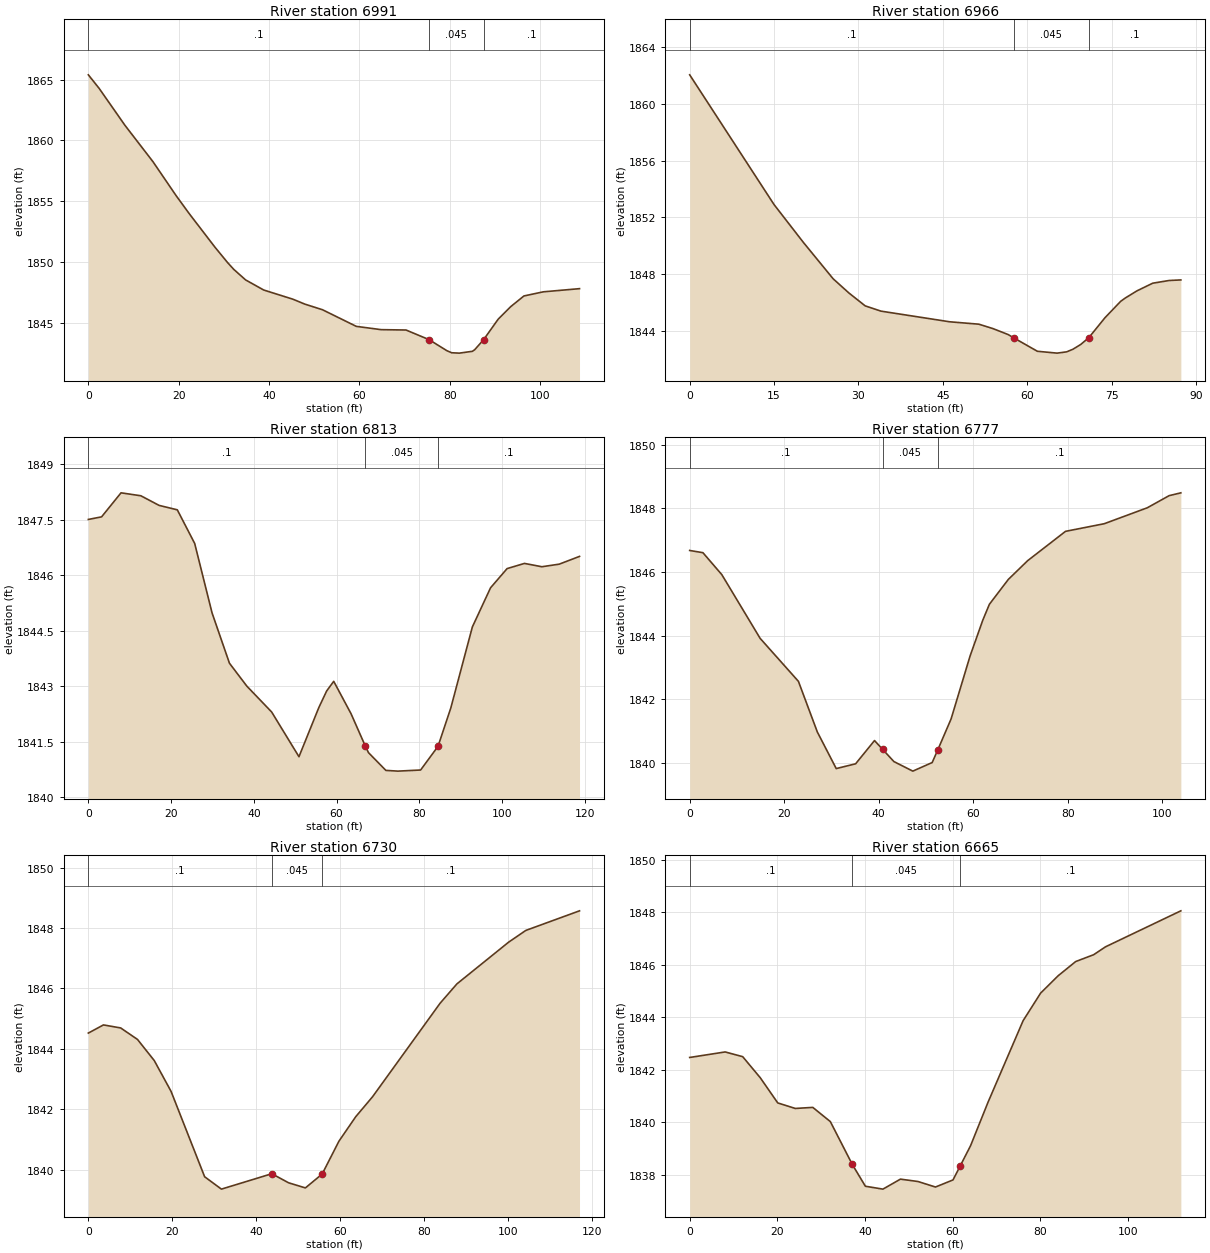
Type RM Length L Ch R = 1 ,6991    ,25.7,25.2,24.9
XS GIS Cut Line= 3
2184634.03467219670835.6218236582184623.20787828670847.003837761
2184549.91881186670904.191518379
#Sta/Elev= 29
       0 1865.39     2.4 1864.27     8.1 1861.24    14.3 1858.25    19.4 1855.47
    22.3 1853.99      28 1851.23    30.8 1849.96    32.2 1849.39    34.8 1848.53
    38.8  1847.7    45.3 1846.94    47.9 1846.54    51.8 1846.08    59.3 1844.71
    64.8 1844.44    70.3 1844.41    75.4 1843.62    79.3 1842.72    80.4 1842.54
    82.1 1842.51      85 1842.66    85.5 1842.79   87.461843.608    90.7  1845.3
    93.5 1846.34    96.4 1847.21   100.7 1847.55   108.7 1847.81
#Mann= 3 ,-1,0
       0      .1       0    75.4    .045       0   87.46      .1       0
Bank Sta=75.4,87.46
XS Rating Curve= 0 ,0
Exp/Cntr(USF)=0,0
Exp/Cntr=0.3,0.1

Type RM Length L Ch R = 1 ,6966    ,176.9,153,120.9
XS GIS Cut Line= 3
2184604.43584666670821.5564783452184588.82265859670840.596951602
2184540.49713786670880.568269715
#Sta/Elev= 25
       0 1862.04      15 1852.89    20.2 1850.23    25.5 1847.66    28.3 1846.66
    31.2 1845.75      34 1845.38    46.2 1844.63    51.4 1844.46    53.9 1844.15
    56.6 1843.73    57.61843.497    61.8 1842.55    65.3 1842.42      67 1842.51
    68.1 1842.69    69.5 1843.03   70.951843.513    73.8 1844.91    76.6 1846.07
    77.4  1846.3    79.5 1846.81    82.3 1847.35    85.2 1847.54    87.3 1847.58
#Mann= 3 ,-1,0
       0      .1       0    57.6    .045       0   70.95      .1       0
Bank Sta=57.6,70.95
XS Rating Curve= 0 ,0
Exp/Cntr(USF)=0,0
Exp/Cntr=0.3,0.1

Type RM Length L Ch R = 1 ,6813    ,37.6,35.8,34.4
XS GIS Cut Line= 3
2184405.47574284670843.8747326622184419.94514798 670853.01327447
 2184516.8443841670883.554581972
#Sta/Elev= 30
       0 1847.51     3.2 1847.58     7.9 1848.23    12.7 1848.15    17.1 1847.89
    21.5 1847.77    25.7 1846.86    29.9 1844.98    34.1 1843.62    38.3    1843
    44.3  1842.3    50.9 1841.09    55.7 1842.42    57.6 1842.87    59.3 1843.13
    63.5 1842.25    66.91841.387    67.7  1841.2    71.9 1840.72    74.8  1840.7
    80.3 1840.73    84.5 1841.37    87.6 1842.41    92.8  1844.6    97.2 1845.66
   101.2 1846.18   105.4 1846.32   109.6 1846.23   113.8  1846.3   118.7 1846.51
#Mann= 3 ,-1,0
       0      .1       0    66.9    .045       0    84.5      .1       0
Bank Sta=66.9,84.5
XS Rating Curve= 0 ,0
Exp/Cntr(USF)=0,0
Exp/Cntr=0.3,0.1

Type RM Length L Ch R = 1 ,6777    ,48.3,47.3,46.2
XS GIS Cut Line= 3
 2184417.4531137670897.6445321822184503.89686229670910.211244531
2184518.36762196670918.208243299
#Sta/Elev= 25
       0 1846.68     2.8 1846.61     6.8 1845.92    14.9 1843.92      23 1842.57
      27 1840.98      31 1839.83    35.1 1839.98    39.1 1840.71    40.81840.436
    43.2 1840.05    47.2 1839.75    51.3 1840.02    52.51840.424    55.3 1841.39
    59.3 1843.36      62 1844.49    63.4 1844.99    67.4 1845.77    71.5 1846.36
    79.5 1847.28    87.7 1847.52    96.8 1848.02   101.4  1848.4   103.9 1848.49
#Mann= 3 ,-1,0
       0      .1       0    40.8    .045       0    52.5      .1       0
Bank Sta=40.8,52.5
XS Rating Curve= 0 ,0
Exp/Cntr(USF)=0,0
Exp/Cntr=0.3,0.1

Type RM Length L Ch R = 1 ,6730    ,65.3,64.5,64.2
XS GIS Cut Line= 3
2184408.53091202670948.4607787152184500.99082331670953.162130136
2184524.49758041670946.371289194
#Sta/Elev= 20
       0 1844.52     3.6 1844.79     7.7 1844.69    11.7 1844.31    15.7 1843.61
    19.7 1842.59    27.7 1839.76    31.7 1839.35    43.7 1839.86    47.7 1839.56
    51.7 1839.39    55.7 1839.85    59.7 1840.94    63.7 1841.75    67.7 1842.41
    83.8 1845.51    87.8 1846.15   100.1 1847.53   104.2 1847.92     117 1848.57
#Mann= 3 ,-1,0
       0      .1       0    43.7    .045       0    55.7      .1       0
Bank Sta=43.7,55.7
XS Rating Curve= 0 ,0
Exp/Cntr(USF)=0,0
Exp/Cntr=0.3,0.1

Type RM Length L Ch R = 1 ,6665    ,56.3,59,62
XS GIS Cut Line= 3
2184404.12013667671014.2796986152184496.28947189671015.324443375
2184510.91589853671028.906125259
#Sta/Elev= 25
       0 1842.47     8.1 1842.68    12.1  1842.5    16.1  1841.7    20.1 1840.74
    24.1 1840.53    28.1 1840.57    32.1 1840.03    37.11838.403    40.1 1837.57
    44.1 1837.46    48.1 1837.84    52.1 1837.75    56.1 1837.54    60.1 1837.81
    61.7 1838.33    64.1 1839.11    68.1 1840.77    76.1 1843.87    80.1 1844.92
    84.1 1845.58    88.1 1846.12    92.2 1846.38    94.9 1846.68   112.1 1848.05
#Mann= 3 ,-1,0
       0      .1       0    37.1    .045       0    61.7      .1       0
Bank Sta=37.1,61.7
XS Rating Curve= 0 ,0
Exp/Cntr(USF)=0,0
Exp/Cntr=0.3,0.1