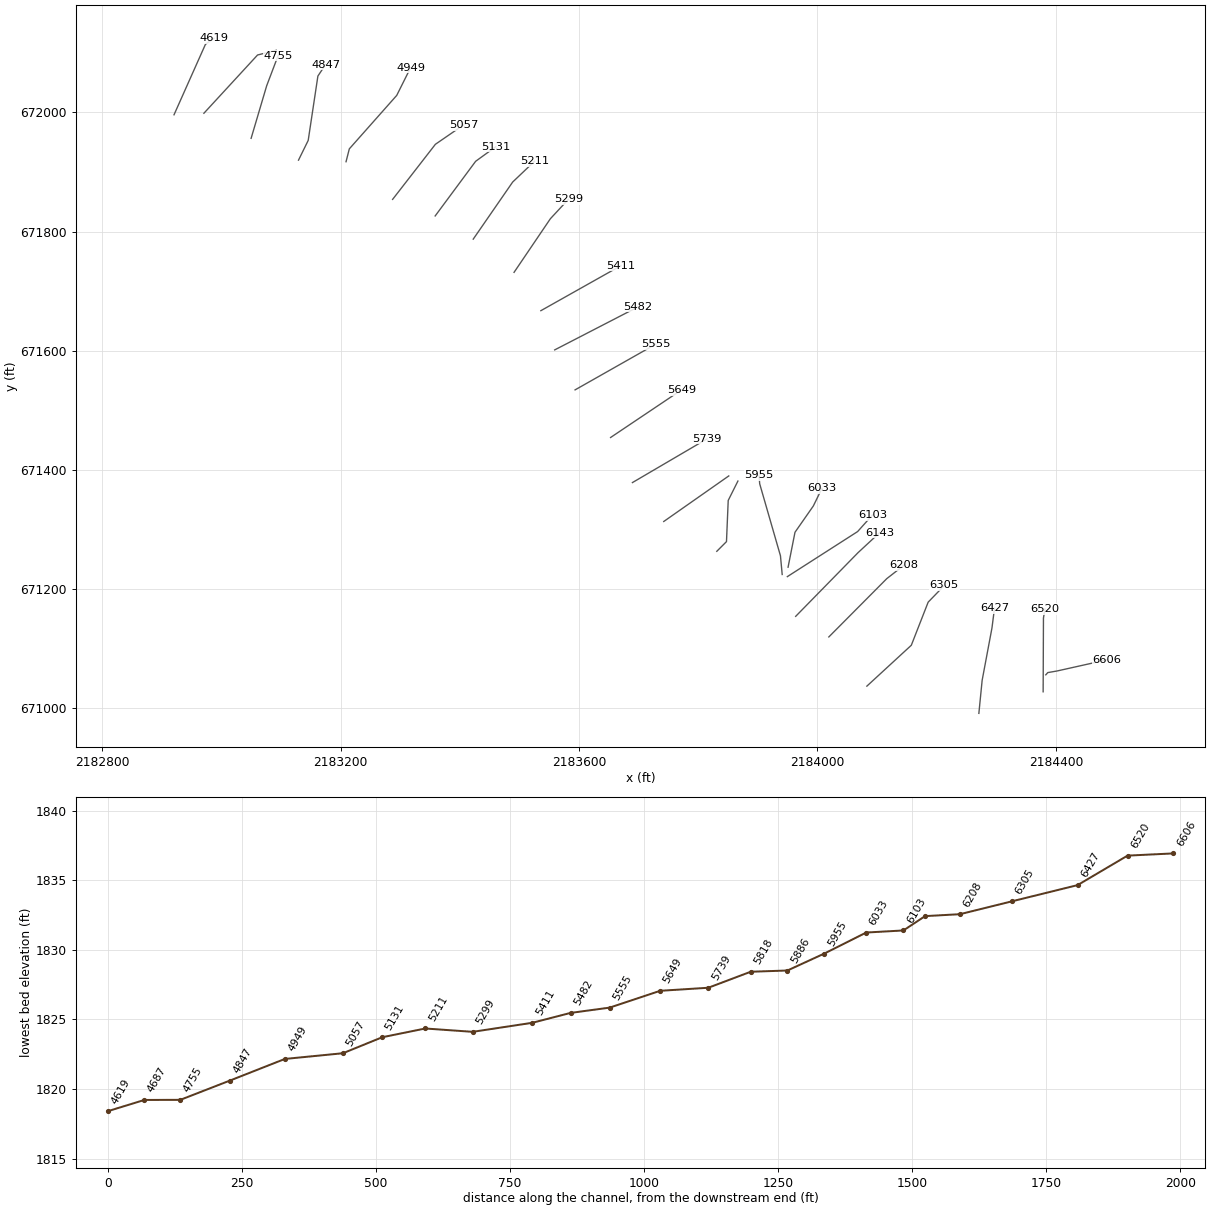
HEC-RAS study QUEENSFK.prj: QUEENSFK

--- QUEENSFK.g01 (geometry) --- (continued)

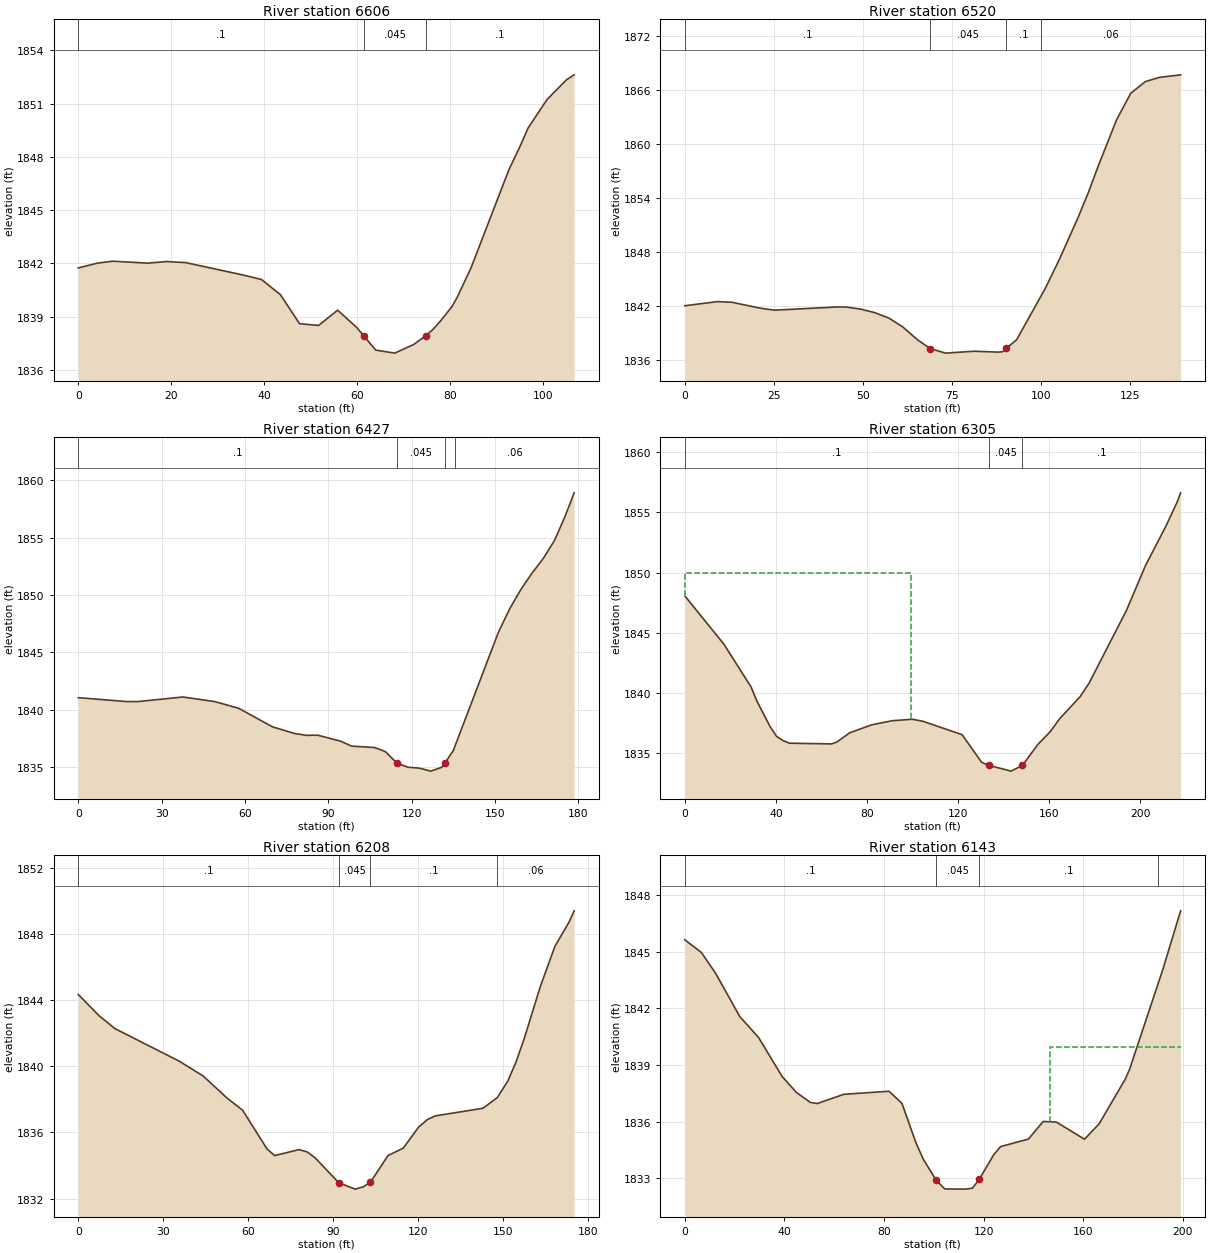
Type RM Length L Ch R = 1 ,6606    ,68.1,85.6,102.8
XS GIS Cut Line= 4
2184383.06941192671056.4914888812184386.44730199671060.226444639
2184401.96293049671062.9248148122184485.84202428671081.665735655
#Sta/Elev= 29
       0 1841.74     4.1 1842.01     7.4 1842.12    14.9 1842.01      19  1842.1
    23.1 1842.04    35.3 1841.35    39.4 1841.09    43.5 1840.23    47.6  1838.6
    51.7  1838.5    55.8 1839.36    59.9 1838.39    61.4 1837.92      64 1837.11
    68.1 1836.94    72.2 1837.43    74.8 1837.93    76.3 1838.27    78.1  1838.8
    80.4 1839.56    81.5 1840.07    84.5 1841.74    92.7  1847.3    94.9  1848.5
    96.8 1849.63   100.9 1851.24     105 1852.33   106.7 1852.62
#Mann= 3 ,-1,0
       0      .1       0    61.4    .045       0    74.8      .1       0
Bank Sta=61.4,74.8
XS Rating Curve= 0 ,0
Exp/Cntr(USF)=0,0
Exp/Cntr=0.3,0.1

Type RM Length L Ch R = 1 ,6520    ,95.2,93.1,90.1
XS GIS Cut Line= 3
2184378.62065318671028.0066685352184379.14302556671151.808922632
2184381.75488746671166.957721657
#Sta/Elev= 30
       0 1842.04     9.2  1842.5    13.2 1842.43    21.2 1841.77    25.2 1841.55
    42.5  1841.9    45.2  1841.9    49.2 1841.68    53.2 1841.29    57.2 1840.69
    61.2 1839.69    65.2  1838.3    68.91837.282    73.2 1836.78    81.2 1836.99
      88 1836.89    89.2 1836.93    90.3 1837.32    93.2 1838.28     100 1843.12
   101.2 1843.96   105.2 1847.22   110.3 1851.74   113.2 1854.51   116.1 1857.58
   121.2 1862.67   125.2 1865.63   129.3 1866.93   133.3  1867.4   139.2 1867.68
#Mann= 4 ,-1,0
       0      .1       0    68.9    .045       0    90.3      .1       0
     100     .06       0
Bank Sta=68.9,90.3
XS Rating Curve= 0 ,0
Exp/Cntr(USF)=0,0
Exp/Cntr=0.3,0.1

Type RM Length L Ch R = 1 ,6427    ,124,121.8,119.2
XS GIS Cut Line= 4
2184270.78433766670991.8056170052184276.28491883671047.234550264
2184292.78666232671135.2438488732184297.01787859671168.247335851
#Sta/Elev= 30
       0 1841.06    17.5 1840.72    21.5 1840.72    37.6 1841.12    49.1 1840.72
    57.7 1840.14    69.9 1838.52      78 1837.93    82.1 1837.78    86.2 1837.79
    94.3 1837.28    98.4 1836.84   106.5 1836.72   108.7 1836.54   110.6 1836.35
   114.7 1835.35   118.7    1835   122.8 1834.92   126.9 1834.66   130.9    1835
  131.971835.357     135 1836.46   151.2 1846.74   155.3 1848.81   159.3 1850.48
   163.3  1851.9   167.4  1853.2   171.4 1854.75     175 1856.73   178.5 1858.91
#Mann= 4 ,-1,0
       0      .1       0   114.7    .045       0  131.97      .1       0
   135.7     .06       0
Bank Sta=114.7,131.97
XS Rating Curve= 0 ,0
Exp/Cntr(USF)=0,0
Exp/Cntr=0.3,0.1

Type RM Length L Ch R = 1 ,6305    ,101.3,97.4,92.3
XS GIS Cut Line= 4
2184082.91833486671037.502752822 2184157.4723657 671106.09076871
2184185.73689045671178.4022549222184212.81667464671206.328282365
#Sta/Elev= 30
       0 1848.06    17.2 1844.04    29.1  1840.5    31.8 1839.27    37.5 1837.19
    40.3 1836.39    43.1 1836.04      46 1835.82    64.5 1835.76    66.9 1835.93
    72.4 1836.68    82.2 1837.35    91.2 1837.69     100 1837.81   104.6 1837.64
   121.8 1836.53   130.4 1834.23   133.6 1833.98   143.3  1833.5  148.271833.968
   155.2 1835.74   160.5 1836.77   164.7 1837.86   173.7  1839.7   177.6 1840.81
     194 1846.85   202.4 1850.59   211.2  1853.8   216.2 1855.82   217.8 1856.62
#Mann= 3 ,-1,0
       0      .1       0   133.6    .045       0  148.27      .1       0
#XS Ineff= 2 , 0
           99.21 1849.97
Permanent Ineff=
       F       F
Bank Sta=133.6,148.27
XS Rating Curve= 0 ,0
Exp/Cntr(USF)=0,0
Exp/Cntr=0.3,0.1

Type RM Length L Ch R = 1 ,6208    ,65.2,65.2,65.1
XS GIS Cut Line= 3
2184019.10233585671120.0295019282184116.28867244671217.822312846
2184145.61100126671240.670880754
#Sta/Elev= 30
       0 1844.34     7.3 1843.06    12.9 1842.28    35.6 1840.31      44 1839.42
    52.4 1838.09      58 1837.34    66.6    1835    69.3  1834.6    77.9 1834.96
    80.8 1834.82    83.6 1834.46    91.9 1832.96    97.7 1832.57   100.6 1832.71
   103.1 1832.99   109.3  1834.6   114.7 1835.05     120  1836.3   123.2 1836.78
     126    1837   142.8 1837.46   147.9 1838.11   151.6 1839.11   154.4 1840.22
   157.3 1841.63     163 1844.79   168.2 1847.25   173.2 1848.72     175  1849.4
#Mann= 4 ,-1,0
       0      .1       0    91.9    .045       0   103.1      .1       0
  147.87     .06       0
Bank Sta=91.9,103.1
XS Rating Curve= 0 ,0
Exp/Cntr(USF)=0,0
Exp/Cntr=0.3,0.1

Type RM Length L Ch R = 1 ,6143    ,42.9,40.3,36.8
XS GIS Cut Line= 3
2183963.48534854671154.5750321732184068.30667983671261.615401336
2184104.48357902671295.126634268
#Sta/Elev= 30
       0 1845.63     6.7 1844.95    12.4 1843.85    22.1 1841.56    29.6 1840.46
    39.1 1838.39    44.8 1837.55    50.4 1837.02    53.2 1836.96    63.9 1837.45
      82 1837.61    87.2 1836.97    92.8 1834.89    95.7 1834.03     101 1832.89
   104.4 1832.44   112.6 1832.43   115.5 1832.48   118.3 1832.96     124 1834.24
   126.8 1834.68     138 1835.08   143.9 1836.01   149.2 1835.98   160.5 1835.07
   166.4 1835.89   176.9 1838.26   178.6 1838.77   191.9 1844.03   199.1 1847.16
#Mann= 4 ,-1,0
       0      .1       0     101    .045       0   118.3      .1       0
  189.82     .06       0
#XS Ineff= 2 , 0
                          146.54         1839.94
Permanent Ineff=
       F       F
Bank Sta=101,118.3
XS Rating Curve= 0 ,0
Exp/Cntr(USF)=0,0
Exp/Cntr=0.3,0.1

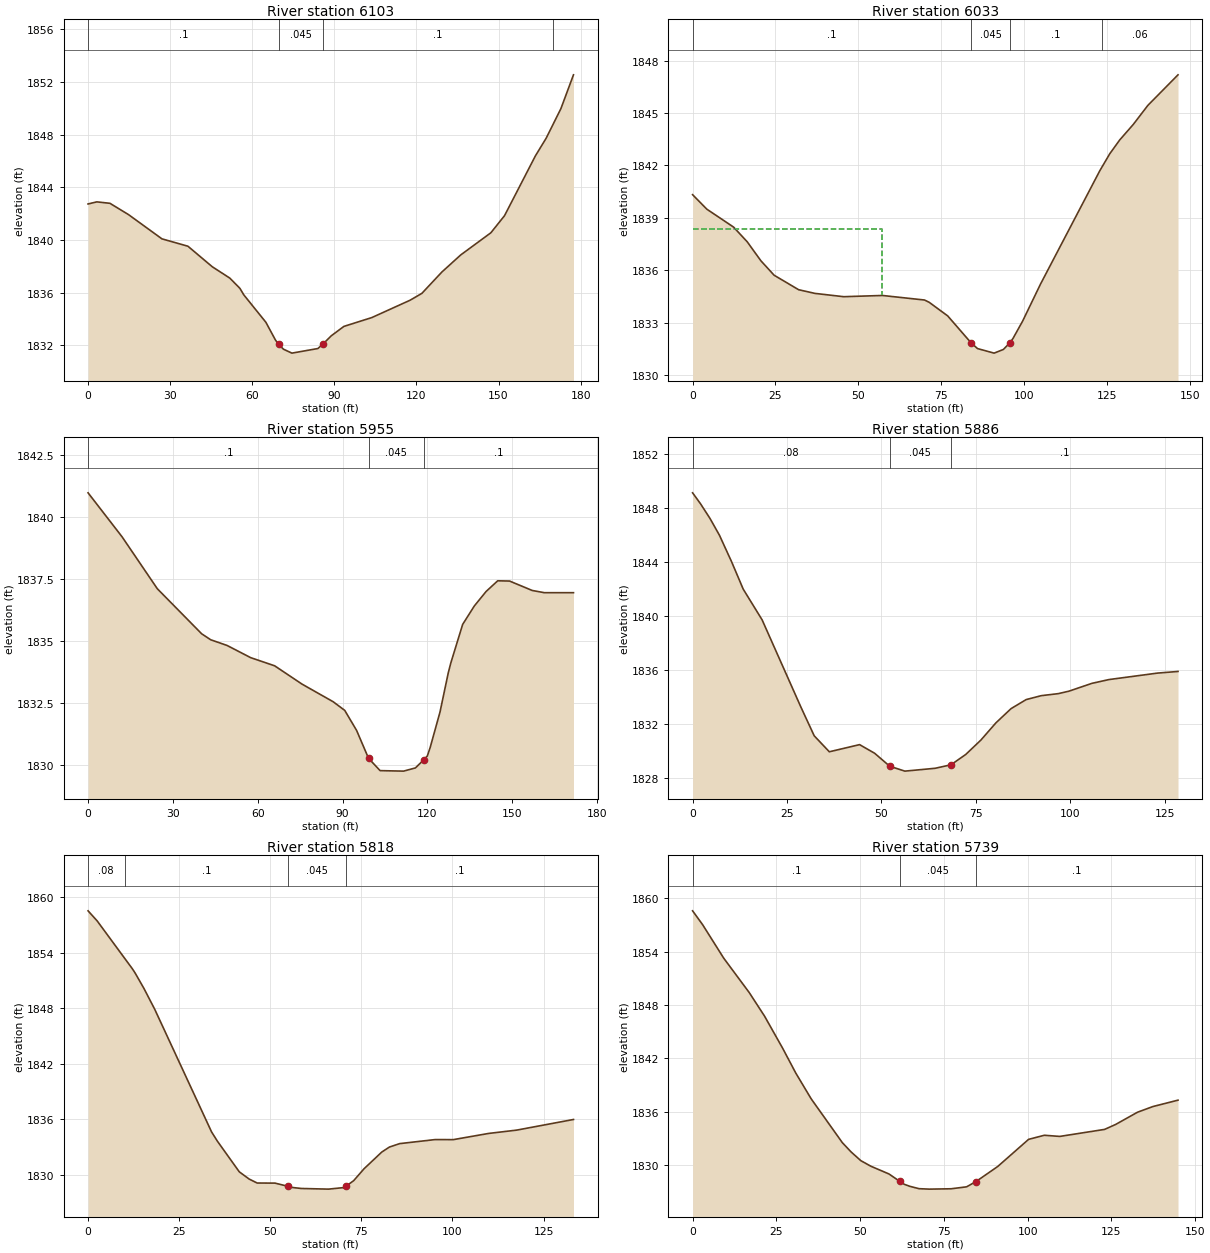
Type RM Length L Ch R = 1 ,6103    ,64.2,69.3,72.6
XS GIS Cut Line= 3
2183949.48080137671221.2094355862184067.37717138671296.784894982
2184092.33496287671324.644755257
#Sta/Elev= 30
       0 1842.73     3.2 1842.89       8 1842.78    14.8 1841.92      27 1840.08
    36.5 1839.52    45.4 1837.96    51.8  1837.1    55.5 1836.32    56.9 1835.83
      65 1833.74    68.5 1832.39    69.7 1832.06    71.4  1831.7    74.5  1831.4
      84 1831.75    85.9  1832.1    88.9 1832.72    93.5 1833.43   103.7  1834.1
   117.7 1835.42     122 1835.94   129.3 1837.56   136.2 1838.86   147.2 1840.54
   152.2 1841.84   163.5 1846.39   167.4 1847.72   172.8 1849.97   177.4 1852.54
#Mann= 4 ,-1,0
       0      .1       0    69.7    .045       0    85.9      .1       0
  170.04     .06       0
Bank Sta=69.7,85.9
XS Rating Curve= 0 ,0
Exp/Cntr(USF)=0,0
Exp/Cntr=0.3,0.1

Type RM Length L Ch R = 1 ,6033    ,63.3,78.1,86.6
XS GIS Cut Line= 4
2183950.71400648671237.0022781422183962.32228159671295.624067471
2183993.08421064671339.7355129062184007.59455454671369.336614448
#Sta/Elev= 27
       0 1840.32     4.3 1839.49    12.4 1838.46    16.5 1837.62    20.6 1836.54
    24.6 1835.71      32 1834.88    36.9 1834.67    45.6 1834.48    57.3 1834.55
      70 1834.29    71.4 1834.16      77 1833.38      84 1831.85      86 1831.51
      91 1831.25    93.8 1831.46    95.8 1831.85    96.7 1832.09    99.6 1833.08
     105  1835.2   122.9 1841.69   125.9 1842.66   128.9 1843.45     133 1844.34
   137.4 1845.43   146.5 1847.18
#Mann= 4 ,-1,0
       0      .1       0      84    .045       0    95.8      .1       0
  123.54     .06       0
#XS Ineff= 2 , 0
            57.2 1838.37
Permanent Ineff=
       F       F
Bank Sta=84,95.8
XS Rating Curve= 0 ,0
Exp/Cntr(USF)=0,0
Exp/Cntr=0.3,0.1

Type RM Length L Ch R = 1 ,5955    ,73.9,68.9,65.2
XS GIS Cut Line= 4
2183940.84697263671224.8135892722183937.94490385671256.155932081
2183903.12007851671376.8819932732183901.95925099671391.392337166
#Sta/Elev= 30
       0 1840.97      12  1839.2    24.5  1837.1    40.2 1835.28    43.4 1835.04
    49.2 1834.81    57.5 1834.32      66 1833.99    75.7 1833.25    86.7 1832.54
    90.8 1832.19      95 1831.38    99.2 1830.26   103.3 1829.76   111.6 1829.74
   115.8 1829.87   118.81830.205     120 1830.35     121 1830.69   124.5 1832.13
   127.4  1833.7   128.3  1834.1   132.5 1835.66   136.6  1836.4   140.8 1836.99
   144.9 1837.42   149.1 1837.41   157.1 1837.03   161.4 1836.94   171.7 1836.94
#Mann= 3 ,-1,0
       0      .1       0    99.2    .045       0   118.8      .1       0
Bank Sta=99.2,118.8
XS Rating Curve= 0 ,0
Exp/Cntr(USF)=0,0
Exp/Cntr=0.3,0.1

Type RM Length L Ch R = 1 ,5886    ,80,68.5,56
XS GIS Cut Line= 4
2183831.14877279671263.7013109052183847.40035796671279.952896066
2183850.30242673671349.0221329982183866.55401189671381.525303319
#Sta/Elev= 28
       0  1849.1     2.1 1848.29     4.6 1847.21     7.1 1845.97    10.3 1844.02
    13.4 1841.98    18.4 1839.71    28.7 1833.24    32.2 1831.13    36.2 1829.95
    44.2 1830.48    48.2 1829.84    52.2 1828.88    56.2 1828.52    64.2 1828.73
    68.41828.989    72.3 1829.75    76.3 1830.81    80.3 1832.09    84.3 1833.14
    88.3 1833.81    92.3  1834.1    96.8 1834.25    99.6 1834.43   105.7 1835.01
   110.2 1835.29   123.1 1835.77   128.5 1835.89
#Mann= 3 ,-1,0
       0     .08       0    52.2    .045       0    68.4      .1       0
Bank Sta=52.2,68.4
XS Rating Curve= 0 ,0
Exp/Cntr(USF)=0,0
Exp/Cntr=0.3,0.1

Type RM Length L Ch R = 1 ,5818    ,79.7,79,77.8
XS GIS Cut Line= 2
2183742.15617451671313.6991674222183851.23255933671390.132254596
#Sta/Elev= 28
       0 1858.52     2.5 1857.43    12.2 1852.23      13 1851.74    15.4 1850.08
    18.3 1847.87    33.9 1834.61    35.5 1833.61    41.5  1830.3    44.2 1829.52
    46.4 1829.09    51.3 1829.08    54.9 1828.73    55.6 1828.63    58.5  1828.5
      66 1828.43      70 1828.59    70.8 1828.75    72.9 1829.35    75.7 1830.62
    80.6 1832.44    82.7 1832.98    85.5 1833.35    95.3 1833.79   100.2 1833.78
   109.9 1834.45   117.6 1834.81   133.2 1835.96
#Mann= 4 ,-1,0
       0     .08       0      10      .1       0    54.9    .045       0
    70.8      .1       0
Bank Sta=54.9,70.8
XS Rating Curve= 0 ,0
Exp/Cntr(USF)=0,0
Exp/Cntr=0.3,0.1

Type RM Length L Ch R = 1 ,5739    ,89.1,89.7,90.1
XS GIS Cut Line= 2
2183689.60842708671378.9857627172183814.60837172671452.234137925
#Sta/Elev= 30
       0 1858.59       3 1857.03     9.3 1853.26    16.9  1849.4    21.5 1846.73
    26.9 1843.12    30.8 1840.34    35.4 1837.44    44.7 1832.51    47.3 1831.47
    50.2 1830.49    53.2 1829.86    58.6 1828.99    61.9 1828.14    63.2 1827.82
    64.9 1827.59    67.6 1827.33    70.7 1827.28    77.2 1827.32    81.8 1827.54
    84.61828.132    91.1 1829.83   100.3 1832.88     105 1833.34   109.6 1833.21
     123    1834   126.3 1834.56   132.8 1835.93   137.4 1836.57   144.9 1837.29
#Mann= 3 ,-1,0
       0      .1       0    61.9    .045       0    84.6      .1       0
Bank Sta=61.9,84.6
XS Rating Curve= 0 ,0
Exp/Cntr(USF)=0,0
Exp/Cntr=0.3,0.1

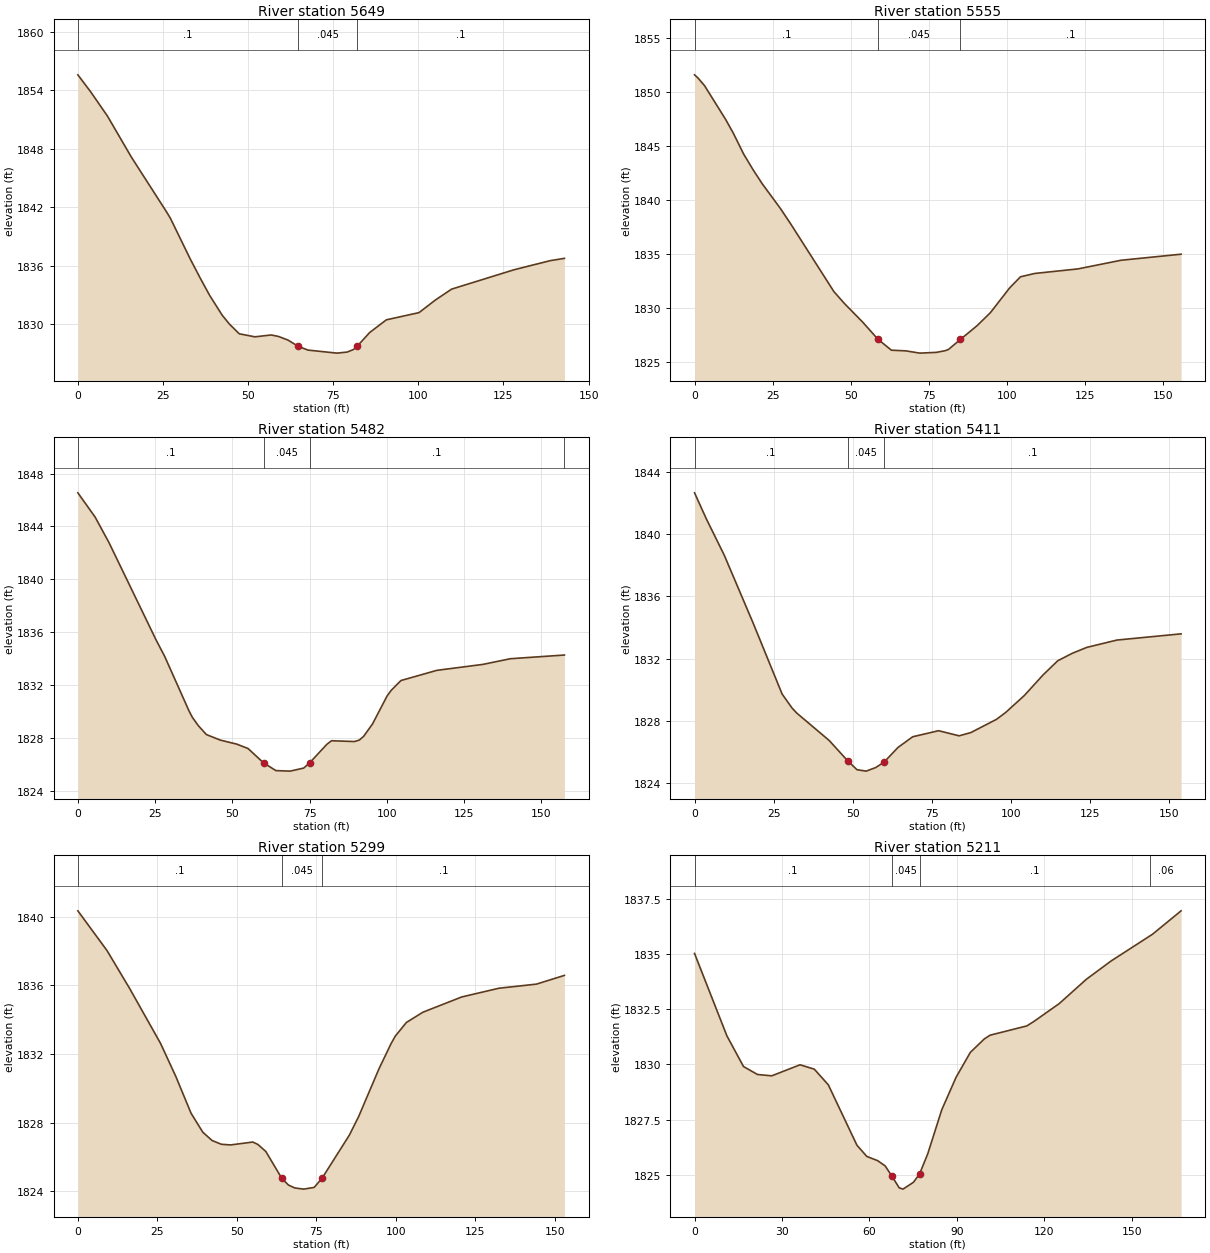
Type RM Length L Ch R = 1 ,5649    ,96.4,94.3,93.2
XS GIS Cut Line= 2
2183652.98423947671454.6226718992183771.61476019671534.240471039
#Sta/Elev= 30
       0 1855.57     3.8 1853.81     8.7 1851.34    15.7 1847.15    26.1  1841.5
    27.2 1840.86      33 1836.71    35.9 1834.77    38.7 1832.98    42.4 1830.94
    44.5 1830.04    47.4 1829.04      52 1828.73    56.8 1828.92    58.9 1828.77
    61.7  1828.4    64.7 1827.76    67.6 1827.37    76.1 1827.06    79.1 1827.17
    80.9 1827.42      82 1827.75    85.7 1829.17    90.6 1830.47   100.2 1831.21
     105  1832.5   109.8 1833.62   128.1  1835.6   138.7 1836.53   142.9 1836.77
#Mann= 3 ,-1,0
       0      .1       0    64.7    .045       0      82      .1       0
Bank Sta=64.7,82
XS Rating Curve= 0 ,0
Exp/Cntr(USF)=0,0
Exp/Cntr=0.3,0.1

Type RM Length L Ch R = 1 ,5555    ,73.2,72.9,72.5
XS GIS Cut Line= 2
2183593.40386461671534.4962279662183728.83374095671611.239824557
#Sta/Elev= 29
       0 1851.59     1.1  1851.3     3.2 1850.59     9.9 1847.49    12.4  1846.2
    15.7 1844.27    18.7 1842.83    21.6 1841.54    27.5 1839.22    30.8 1837.79
    44.6 1831.54      48 1830.43    53.8 1828.72    58.71827.133      63 1826.12
    67.6 1826.06    72.1 1825.85    77.4 1825.92    80.3 1826.08    81.3  1826.2
    85.1 1827.12    90.5 1828.41    94.7  1829.6   100.8 1831.87   104.3 1832.91
   108.9 1833.22   122.7 1833.64   136.5 1834.44   155.7    1835
#Mann= 3 ,-1,0
       0      .1       0    58.7    .045       0    85.1      .1       0
Bank Sta=58.7,85.1
XS Rating Curve= 0 ,0
Exp/Cntr(USF)=0,0
Exp/Cntr=0.3,0.1

Type RM Length L Ch R = 1 ,5482    ,70.7,71.2,71.7
XS GIS Cut Line= 2
2183559.22394344671601.5662619612183699.16814899671673.795529341
#Sta/Elev= 30
       0 1846.54     5.6  1844.7    10.1 1842.76    25.3 1835.41    28.1 1834.16
      36 1830.02    37.1 1829.53      39 1828.91    41.6 1828.24    46.1 1827.82
    51.5 1827.51    55.1 1827.18    60.11826.099    64.1 1825.51    68.7 1825.47
    73.1  1825.7    75.11826.115    80.6  1827.5    82.1 1827.77    89.5 1827.71
    91.1 1827.82    92.5  1828.1    95.4 1829.05   100.1 1831.16   101.4 1831.58
   104.6 1832.33   116.2  1833.1   131.1 1833.55     140 1833.98   157.5 1834.26
#Mann= 4 ,-1,0
       0      .1       0    60.1    .045       0    75.1      .1       0
  157.48     .05       0
Bank Sta=60.1,75.1
XS Rating Curve= 0 ,0
Exp/Cntr(USF)=0,0
Exp/Cntr=0.3,0.1

Type RM Length L Ch R = 1 ,5411    ,105.1,111.2,115.6
XS GIS Cut Line= 2
2183536.00739321671667.346487611 2183670.1474612671742.800275856
#Sta/Elev= 27
       0 1842.66     3.7    1841     9.4 1838.65    18.5  1834.3    27.7 1829.72
    30.8 1828.83    32.3  1828.5    42.6 1826.73    48.5 1825.41    51.4 1824.85
    54.3 1824.76    57.3 1824.99    59.9 1825.33    64.4 1826.29      69 1826.97
    77.2 1827.36    83.7 1827.03    87.4 1827.24    95.5 1828.09    98.4 1828.53
   104.3 1829.62   110.3 1830.96   114.9 1831.86   119.5 1832.34   124.1 1832.72
   133.6 1833.19   153.9 1833.59
#Mann= 3 ,-1,0
       0      .1       0    48.5    .045       0    59.9      .1       0
Bank Sta=48.5,59.9
XS Rating Curve= 0 ,0
Exp/Cntr(USF)=0,0
Exp/Cntr=0.3,0.1

Type RM Length L Ch R = 1 ,5299    ,88.7,88.4,88.1
XS GIS Cut Line= 3
2183491.04269301671731.6662432012183551.98613736671821.630375339
2183582.14721742671854.097009937
#Sta/Elev= 30
       0 1840.36     9.2 1838.03    16.3 1835.82      26 1832.62    30.8 1830.69
    35.6 1828.54    39.3 1827.43    42.2 1826.95    45.1 1826.73      48 1826.69
      55 1826.86    56.6 1826.72    59.1 1826.31    64.11824.749    66.2 1824.35
    68.2 1824.18      71 1824.11    74.3 1824.21    76.8 1824.75    85.4 1827.27
    88.3 1828.35    94.7 1831.14    98.5 1832.61    99.8 1833.04   103.3 1833.84
   108.5 1834.44   120.7 1835.33   132.4 1835.84   144.2 1836.08     153 1836.59
#Mann= 3 ,-1,0
       0      .1       0    64.1    .045       0    76.8      .1       0
Bank Sta=64.1,76.8
XS Rating Curve= 0 ,0
Exp/Cntr(USF)=0,0
Exp/Cntr=0.3,0.1

Type RM Length L Ch R = 1 ,5211    ,82.1,80.3,75.4
XS GIS Cut Line= 3
2183422.55386983671787.3859637512183488.72103798671883.154233446
 2183525.2871046 671917.97905879
#Sta/Elev= 30
       0 1835.02    11.1 1831.29    16.8  1829.9    21.6 1829.54    26.5 1829.48
    36.2 1829.98    41.1 1829.78    45.9 1829.07    55.7 1826.34    59.1 1825.83
    62.8 1825.64    65.4  1825.4    67.71824.939    70.2 1824.41    71.5 1824.35
    75.1 1824.66    77.2 1825.04      80 1825.95    84.8 1827.94    89.7 1829.41
    94.6 1830.54    99.4 1831.15   101.4 1831.32     114 1831.74   116.4 1831.94
   125.1 1832.75   134.4 1833.85   142.9 1834.68   157.1 1835.89   166.9 1836.95
#Mann= 4 ,-1,0
       0      .1       0    67.7    .045       0    77.2      .1       0
   156.4     .06       0
Bank Sta=67.7,77.2
XS Rating Curve= 0 ,0
Exp/Cntr(USF)=0,0
Exp/Cntr=0.3,0.1

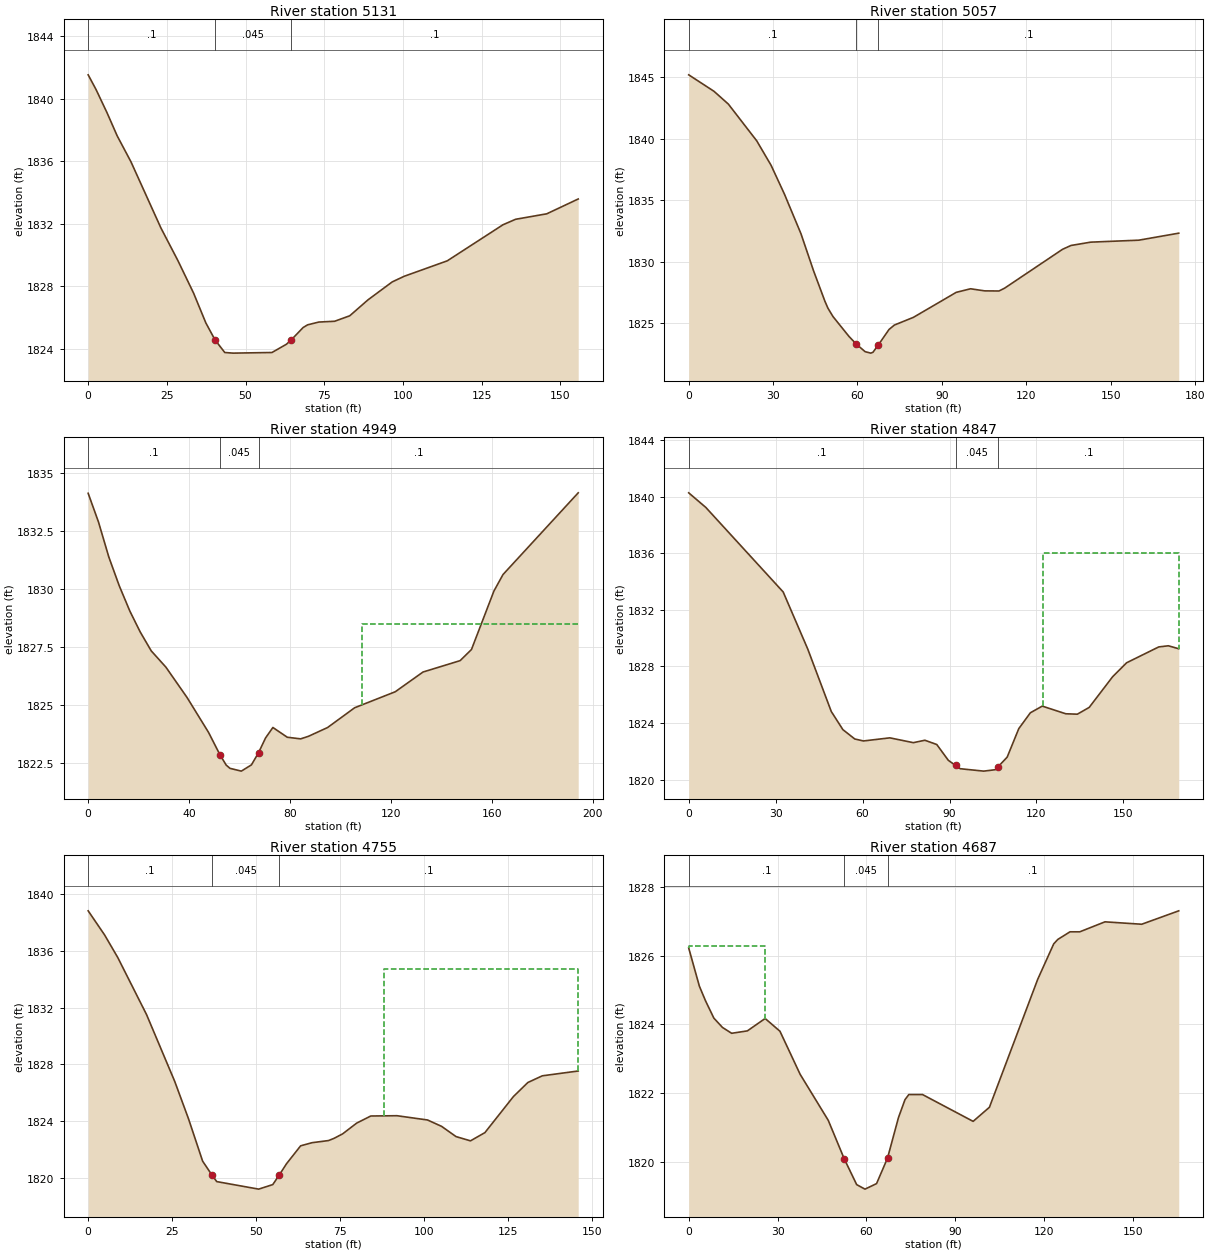
Type RM Length L Ch R = 1 ,5131    ,72.9,73.3,74.8
XS GIS Cut Line= 3
 2183358.7083567671826.2736853852183426.61676612 671917.97905879
2183460.28076395671942.356436531
#Sta/Elev= 28
       0 1841.54     2.5  1840.6       6 1839.11     9.2 1837.64    13.6 1835.97
    23.1 1831.74    28.5 1829.65    33.5 1827.56    37.4 1825.65    40.3 1824.57
    43.4 1823.76      46 1823.72    58.4 1823.76      63 1824.29    64.61824.583
    68.3 1825.36    69.7 1825.53    73.3 1825.71    78.3 1825.76    83.1 1826.11
    88.9 1827.13    96.6 1828.28   100.4 1828.64   114.1 1829.63   131.8 1831.94
   135.8 1832.29   145.7 1832.64   155.7 1833.59
#Mann= 3 ,-1,0
       0      .1       0    40.3    .045       0    64.6      .1       0
Bank Sta=40.3,64.6
XS Rating Curve= 0 ,0
Exp/Cntr(USF)=0,0
Exp/Cntr=0.3,0.1

Type RM Length L Ch R = 1 ,5057    ,109.6,108.2,107.5
XS GIS Cut Line= 3
2183287.31125259671854.076319138 2183359.0655654671946.472283572
2183406.24648341671978.909164703
#Sta/Elev= 30
       0 1845.19       9 1843.85    14.1 1842.81    24.2 1839.82    29.3 1837.83
      34 1835.51    39.9 1832.28    44.4 1829.25    48.4  1826.8    49.5 1826.22
    51.3 1825.54      57 1823.92    59.6  1823.3    62.7 1822.69    64.7 1822.57
    65.5 1822.64    67.41823.234    71.2 1824.49    73.1 1824.85    79.9 1825.48
    95.1 1827.51   100.2  1827.8   105.2 1827.63   110.3 1827.62   112.3 1827.85
   132.9 1831.01   135.9 1831.32   142.9 1831.59     160 1831.75   174.2 1832.32
#Mann= 3 ,-1,0
       0      .1       0    59.6    .045       0    67.4      .1       0
Bank Sta=59.6,67.4
XS Rating Curve= 0 ,0
Exp/Cntr(USF)=0,0
Exp/Cntr=0.3,0.1

Type RM Length L Ch R = 1 ,4949    ,93.9,102.1,108.1
XS GIS Cut Line= 4
2183209.17260135671917.2309675022183214.67318251671938.810170526
2183294.22004856672028.511955647 2183317.4917381672075.055334719
#Sta/Elev= 30
       0 1834.13     4.1 1832.89     8.2 1831.38    12.3 1830.15    16.5 1829.06
    20.6 1828.16      25 1827.34    30.8 1826.64    39.2 1825.33    47.7 1823.83
    52.2 1822.87    54.7 1822.42    56.2 1822.28    60.7 1822.16    64.7 1822.43
    67.5 1822.95    70.3 1823.59    73.2 1824.04    78.9 1823.62    84.2 1823.55
    87.3 1823.66    94.9 1824.04   105.6 1824.89   121.7 1825.58   132.7 1826.43
   147.4 1826.92   151.9  1827.4   160.8 1829.92   164.4 1830.63   194.2 1834.15
#Mann= 3 ,-1,0
       0      .1       0    52.2    .045       0    67.5      .1       0
#XS Ineff= 2 , 0
                          108.53         1828.51
Permanent Ineff=
       F       F
Bank Sta=52.2,67.5
XS Rating Curve= 0 ,0
Exp/Cntr(USF)=0,0
Exp/Cntr=0.3,0.1

Type RM Length L Ch R = 1 ,4847    ,96.4,92.7,90.5
XS GIS Cut Line= 4
2183129.45465417 671919.916461292183145.70623933671953.000045367
 2183161.9578245672060.9570039322183174.72692712672080.110657871
#Sta/Elev= 30
       0 1840.26     5.9 1839.23    32.6 1833.26    41.1 1829.22    49.2 1824.82
    53.2 1823.54    57.3 1822.88    60.3 1822.74    69.4 1822.96    77.5 1822.62
    81.5 1822.79    85.6 1822.49    89.6 1821.37    92.1 1821.01    93.7 1820.78
   101.8 1820.61   105.8 1820.71   106.81820.926   109.9  1821.6   113.9 1823.61
   117.9 1824.73     122  1825.2   130.1 1824.66   134.1 1824.63   138.2 1825.11
   146.3 1827.28   151.1 1828.26   162.2 1829.38   165.5 1829.46   169.1 1829.25
#Mann= 3 ,-1,0
       0      .1       0    92.1    .045       0   106.8      .1       0
#XS Ineff= 2 , 0
                          122.16         1835.98
Permanent Ineff=
       F       F
Bank Sta=92.1,106.8
XS Rating Curve= 0 ,0
Exp/Cntr(USF)=0,0
Exp/Cntr=0.3,0.1

Type RM Length L Ch R = 1 ,4755    ,74.6,67.2,61.1
XS GIS Cut Line= 3
2183049.93796964671956.4825279012183076.05658865672044.705418772
2183095.21024259 672095.20141552
#Sta/Elev= 30
       0 1838.82     4.9 1837.12     8.8 1835.54    17.4 1831.51    25.8  1826.8
    29.9 1824.17    34.1 1821.19    36.91820.207    38.3 1819.75    50.8 1819.22
      55 1819.54      57 1820.24    59.1 1821.01    63.3 1822.27    66.7 1822.49
    71.6 1822.64    73.2 1822.79    75.8 1823.11      80 1823.87    84.2 1824.37
      92 1824.39   101.1 1824.09   105.3 1823.64   109.6 1822.92   113.9 1822.62
   118.2  1823.2   126.7 1825.74     131 1826.73   135.3  1827.2     146 1827.54
#Mann= 3 ,-1,0
       0      .1       0    36.9    .045       0      57      .1       0
#XS Ineff= 2 , 0
                           88.22         1834.71
Permanent Ineff=
       F       F
Bank Sta=36.9,57
XS Rating Curve= 0 ,0
Exp/Cntr(USF)=0,0
Exp/Cntr=0.3,0.1

Type RM Length L Ch R = 1 ,4687    ,65.8,68.4,72
XS GIS Cut Line= 3
2182970.72745488671998.548810888 2183060.7436198672096.285797931
2183092.27226826672104.167960046
#Sta/Elev= 30
       0 1826.22     3.6 1825.11     5.7 1824.68     8.5 1824.18    11.4 1823.91
    14.5 1823.74    19.8 1823.81    25.8 1824.17    30.8  1823.8    37.6 1822.55
    47.1 1821.21    52.5 1820.09    56.7 1819.34    59.5 1819.21    63.4 1819.37
    67.1 1820.11    70.8 1821.29      73 1821.81    74.3 1821.96    78.9 1821.96
      96 1821.18   101.5 1821.59   117.8 1825.31   123.2 1826.34   124.6 1826.47
   128.7 1826.69     132 1826.69   140.5 1826.98   152.9 1826.91   165.4  1827.3
#Mann= 3 ,-1,0
       0      .1       0    52.5    .045       0    67.1      .1       0
#XS Ineff= 2 , 0
            25.8 1826.28
Permanent Ineff=
       F       F
Bank Sta=52.5,67.1
XS Rating Curve= 0 ,0
Exp/Cntr(USF)=0,0
Exp/Cntr=0.3,0.1

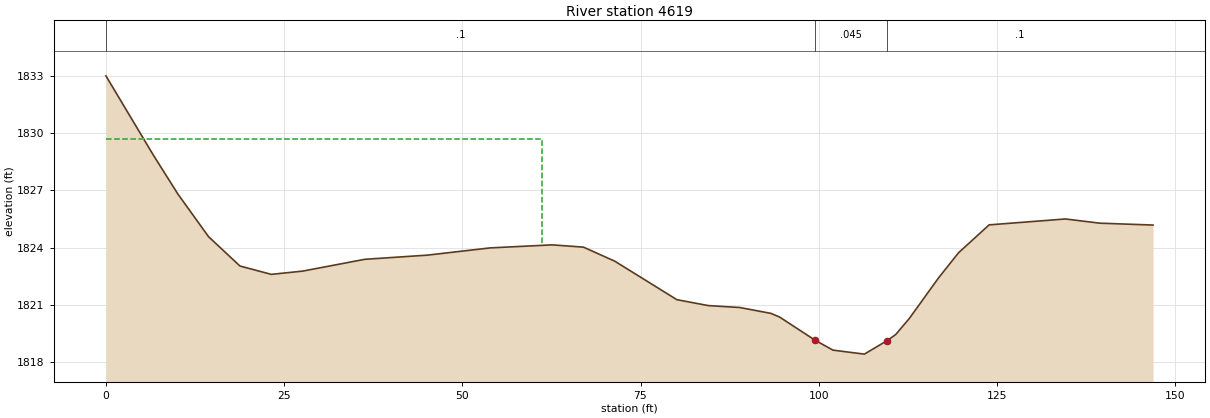
Type RM Length L Ch R = 1 ,4619    ,54.8,58.4,62.3
XS GIS Cut Line= 3
2182920.60448983671995.9820470372182973.32327634672114.199802737
2182987.65448019672124.231645429
#Sta/Elev= 30
       0 1833.02     6.6 1828.89    10.1 1826.81    14.4 1824.57    18.8 1823.03
    23.2 1822.59    27.6 1822.76    36.3 1823.38    45.1  1823.6    53.9 1823.98
    62.6 1824.14      67 1824.02    71.4 1823.28    80.1 1821.26    84.5 1820.95
    88.9 1820.85    93.3 1820.54    94.5 1820.35    99.51819.128     102 1818.61
   106.4  1818.4   109.6 1819.11   110.8 1819.43   112.7 1820.27   116.8  1822.4
   119.6 1823.72   123.9 1825.19   134.6  1825.5   139.4 1825.28   146.9 1825.18
#Mann= 3 ,-1,0
       0      .1       0    99.5    .045       0   109.6      .1       0
#XS Ineff= 2 , 0
           61.19 1829.72
Permanent Ineff=
       F       F
Bank Sta=99.5,109.6
XS Rating Curve= 0 ,0
Exp/Cntr(USF)=0,0
Exp/Cntr=0.3,0.1