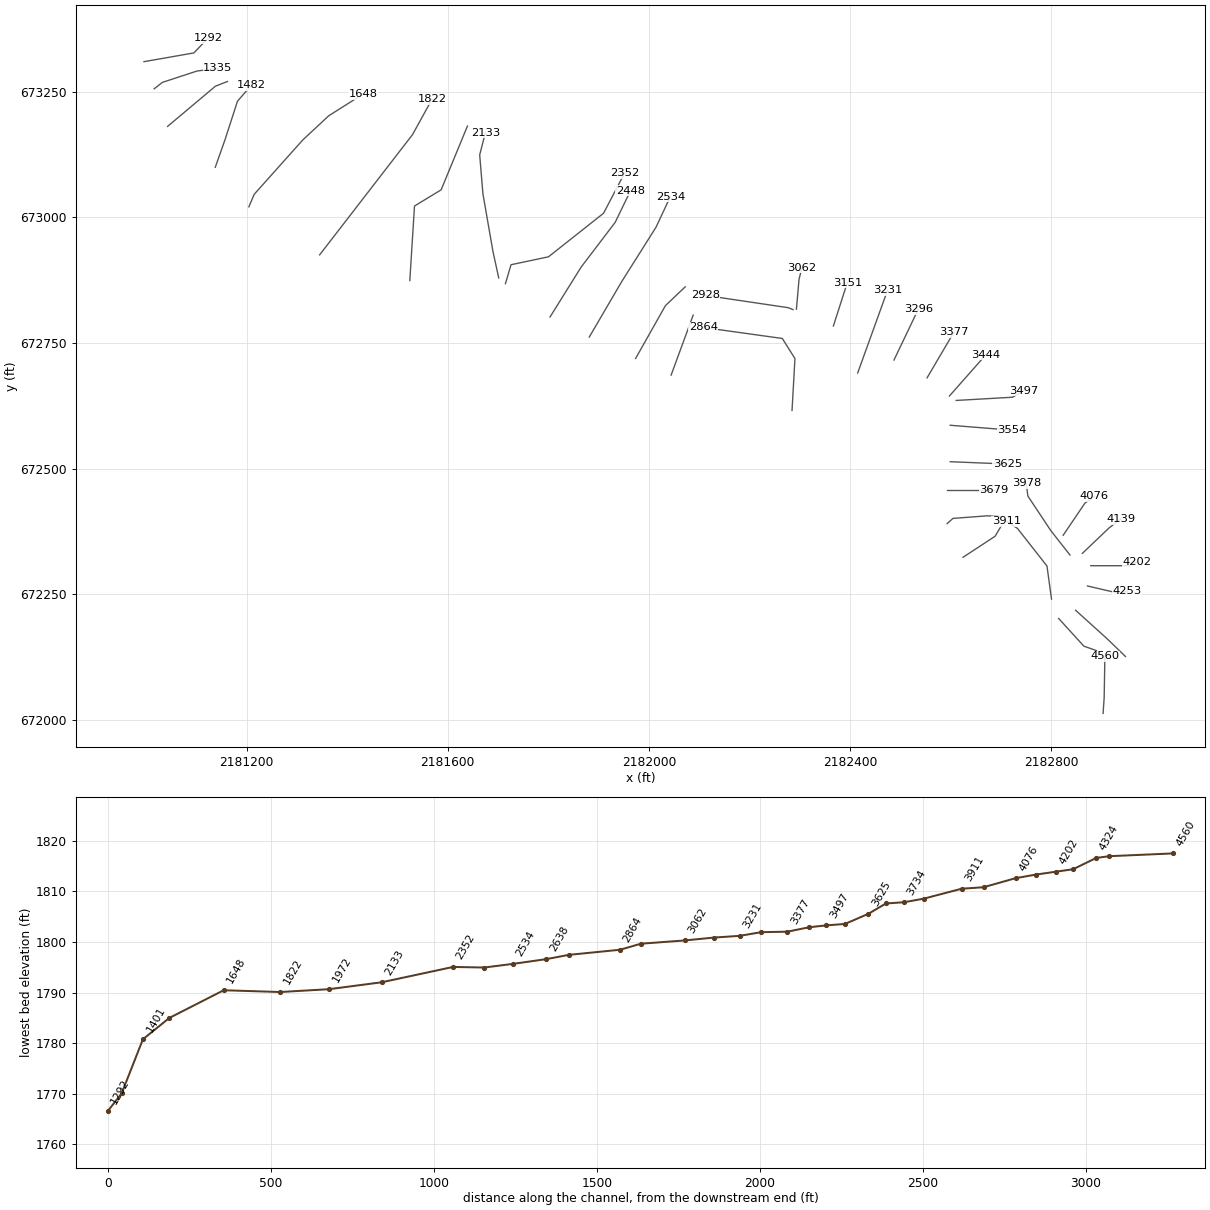
HEC-RAS study QUEENSFK.prj: QUEENSFK

--- QUEENSFK.g01 (geometry) --- (continued)

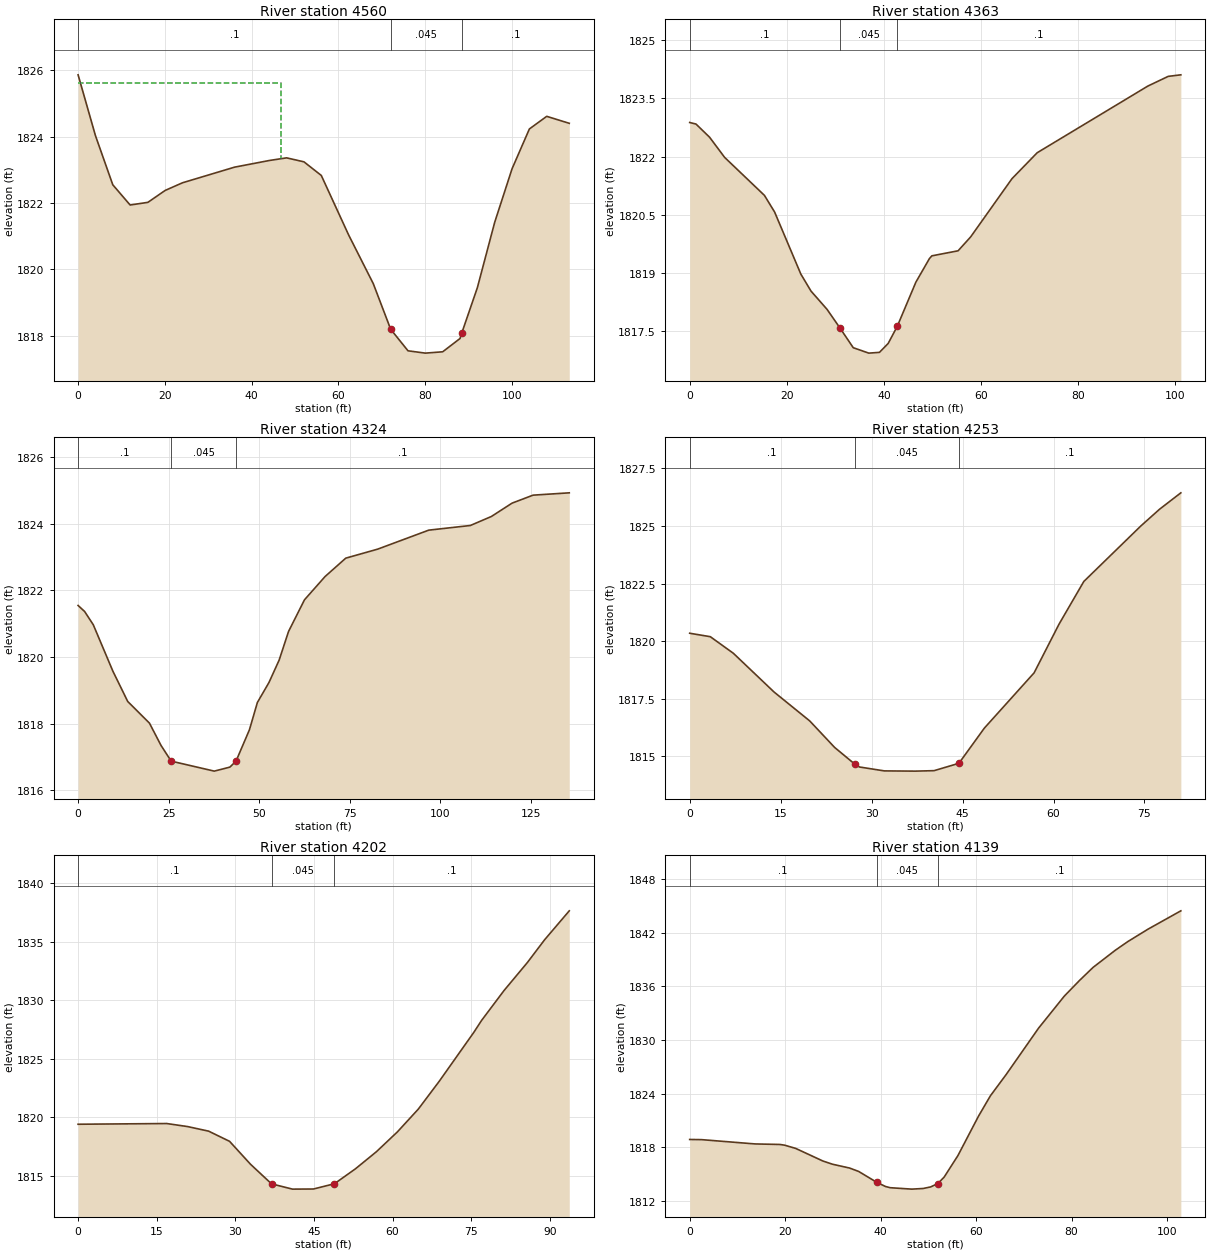
Type RM Length L Ch R = 1 ,4560    ,224.5,197,168.4
XS GIS Cut Line= 3
2182903.81693769672013.1648156292182905.96661827672043.976903896
2182907.39973865672126.381326006
#Sta/Elev= 26
       0 1825.86       4 1824.03       8 1822.55      12 1821.94    16.1 1822.02
    20.1 1822.38    24.1 1822.61    36.1 1823.08    44.1 1823.28    48.1 1823.36
    52.1 1823.24    56.1 1822.83    62.4 1821.04    68.1 1819.57    72.1  1818.2
    76.1 1817.55    80.1 1817.48    84.1 1817.52    88.1 1817.92    88.51818.083
    92.1 1819.45    96.1 1821.42   100.1 1823.03   104.1 1824.23   108.1 1824.61
   113.3  1824.4
#Mann= 3 ,-1,0
       0      .1       0    72.1    .045       0    88.5      .1       0
#XS Ineff= 2 , 0
           46.76 1825.62
Permanent Ineff=
       F       F
Bank Sta=72.1,88.5
XS Rating Curve= 0 ,0
Exp/Cntr(USF)=0,0
Exp/Cntr=0.3,0.1

Type RM Length L Ch R = 1 ,4363    ,38.3,39.8,42.3
XS GIS Cut Line= 3
2182815.36160942672202.1284232192182865.52082288672146.953288415
2182890.62871645672138.076428087
#Sta/Elev= 25
       0 1822.88     1.3 1822.84     4.1  1822.5     7.2 1821.98    15.4    1821
    17.5 1820.57    22.9 1818.97      25 1818.53    28.3 1818.06    30.9 1817.59
    33.7 1817.07    36.9 1816.93    39.1 1816.95    40.9 1817.18    42.8 1817.63
    46.6 1818.76    49.4 1819.37    49.9 1819.44    55.3 1819.57    57.9 1819.93
    66.4 1821.43    71.6  1822.1    94.4 1823.82    98.6 1824.07   101.2 1824.11
#Mann= 3 ,-1,0
       0      .1       0    30.9    .045       0    42.8      .1       0
Bank Sta=30.9,42.8
XS Rating Curve= 0 ,0
Exp/Cntr(USF)=0,0
Exp/Cntr=0.3,0.1

Type RM Length L Ch R = 1 ,4324    ,64.9,71.1,78.8
XS GIS Cut Line= 3
2182849.06047038672218.3814048532182912.27484159672161.259985083
2182948.45174078672126.225514291
#Sta/Elev= 26
       0 1821.55     1.8 1821.37     4.2 1820.97     9.6 1819.58    13.7 1818.67
    19.7 1818.02    22.9 1817.35    25.7 1816.88    37.6 1816.58    41.9  1816.7
    43.6 1816.88    47.3 1817.82    49.5 1818.64    52.7 1819.24    55.5 1819.91
    58.1 1820.77    62.5 1821.72    68.2 1822.42    73.9 1822.97    82.7 1823.24
    96.8 1823.81   108.3 1823.95   114.1 1824.22   119.8 1824.62   125.6 1824.86
   135.6 1824.93
#Mann= 3 ,-1,0
       0      .1       0    25.7    .045       0    43.6      .1       0
Bank Sta=25.7,43.6
XS Rating Curve= 0 ,0
Exp/Cntr(USF)=0,0
Exp/Cntr=0.3,0.1

Type RM Length L Ch R = 1 ,4253    ,48.6,50.9,53.1
XS GIS Cut Line= 3
 2182872.8789799672266.5784152192182936.72930292672251.772543214
2182951.53517493672256.090922549
#Sta/Elev= 19
       0 1820.34     3.4 1820.19     7.2 1819.47    13.9 1817.79    19.8 1816.53
    23.9 1815.38    27.2 1814.66      28 1814.53    32.1 1814.36    37.2 1814.35
    40.3 1814.37    44.4 1814.69    48.6 1816.22    56.8 1818.62    60.9 1820.73
      65 1822.59    74.4    1825    77.5 1825.73      81 1826.44
#Mann= 3 ,-1,0
       0      .1       0    27.2    .045       0    44.4      .1       0
Bank Sta=27.2,44.4
XS Rating Curve= 0 ,0
Exp/Cntr(USF)=0,0
Exp/Cntr=0.3,0.1

Type RM Length L Ch R = 1 ,4202    ,54.4,62.7,71.4
XS GIS Cut Line= 3
2182879.27461011672306.9559970952182954.72839836672306.955997095
2182971.49590685672314.049942998
#Sta/Elev= 21
       0 1819.42    16.9 1819.48    20.9 1819.22    24.9 1818.83    28.9 1817.96
    32.9    1816    36.9 1814.33    40.9 1813.88    44.9 1813.89    48.9 1814.34
    52.9 1815.61    56.9 1817.07    60.9 1818.76    64.9 1820.71    68.9 1823.09
    75.5 1827.27      77  1828.3    81.3 1830.86    85.7 1833.22      89 1835.17
    93.7 1837.64
#Mann= 3 ,-1,0
       0      .1       0    36.9    .045       0    48.9      .1       0
Bank Sta=36.9,48.9
XS Rating Curve= 0 ,0
Exp/Cntr(USF)=0,0
Exp/Cntr=0.3,0.1

Type RM Length L Ch R = 1 ,4139    ,59.8,62.5,64.9
XS GIS Cut Line= 3
2182862.50710161 672331.462355672182916.03414797 672382.40978534
 2182939.2506982672399.822198011
#Sta/Elev= 30
       0 1818.86     2.5 1818.84    13.7 1818.36    18.9  1818.3    19.9 1818.22
    22.2 1817.86    27.9 1816.45    29.9 1816.09    33.5 1815.66    35.4 1815.28
    39.2 1814.06      41  1813.6      42 1813.46    46.5  1813.3    48.9 1813.37
    50.5 1813.55      52 1813.93    53.3 1814.64    56.2 1817.06    60.5 1821.46
      63 1823.75    66.3 1826.13    73.1 1831.33    78.5 1834.92    81.7 1836.68
    84.5 1838.12    89.1 1840.02    91.8 1841.02      96  1842.4   102.9 1844.46
#Mann= 3 ,-1,0
       0      .1       0    39.2    .045       0      52      .1       0
Bank Sta=39.2,52
XS Rating Curve= 0 ,0
Exp/Cntr(USF)=0,0
Exp/Cntr=0.3,0.1

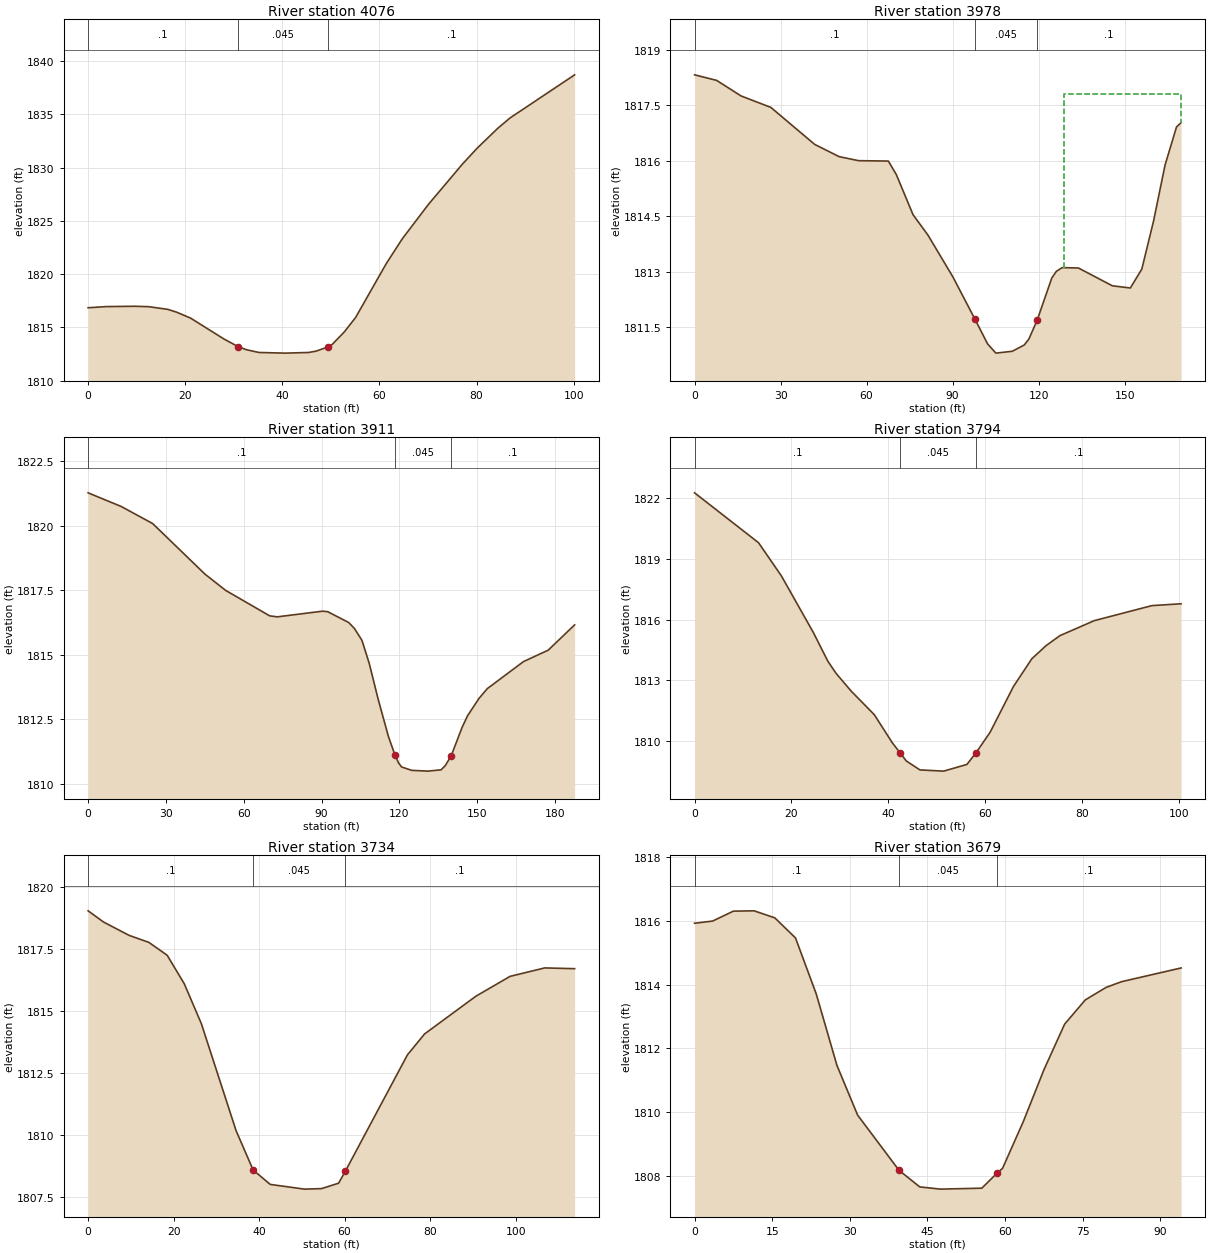
Type RM Length L Ch R = 1 ,4076    ,80.5,98,110.5
XS GIS Cut Line= 3
 2182824.4577554 672367.57698936  2182867.666335 672431.42250249
2182886.36855601672444.965490124
#Sta/Elev= 26
       0 1816.85     3.8 1816.96     9.6 1816.99    12.5 1816.95    16.4  1816.7
    18.2 1816.44    21.1 1815.88      28 1813.91    30.9  1813.2    32.6 1812.91
    35.2 1812.65    40.6 1812.59    45.4 1812.65      47 1812.78    49.5 1813.19
    50.2 1813.37    52.8  1814.6    55.1 1815.94    61.4 1820.99    64.7 1823.32
    70.1 1826.56    77.1 1830.34    80.1 1831.82    84.4 1833.71    86.9 1834.67
   100.2 1838.72
#Mann= 3 ,-1,0
       0      .1       0    30.9    .045       0    49.5      .1       0
Bank Sta=30.9,49.5
XS Rating Curve= 0 ,0
Exp/Cntr(USF)=0,0
Exp/Cntr=0.3,0.1

Type RM Length L Ch R = 1 ,3978    ,62.6,67.6,66.2
XS GIS Cut Line= 4
2182838.00074304672328.2378348052182799.95139683672376.605647782
2182754.16320054672445.6103942972182750.93867968672470.761657045
#Sta/Elev= 30
       0 1818.32     7.7 1818.17    16.2 1817.75    26.6 1817.44    41.9 1816.44
    50.4 1816.11    57.2    1816    67.6 1815.99    70.4 1815.62    76.2 1814.54
    81.4 1813.99    90.1 1812.86    97.81811.717   102.2 1811.05   105.1  1810.8
   110.8 1810.85     115 1811.02   116.6 1811.18   119.5 1811.69   124.6 1812.83
   126.2 1813.01   128.2 1813.11   133.9  1813.1   145.7 1812.62     152 1812.56
     156 1813.07   160.1 1814.37   164.1 1815.88   168.1 1816.91   169.7 1817.03
#Mann= 3 ,-1,0
       0      .1       0    97.8    .045       0   119.5      .1       0
#XS Ineff= 2 , 0
                           128.7          1817.8
Permanent Ineff=
       F       F
Bank Sta=97.8,119.5
XS Rating Curve= 0 ,0
Exp/Cntr(USF)=0,0
Exp/Cntr=0.3,0.1

Type RM Length L Ch R = 1 ,3911    ,136.4,116.6,89.1
XS GIS Cut Line= 4
2182801.24120517672240.5308672732182792.21254675672306.311092922
2182733.52626701672381.1199769942182711.59952512  672395.3078688
#Sta/Elev= 30
       0 1821.27    12.8 1820.74    24.9 1820.08    45.1 1818.12    53.1 1817.49
      70 1816.51    72.9 1816.47    90.4 1816.69    92.4 1816.67   100.5 1816.25
   102.7 1816.02   105.6 1815.56   108.4 1814.67   111.8  1813.3   115.8 1811.84
   118.3 1811.13   119.7 1810.82   120.9 1810.66   124.8 1810.53     131  1810.5
   136.1 1810.55   137.7 1810.71     1401811.092   144.2 1812.19   146.3 1812.64
   150.7 1813.31   153.9 1813.69   167.9 1814.74   177.4 1815.18   187.6 1816.16
#Mann= 3 ,-1,0
       0      .1       0   118.3    .045       0     140      .1       0
Bank Sta=118.3,140
XS Rating Curve= 0 ,0
Exp/Cntr(USF)=0,0
Exp/Cntr=0.3,0.1

Type RM Length L Ch R = 1 ,3794    ,68.5,60.7,52.9
XS GIS Cut Line= 3
2182625.18236594672323.7235055942182689.02787907672365.642276841
2182701.28105835672386.279210378
#Sta/Elev= 23
       0 1822.25    13.2 1819.79    17.9 1818.16    24.5 1815.37    27.5 1813.95
    29.2 1813.35    32.3 1812.48    37.1 1811.31    40.8 1809.93    42.41809.433
    43.7 1809.03    46.5 1808.59    51.4 1808.53    56.2 1808.86    58.1 1809.44
      61 1810.45    65.8  1812.7    69.6 1814.07    72.5 1814.71    75.4 1815.21
    82.5 1815.95    94.4 1816.69   100.4 1816.78
#Mann= 3 ,-1,0
       0      .1       0    42.4    .045       0    58.1      .1       0
Bank Sta=42.4,58.1
XS Rating Curve= 0 ,0
Exp/Cntr(USF)=0,0
Exp/Cntr=0.3,0.1

Type RM Length L Ch R = 1 ,3734    ,55.9,54.6,53.4
XS GIS Cut Line= 4
2182593.58206146672390.7935395892182605.19033657672401.112006358
2182674.19508309672406.2712397422182703.21577087672404.336527223
#Sta/Elev= 20
       0 1819.04     3.6 1818.59     9.6 1818.05    14.2 1817.77    18.5 1817.25
    22.5  1816.1    26.5 1814.49    34.6 1810.19    38.6  1808.6    42.6 1808.02
    50.6 1807.83    54.6 1807.85    58.6 1808.07    60.21808.562    74.7 1813.24
    78.7 1814.08    90.7  1815.6    98.7  1816.4   106.8 1816.74   113.8 1816.71
#Mann= 3 ,-1,0
       0      .1       0    38.6    .045       0    60.2      .1       0
Bank Sta=38.6,60.2
XS Rating Curve= 0 ,0
Exp/Cntr(USF)=0,0
Exp/Cntr=0.3,0.1

Type RM Length L Ch R = 1 ,3679    ,54.9,54.2,53.7
XS GIS Cut Line= 2
2182592.71506076672458.1495958862182686.74208919672458.149595886
#Sta/Elev= 22
       0 1815.92     3.5 1815.99     7.5  1816.3    11.5 1816.31    15.5 1816.09
    19.5 1815.46    23.5 1813.71    27.5 1811.47    31.5 1809.91    39.5 1808.18
    43.5 1807.66    47.5 1807.59    55.5 1807.62    58.5  1808.1    59.5 1808.24
    63.5  1809.7    67.5 1811.33    71.5 1812.76    75.5 1813.52    79.5 1813.91
    82.5 1814.09      94 1814.52
#Mann= 3 ,-1,0
       0      .1       0    39.5    .045       0    58.5      .1       0
Bank Sta=39.5,58.5
XS Rating Curve= 0 ,0
Exp/Cntr(USF)=0,0
Exp/Cntr=0.3,0.1

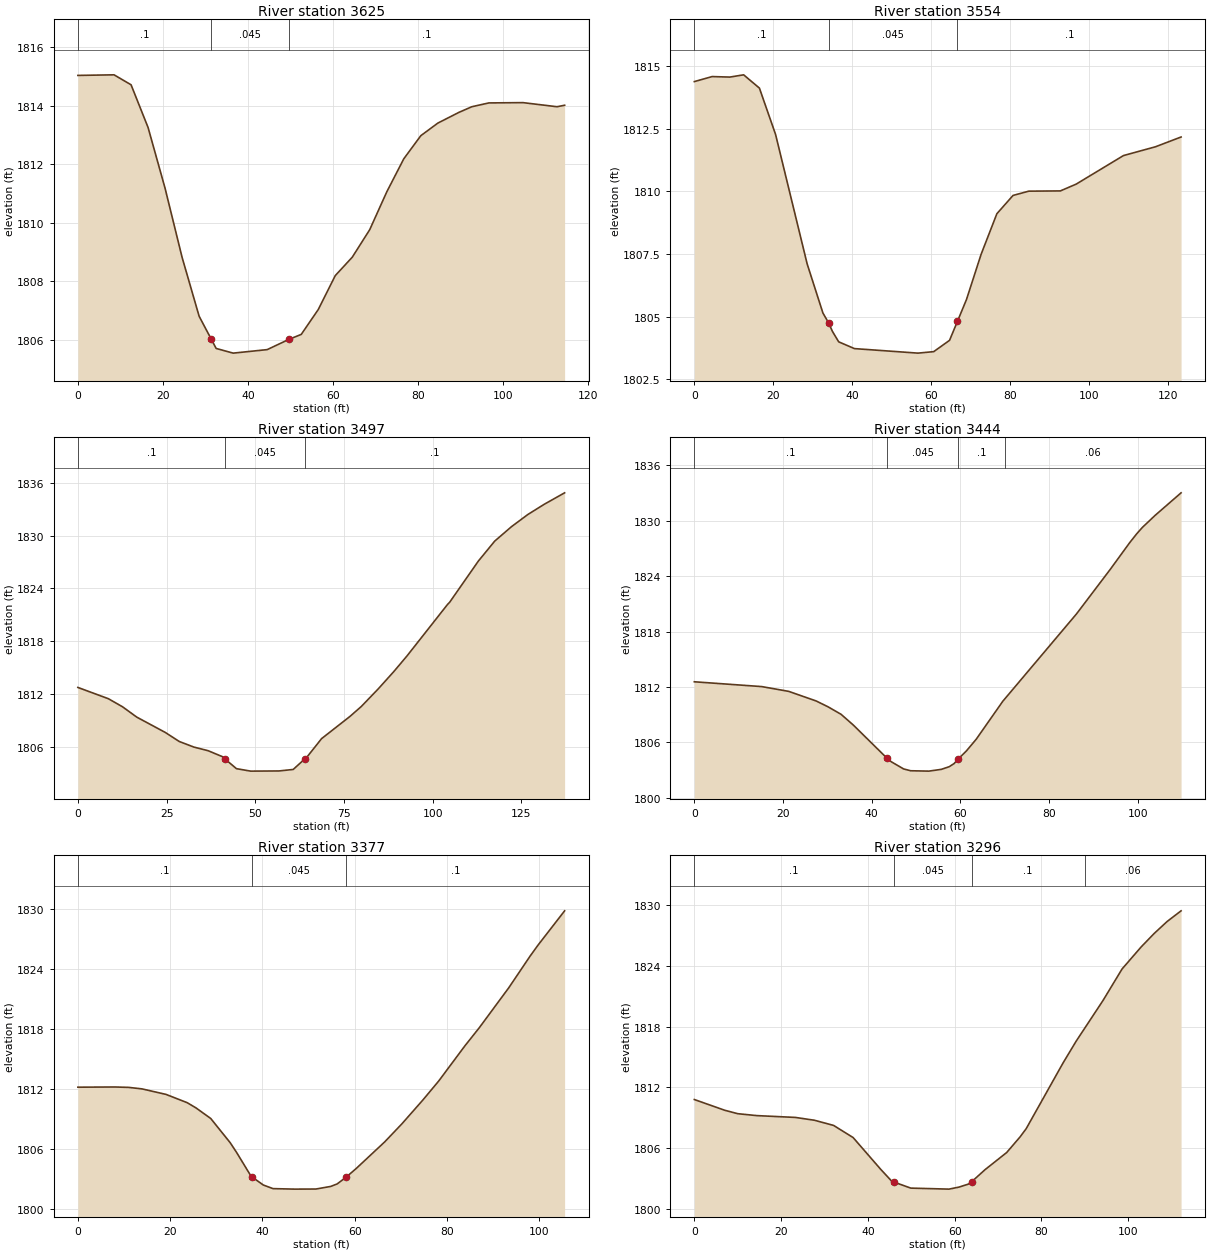
Type RM Length L Ch R = 1 ,3625    ,71.8,71.3,71.9
XS GIS Cut Line= 2
2182599.68002583672513.8693164362182714.02153571 672509.22600639
#Sta/Elev= 27
       0 1815.03     8.5 1815.05    12.5 1814.71    16.5 1813.25    20.5 1811.17
    24.5 1808.81    28.5  1806.8    31.3 1806.03    32.5  1805.7    36.5 1805.54
    44.5 1805.66    49.6 1806.01    52.5 1806.18    56.5 1807.03    60.5 1808.19
    64.5 1808.82    68.6 1809.76    72.6 1811.05    76.6 1812.18    80.6 1812.97
    84.6  1813.4    89.6 1813.77    92.6 1813.96    96.6 1814.09   104.6  1814.1
   112.6 1813.96   114.4 1814.01
#Mann= 3 ,-1,0
       0      .1       0    31.3    .045       0    49.6      .1       0
Bank Sta=31.3,49.6
XS Rating Curve= 0 ,0
Exp/Cntr(USF)=0,0
Exp/Cntr=0.3,0.1

Type RM Length L Ch R = 1 ,3554    ,57.6,57,59.9
XS GIS Cut Line= 2
2182599.68002583672586.4210359022182722.72774204672576.554002054
#Sta/Elev= 26
       0 1814.38     4.5 1814.58       9 1814.56    12.5 1814.65    16.5 1814.12
    20.6 1812.27    28.6 1807.11    32.6 1805.15    34.1 1804.74      35 1804.42
    36.6    1804    40.6 1803.73    56.7 1803.55    60.7 1803.61    64.7 1804.06
    66.71804.815      69 1805.69    72.7 1807.49    76.7 1809.11    80.8 1809.84
    84.8 1810.01    92.8 1810.02    96.8 1810.29   108.8 1811.43   116.9 1811.78
   123.4 1812.17
#Mann= 3 ,-1,0
       0      .1       0    34.1    .045       0    66.7      .1       0
Bank Sta=34.1,66.7
XS Rating Curve= 0 ,0
Exp/Cntr(USF)=0,0
Exp/Cntr=0.3,0.1

Type RM Length L Ch R = 1 ,3497    ,44.4,52.7,68.3
XS GIS Cut Line= 3
2182611.57205812672635.7757797582182723.59191298672642.160331071
2182745.06722194672654.929433697
#Sta/Elev= 30
       0 1812.76     8.6 1811.48    12.6 1810.56    16.6 1809.39    24.6 1807.66
    28.6 1806.62    32.7 1805.99    36.7 1805.58    40.7 1804.91    41.6 1804.59
    44.7 1803.54    48.7 1803.26    56.7 1803.28    60.7 1803.45    63.91804.626
    64.7 1804.92    68.7 1806.95    76.7 1809.47    79.9  1810.6    84.7 1812.61
    89.1 1814.58    92.8 1816.35   104.2 1822.18   104.8 1822.43   112.9 1827.11
   117.5 1829.37   122.2    1831   126.8 1832.38   131.5 1833.56   137.2 1834.85
#Mann= 3 ,-1,0
       0      .1       0    41.6    .045       0    63.9      .1       0
Bank Sta=41.6,63.9
XS Rating Curve= 0 ,0
Exp/Cntr(USF)=0,0
Exp/Cntr=0.3,0.1

Type RM Length L Ch R = 1 ,3444    ,64.2,66.7,69.5
XS GIS Cut Line= 2
2182598.08790138672644.6011244652182670.77426121672726.900739408
#Sta/Elev= 26
       0 1812.57    15.2 1812.05    21.3 1811.53    27.5 1810.49    30.2 1809.85
    33.1 1809.05    35.9 1807.87    43.5 1804.28    44.4 1803.92    47.2 1803.14
    48.8 1802.94    52.9  1802.9    55.7 1803.09    57.5 1803.38    58.6 1803.72
    59.5  1804.2    61.4  1805.1    63.6 1806.36    69.6 1810.47    86.2 1819.91
    93.8 1824.72    98.2 1827.62    99.8 1828.59   101.1 1829.29   103.9 1830.56
   109.8 1833.02
#Mann= 4 ,-1,0
       0      .1       0    43.5    .045       0    59.5      .1       0
      70     .06       0
Bank Sta=43.5,59.5
XS Rating Curve= 0 ,0
Exp/Cntr(USF)=0,0
Exp/Cntr=0.3,0.1

Type RM Length L Ch R = 1 ,3377    ,79.3,80.9,81.5
XS GIS Cut Line= 2
2182553.58951344672680.715758155 2182607.1165598672771.647246552
#Sta/Elev= 30
       0 1812.21     8.1 1812.23      11 1812.19    13.9 1812.04    19.1 1811.49
    23.7 1810.66    25.6 1810.14    28.8 1809.08      33 1806.67    34.4 1805.69
    37.3 1803.49    37.7 1803.25    40.2 1802.43    42.3 1802.07      47 1802.02
    51.6 1802.03    54.8 1802.29    56.2 1802.54   58.13 1803.21    60.3 1804.07
    66.5 1806.74    70.2 1808.53    74.8 1810.94    78.2 1812.82    83.9 1816.35
      87 1818.15    93.4 1822.15      98  1825.3    99.7 1826.39   105.5 1829.84
#Mann= 3 ,-1,0
       0      .1       0    37.7    .045       0   58.13      .1       0
Bank Sta=37.7,58.13
XS Rating Curve= 0 ,0
Exp/Cntr(USF)=0,0
Exp/Cntr=0.3,0.1

Type RM Length L Ch R = 1 ,3296    ,63.8,64.9,66.3
XS GIS Cut Line= 2
2182487.80928779672716.1854876722182536.17710077672817.435442837
#Sta/Elev= 28
       0 1810.78       7 1809.72      10 1809.38    14.4 1809.19    23.3 1809.01
    27.7 1808.73    32.1 1808.22    36.6 1807.02      43 1803.86    45.4 1802.75
      46 1802.62    49.9 1802.02    58.7 1801.92      61 1802.12    63.2 1802.42
    63.91802.639      67 1803.84      72 1805.54    75.1 1807.09    76.5  1807.9
      85  1814.4      88 1816.54    94.2 1820.57    98.6 1823.69     103 1825.87
     106  1827.2     109 1828.39   112.2 1829.44
#Mann= 4 ,-1,0
       0      .1       0      46    .045       0    63.9      .1       0
      90     .06       0
Bank Sta=46,63.9
XS Rating Curve= 0 ,0
Exp/Cntr(USF)=0,0
Exp/Cntr=0.3,0.1

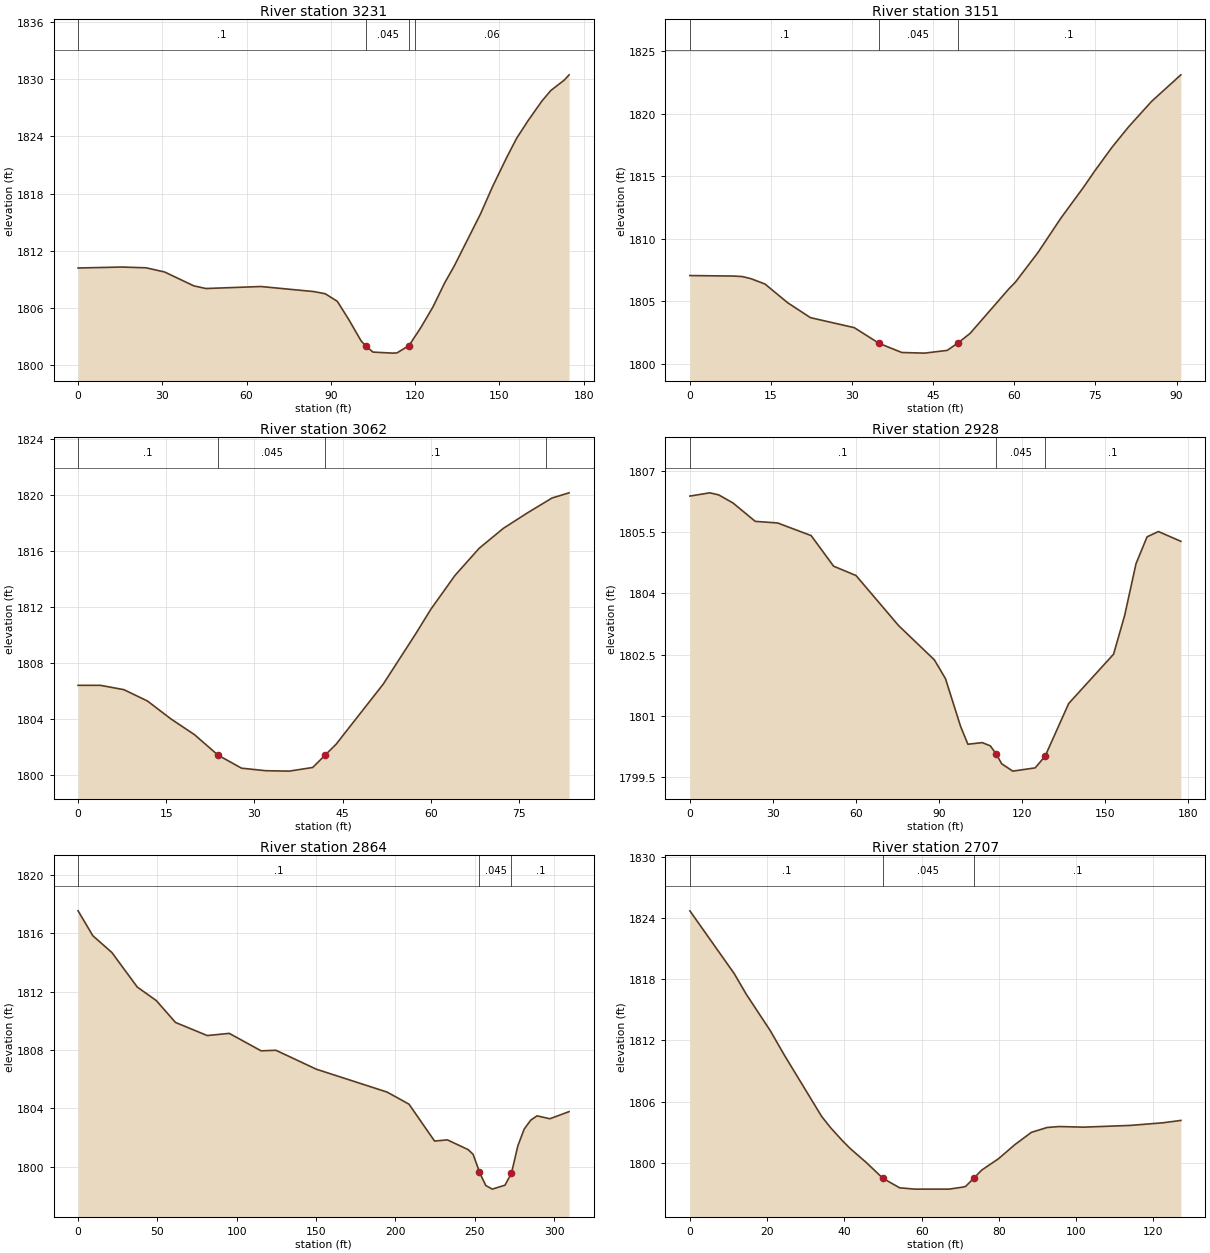
Type RM Length L Ch R = 1 ,3231    ,79,80.2,79.9
XS GIS Cut Line= 2
2182415.58002041 672690.389320752182474.91120433672854.839884873
#Sta/Elev= 30
       0 1810.16    15.7 1810.26    24.2 1810.18    30.8 1809.74    41.2 1808.28
    45.5    1808    65.1 1808.21    83.9 1807.68      88 1807.45    92.3 1806.65
    96.4 1804.72   100.8 1802.47   102.6 1801.91     105 1801.31     112  1801.2
   113.5 1801.22   117.8 1801.99     122 1803.88   126.3 1806.04   130.5 1808.59
   133.9 1810.36   143.3 1815.87   147.5 1818.69   152.6  1821.8   156.1  1823.8
   160.3 1825.71   165.1 1827.72   168.3 1828.84   173.1 1829.94   174.8 1830.49
#Mann= 4 ,-1,0
       0      .1       0   102.6    .045       0   117.8      .1       0
     120     .06       0
Bank Sta=102.6,117.8
XS Rating Curve= 0 ,0
Exp/Cntr(USF)=0,0
Exp/Cntr=0.3,0.1

Type RM Length L Ch R = 1 ,3151    ,85.2,88.9,91.6
XS GIS Cut Line= 2
2182367.21220744 672783.900425842182394.94308688672870.317585026
#Sta/Elev= 24
       0 1807.06     8.1 1807.02     9.7 1806.98    11.3 1806.81    13.9 1806.38
    18.1 1804.88    22.3 1803.69    30.4 1802.89      35 1801.63    39.2  1800.9
    43.4 1800.85    47.6 1801.07    49.5 1801.64    51.8 1802.42      59    1806
    60.2 1806.53    64.4 1808.92    68.6 1811.65    72.8 1814.13    74.9 1815.45
    78.1 1817.35    81.2    1819    85.4 1821.01    90.8 1823.13
#Mann= 3 ,-1,0
       0      .1       0      35    .045       0    49.5      .1       0
Bank Sta=35,49.5
XS Rating Curve= 0 ,0
Exp/Cntr(USF)=0,0
Exp/Cntr=0.3,0.1

Type RM Length L Ch R = 1 ,3062    ,112.9,134.7,154.1
XS GIS Cut Line= 3
2182293.69313171672817.4354428372182298.85236509672876.766626756
2182304.65650265672899.983176985
#Sta/Elev= 22
       0 1806.41     3.8 1806.41     7.8  1806.1    11.8 1805.29    15.8 1804.01
    19.8 1802.89    23.8 1801.43    27.8  1800.5    31.9 1800.32    35.9 1800.29
    39.9 1800.55      421801.427    43.9 1802.22    51.9  1806.5    57.5 1810.14
      60 1811.84    64.1 1814.25    68.2 1816.18    72.3  1817.6    76.5 1818.73
    80.6 1819.77    83.5 1820.14
#Mann= 4 ,-1,0
       0      .1       0    23.8    .045       0      42      .1       0
   79.56     .06       0
Bank Sta=23.8,42
XS Rating Curve= 0 ,0
Exp/Cntr(USF)=0,0
Exp/Cntr=0.3,0.1

Type RM Length L Ch R = 1 ,2928    ,63.7,63.7,64
XS GIS Cut Line= 3
2182286.88158326672816.4757807812182277.20802066672820.345205819
2182112.11255237672844.851564394
#Sta/Elev= 28
       0 1806.39     7.2 1806.47    10.4 1806.42    15.6 1806.22    23.6 1805.77
    31.7 1805.73    43.8 1805.42    51.9 1804.67      60 1804.44    75.4 1803.21
    88.3 1802.37    92.3 1801.91    97.8 1800.73   100.4  1800.3   105.6 1800.34
   108.5 1800.26   110.7 1800.05   112.6 1799.82   116.6 1799.64   124.7 1799.72
   128.3 1800.01   136.8  1801.3     153 1802.51     157 1803.46   161.1 1804.73
   165.1 1805.39   169.2 1805.52   177.3 1805.28
#Mann= 3 ,-1,0
       0      .1       0   110.7    .045       0   128.3      .1       0
Bank Sta=110.7,128.3
XS Rating Curve= 0 ,0
Exp/Cntr(USF)=0,0
Exp/Cntr=0.3,0.1

Type RM Length L Ch R = 1 ,2864    ,180.8,157.1,124.3
XS GIS Cut Line= 4
2182284.94687074672615.910582969 2182290.7510083672719.095250653
2182265.59974555672759.0793093812182108.24312733672781.006051264
#Sta/Elev= 30
       0 1817.55     9.3 1815.84    21.3 1814.69    37.3 1812.32    49.3 1811.39
    61.4 1809.89    81.4 1808.99    95.3 1809.14   115.4 1807.94   124.7 1807.98
   150.2 1806.68   194.8 1805.11   208.6 1804.28   224.7 1801.75   232.8 1801.83
   245.9 1801.16     249 1800.84     253 1799.63     253 1799.62     253 1799.61
     257  1798.7   261.1 1798.45   269.1 1798.72   273.2 1799.55   277.2 1801.42
   281.2 1802.57   285.3 1803.18   289.3 1803.48   297.4 1803.28   309.5 1803.77
#Mann= 3 ,-1,0
       0      .1       0     253    .045       0   273.2      .1       0
Bank Sta=253,273.2
XS Rating Curve= 0 ,0
Exp/Cntr(USF)=0,0
Exp/Cntr=0.3,0.1

Type RM Length L Ch R = 1 ,2707    ,71.8,68.8,65.6
XS GIS Cut Line= 2
 2182044.3976142672686.2051378292182088.25109797672805.512409839
#Sta/Elev= 27
       0  1824.7    11.5 1818.54    14.6 1816.53    20.8 1812.97    24.5 1810.54
    34.1 1804.57    36.4 1803.47    39.5 1802.18    41.5 1801.42    45.8    1800
      50 1798.49    54.3 1797.57    58.2 1797.44    67.1 1797.44    70.7 1797.64
    71.4 1797.71    73.51798.515    75.6 1799.32    79.9 1800.42    84.1 1801.79
    88.4    1803    92.5 1803.48    95.6 1803.57   101.9 1803.51     114 1803.68
   122.5 1803.94   127.1 1804.17
#Mann= 3 ,-1,0
       0      .1       0      50    .045       0    73.5      .1       0
Bank Sta=50,73.5
XS Rating Curve= 0 ,0
Exp/Cntr(USF)=0,0
Exp/Cntr=0.3,0.1

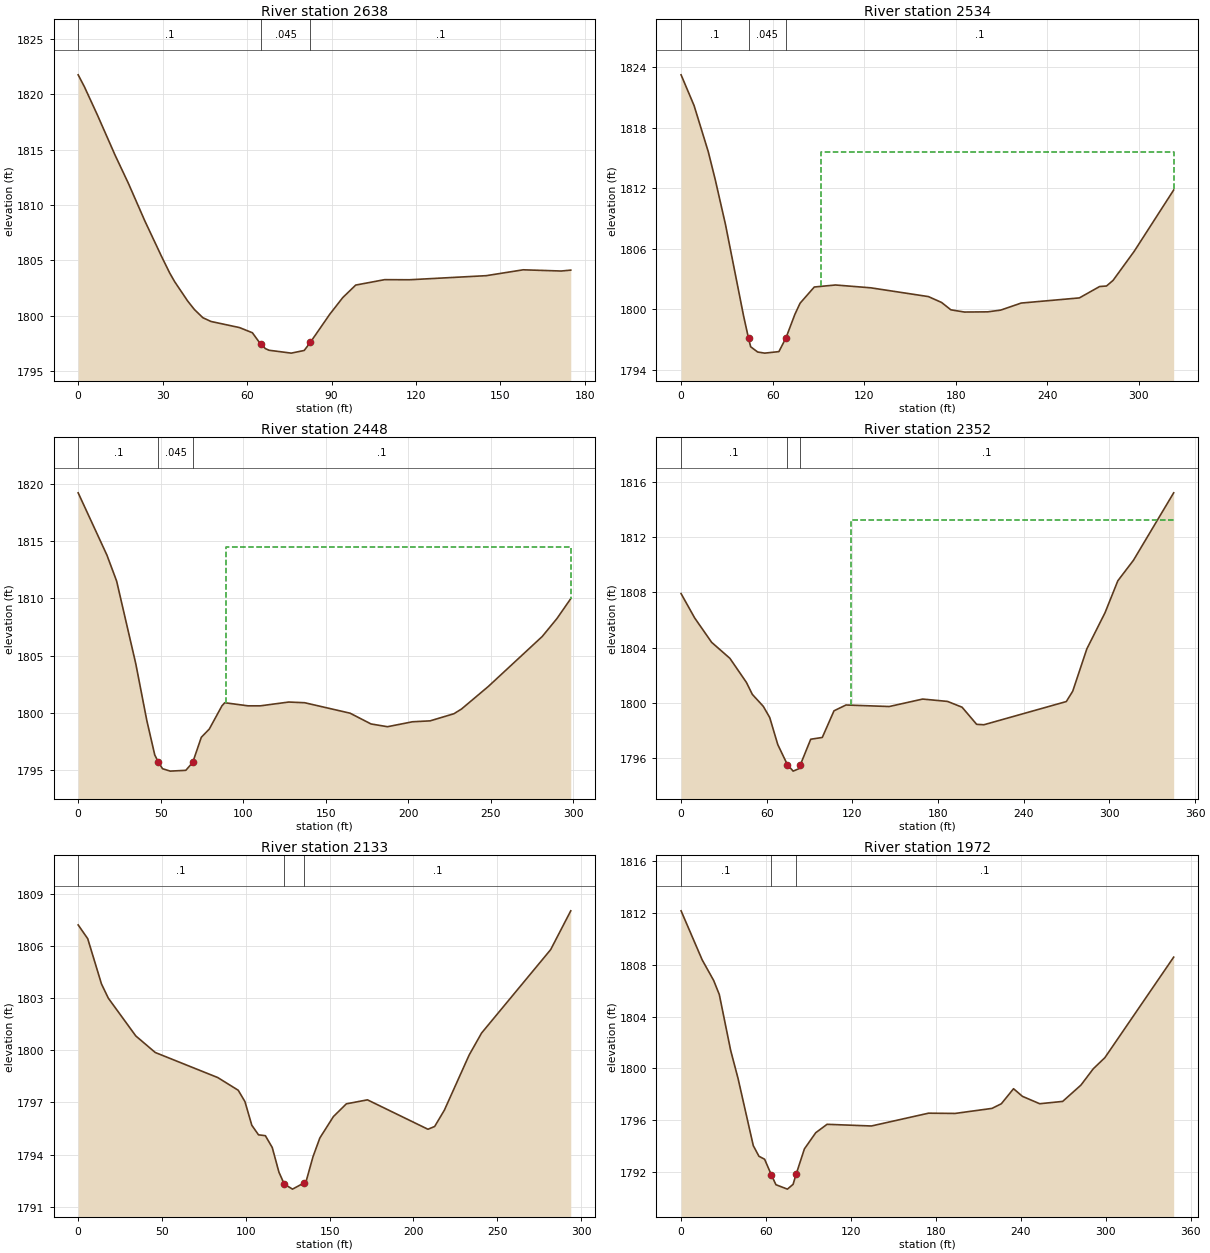
Type RM Length L Ch R = 1 ,2638    ,105.7,103.7,103.3
XS GIS Cut Line= 3
2181973.73024986672719.2915959652182033.06143378672824.410976169
2182072.40058834672861.815418205
#Sta/Elev= 30
       0 1821.75     2.2 1820.68     6.8 1818.14    13.1  1814.5    17.9 1811.91
    23.7 1808.54    29.6 1805.35    32.5 1803.85    34.3 1803.05    38.9 1801.31
    41.3 1800.54    44.3  1799.8    47.2 1799.46    57.3 1798.91    61.9 1798.44
    64.8 1797.42    66.5 1797.01    67.8 1796.86    75.7  1796.6    80.3 1796.84
    82.5 1797.58    89.4 1800.12      94 1801.62    98.6 1802.75   108.9 1803.24
   117.7 1803.23     145  1803.6   158.1 1804.13   171.6 1804.02     175  1804.1
#Mann= 3 ,-1,0
       0      .1       0    64.8    .045       0    82.5      .1       0
Bank Sta=64.8,82.5
XS Rating Curve= 0 ,0
Exp/Cntr(USF)=0,0
Exp/Cntr=0.3,0.1

Type RM Length L Ch R = 1 ,2534    ,86.7,86.4,85.9
XS GIS Cut Line= 4
2181881.50895312672761.8552713852181945.99937042672872.133884973
2182014.35921276672980.4777860422182042.73499638673041.098778307
#Sta/Elev= 30
       0 1823.22     8.5 1820.18    17.8 1815.61    22.4 1812.83    29.1 1808.39
    40.9 1799.38    44.21797.113    45.6 1796.28    50.2 1795.76    54.8 1795.65
    64.1  1795.8    68.7 1797.15    74.6  1799.5      78  1800.6    87.3  1802.2
   101.2  1802.4   124.3 1802.12   162.1 1801.25   170.7 1800.67   176.8 1799.94
   185.7 1799.72     201 1799.74   209.4 1799.91   222.9 1800.61     261 1801.12
   274.3 1802.25   278.8  1802.3   283.1 1802.86   296.9 1805.73   322.8 1811.81
#Mann= 3 ,-1,0
       0      .1       0    44.2    .045       0    68.7      .1       0
#XS Ineff= 2 , 0
                           91.59         1815.55
Permanent Ineff=
       F       F
Bank Sta=44.2,68.7
XS Rating Curve= 0 ,0
Exp/Cntr(USF)=0,0
Exp/Cntr=0.3,0.1

Type RM Length L Ch R = 1 ,2448    ,106.4,96.2,90
XS GIS Cut Line= 4
2181803.47554818672801.8393301132181865.38634879 672901.15457276
2181933.10128696672990.1513486382181963.41178309673052.707053422
#Sta/Elev= 30
       0 1819.19    17.4 1813.77    23.3  1811.5    34.9  1804.3    41.6 1799.34
    46.4 1796.35    48.61795.719    51.1 1795.15    55.8 1794.94    65.2 1795.01
    69.4  1795.7    74.6 1797.89    79.4  1798.6    87.1 1800.63    88.8  1800.9
   102.9 1800.63   110.4 1800.63   127.6 1800.96   137.2  1800.9   164.7 1799.99
   177.4 1799.05   187.4 1798.81   202.5 1799.24   213.2 1799.32   227.6 1799.94
   232.2 1800.35   248.4 1802.31   281.1 1806.67     290 1808.23   298.4 1809.97
#Mann= 3 ,-1,0
       0      .1       0    48.6    .045       0    69.4      .1       0
#XS Ineff= 2 , 0
                           89.37         1814.47
Permanent Ineff=
       F       F
Bank Sta=48.6,69.4
XS Rating Curve= 0 ,0
Exp/Cntr(USF)=0,0
Exp/Cntr=0.3,0.1

Type RM Length L Ch R = 1 ,2352    ,201.4,219.1,233.2
XS GIS Cut Line= 5
2181714.72568577672868.1047328692181725.83236876672905.795798982
2181800.35462875672921.5601232112181909.98833817673008.263906474
2181951.54882932673087.802087814
#Sta/Elev= 30
       0 1807.91     9.5 1806.15    21.4 1804.38    34.2 1803.22    45.8 1801.47
    49.9 1800.61    57.6 1799.74    62.1 1798.93    67.7 1796.98    74.4 1795.53
    78.5 1795.05    82.6 1795.23    83.61795.525    90.8 1797.36    98.9 1797.49
   107.1 1799.42   115.5 1799.84   145.8 1799.73   169.2 1800.27   186.6  1800.1
   196.8 1799.68     207 1798.44   212.1 1798.41   269.8 1800.09   274.3 1800.84
   284.2 1803.91   296.9 1806.52   305.9 1808.84   316.8 1810.32     345 1815.21
#Mann= 3 ,-1,0
       0      .1       0    74.4    .045       0    83.6      .1       0
#XS Ineff= 2 , 0
                          119.02         1813.27
Permanent Ineff=
       F       F
Bank Sta=74.4,83.6
XS Rating Curve= 0 ,0
Exp/Cntr(USF)=0,0
Exp/Cntr=0.3,0.1

Type RM Length L Ch R = 1 ,2133    ,165.6,161,157.9
XS GIS Cut Line= 5
 2181701.3976662672879.5696959452181690.00435914672931.591965903
2181669.94067376673046.9581568562181663.49163203673124.346657619
2181674.95659511673168.773389539
#Sta/Elev= 30
       0  1807.2     5.7 1806.41    13.9 1803.81      18 1802.99    34.4 1800.82
      46 1799.87    83.3 1798.43    95.5  1797.7    99.5 1797.05   103.6 1795.69
   107.6 1795.14   111.7 1795.09   115.8 1794.41   119.8 1792.99     1231792.303
   127.9 1792.02     135 1792.39   136.1  1792.5   140.1 1793.88   144.2 1794.96
   152.3 1796.19     160 1796.92   172.6 1797.15   208.7 1795.46   212.7 1795.62
   218.5 1796.56   233.3 1799.73   240.7 1800.99   281.9 1805.78   293.9 1808.01
#Mann= 3 ,-1,0
       0      .1       0     123    .045       0     135      .1       0
Bank Sta=123,135
XS Rating Curve= 0 ,0
Exp/Cntr(USF)=0,0
Exp/Cntr=0.3,0.1

Type RM Length L Ch R = 1 ,1972    ,158.2,149.8,143.2
XS GIS Cut Line= 4
2181524.47895473672874.2671505222181533.79423723673022.595110319
2181586.81969146673054.8403189712181639.12858549   673181.671473
#Sta/Elev= 30
       0 1812.17    14.9 1808.38      23 1806.79      27  1805.7      35 1801.39
    40.2 1799.23      51 1794.02      55  1793.2      59 1792.97    63.71791.775
      67    1791    75.1 1790.66    79.1 1791.03    81.21791.791    87.1 1793.77
    95.1 1795.02   103.1 1795.67   134.4 1795.54   174.8 1796.53   193.5 1796.51
   219.6  1796.9   226.2 1797.26   234.8 1798.42   241.1 1797.83   253.3 1797.26
   269.5 1797.44   282.4  1798.7   291.1 1799.96   299.3 1800.82   347.9 1808.59
#Mann= 3 ,-1,0
       0      .1       0    63.7    .045       0    81.2      .1       0
Bank Sta=63.7,81.2
XS Rating Curve= 0 ,0
Exp/Cntr(USF)=0,0
Exp/Cntr=0.3,0.1

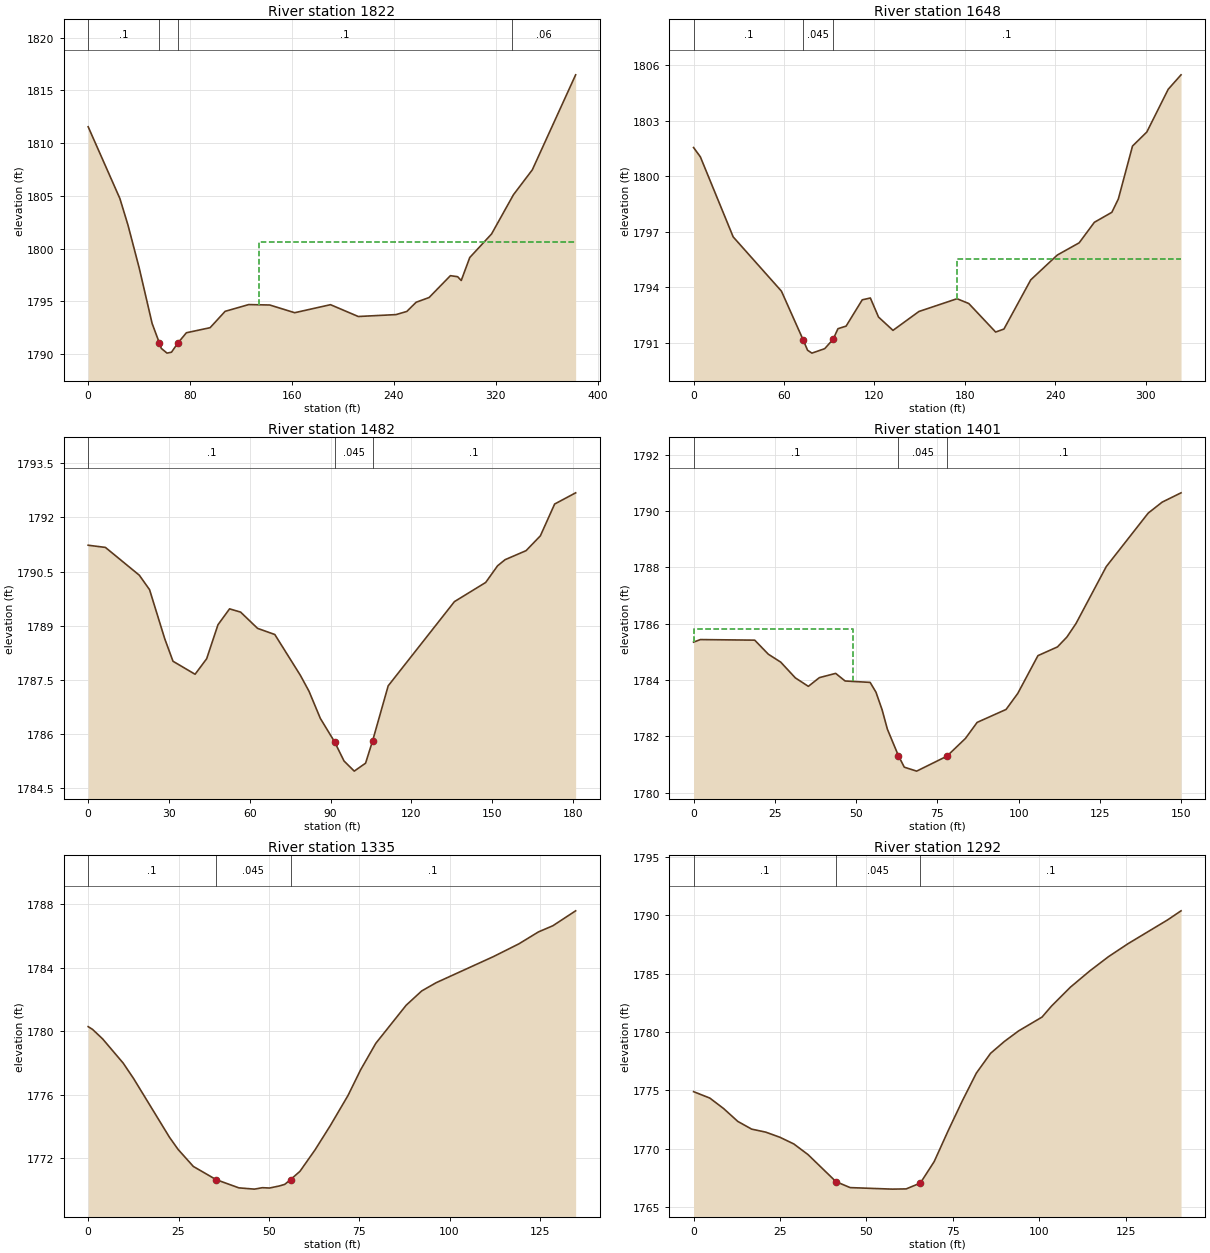
Type RM Length L Ch R = 1 ,1822    ,174.2,173.3,172.4
XS GIS Cut Line= 3
2181345.06250978672925.4396561472181529.93503938673164.770760351
2181568.62928976 673234.99365919
#Sta/Elev= 30
       0 1811.55    24.9 1804.75    31.3 1802.21    40.1 1798.15    50.2 1792.91
    55.81791.093    57.4 1790.55    61.9  1790.1    65.4 1790.19    70.5 1791.07
    77.1 1792.03    95.7 1792.51   107.5 1794.06     126  1794.7   142.5 1794.66
   162.1 1793.93   190.2 1794.69     212 1793.57   241.6 1793.75   250.1 1794.05
   257.4 1794.92   267.6 1795.37   284.3 1797.44     290 1797.34   292.8 1796.98
   299.5 1799.16   316.6 1801.39   333.8 1805.11   348.6 1807.47   382.6 1816.47
#Mann= 4 ,-1,0
       0      .1       0    55.8    .045       0    70.5      .1       0
  332.42     .06       0
#XS Ineff= 2 , 0
                          133.98         1800.66
Permanent Ineff=
       F       F
Bank Sta=55.8,70.5
XS Rating Curve= 0 ,0
Exp/Cntr(USF)=0,0
Exp/Cntr=0.3,0.1

Type RM Length L Ch R = 1 ,1648    ,159.4,166.7,168.9
XS GIS Cut Line= 5
 2181204.2453808673020.9970697292181214.99378369673046.076676457
2181311.72940964673154.2772654832181363.32174348673202.286798363
2181431.39496174673245.280409897
#Sta/Elev= 30
       0 1801.56     4.5 1801.06    26.3 1796.73    58.3  1793.8    72.8 1791.15
    75.6 1790.61    78.5 1790.45      87 1790.69    92.6  1791.2    95.8 1791.77
   101.2 1791.91   111.9 1793.33   117.3 1793.43   122.7  1792.4   132.3 1791.68
   149.5  1792.7   174.8 1793.39   182.6 1793.13   200.4 1791.59   205.9 1791.75
   223.7 1794.41   241.3 1795.75   255.8 1796.41   265.9 1797.52   277.5 1798.06
   281.8 1798.78   291.2 1801.64   300.7  1802.4   314.9 1804.71   323.4 1805.49
#Mann= 3 ,-1,0
       0      .1       0    72.8    .045       0    92.6      .1       0
#XS Ineff= 2 , 0
                          174.72         1795.54
Permanent Ineff=
       F       F
Bank Sta=72.8,92.6
XS Rating Curve= 0 ,0
Exp/Cntr(USF)=0,0
Exp/Cntr=0.3,0.1

Type RM Length L Ch R = 1 ,1482    ,87.7,81,73.9
XS GIS Cut Line= 4
2181137.40771486673099.7178049312181156.82899758673154.554367908
2181181.58161282673231.0970703972181209.38070377673263.085065467
#Sta/Elev= 30
       0 1791.23     6.4 1791.17      19  1790.4    22.8    1790    28.4 1788.65
    31.5 1788.02    39.7 1787.66      44 1788.09    48.2 1789.03    52.5 1789.47
    56.6 1789.38    62.9 1788.93    69.3 1788.76    78.8 1787.63      82 1787.19
    86.2 1786.44    91.5 1785.79      95 1785.26    98.8 1784.98     103  1785.2
   105.61785.815   111.4 1787.34     136 1789.67   147.6  1790.2     152 1790.66
   154.8 1790.83   162.6 1791.08   167.9 1791.49   173.2 1792.37     181 1792.68
#Mann= 3 ,-1,0
       0      .1       0    91.5    .045       0   105.6      .1       0
Bank Sta=91.5,105.6
XS Rating Curve= 0 ,0
Exp/Cntr(USF)=0,0
Exp/Cntr=0.3,0.1

Type RM Length L Ch R = 1 ,1401    ,71.2,65.3,60.8
XS GIS Cut Line= 3
2181042.55946631673181.0759649742181137.78111393673261.051965737
2181161.57807792673270.338585828
#Sta/Elev= 30
       0 1785.35     2.1 1785.44    18.8 1785.42      23 1784.92    26.8 1784.64
    31.3 1784.08    35.3 1783.78    38.7 1784.09    43.7 1784.24    46.6 1783.97
    54.3 1783.92    56.1 1783.57      58 1782.94    59.6 1782.26      631781.316
    64.8 1780.91    68.6 1780.77    77.9  1781.3    83.6 1781.93    87.2  1782.5
    96.1 1782.96    99.7 1783.53   105.9 1784.87   111.9 1785.18   114.8 1785.53
   117.6 1786.01   126.9 1788.03   139.8 1789.93   144.1 1790.32   149.9 1790.65
#Mann= 3 ,-1,0
       0      .1       0      63    .045       0    77.9      .1       0
#XS Ineff= 2 , 0
           49.05 1785.83
Permanent Ineff=
       F       F
Bank Sta=63,77.9
XS Rating Curve= 0 ,0
Exp/Cntr(USF)=0,0
Exp/Cntr=0.3,0.1

Type RM Length L Ch R = 1 ,1335    ,45.7,42.9,41.6
XS GIS Cut Line= 4
2181015.89422524673255.828241935 2181032.1458104673268.597344561
2181101.21504732673291.2334810332181142.42442398673296.457204835
#Sta/Elev= 30
       0  1780.3     1.2 1780.13       4 1779.53     9.7    1778    12.6 1777.02
    22.5 1773.33    24.9 1772.56    29.1 1771.49    35.4 1770.66    41.7 1770.14
      46 1770.06    48.2 1770.15    50.2 1770.13    52.9 1770.26    54.4 1770.36
      56 1770.66    58.6 1771.18    62.8 1772.54      67 1774.06    71.9 1775.96
    75.4 1777.58    79.6 1779.25      88 1781.65    92.3 1782.55    96.3 1783.07
   112.1 1784.71   119.2 1785.52   124.6 1786.27   128.6 1786.66   134.9  1787.6
#Mann= 3 ,-1,0
       0      .1       0    35.4    .045       0      56      .1       0
Bank Sta=35.4,56
XS Rating Curve= 0 ,0
Exp/Cntr(USF)=0,0
Exp/Cntr=0.3,0.1

Type RM Length L Ch R = 1 ,1292    ,37.3,49.6,56.3
XS GIS Cut Line= 3
2180995.57974379673309.8067212162181094.83049601673327.219133887
2181122.69035629673356.239821672
#Sta/Elev= 29
       0  1774.9     4.7 1774.35     8.7 1773.45    12.8 1772.35    16.8 1771.69
    20.9 1771.43      25 1770.99      29 1770.42    33.1 1769.51    41.2 1767.19
    45.3 1766.68    57.5 1766.55    61.5 1766.57    65.6 1767.07    69.6 1768.91
    73.7 1771.59    77.8 1774.15    81.8 1776.49    85.9 1778.18    89.9  1779.2
      94  1780.1   100.8 1781.29   103.5 1782.22     109 1783.85   114.6 1785.24
     120 1786.46   125.7 1787.58   137.1 1789.61     141 1790.39
#Mann= 3 ,-1,0
       0      .1       0    41.2    .045       0    65.6      .1       0
Bank Sta=41.2,65.6
XS Rating Curve= 0 ,0
Exp/Cntr(USF)=0,0
Exp/Cntr=0.3,0.1