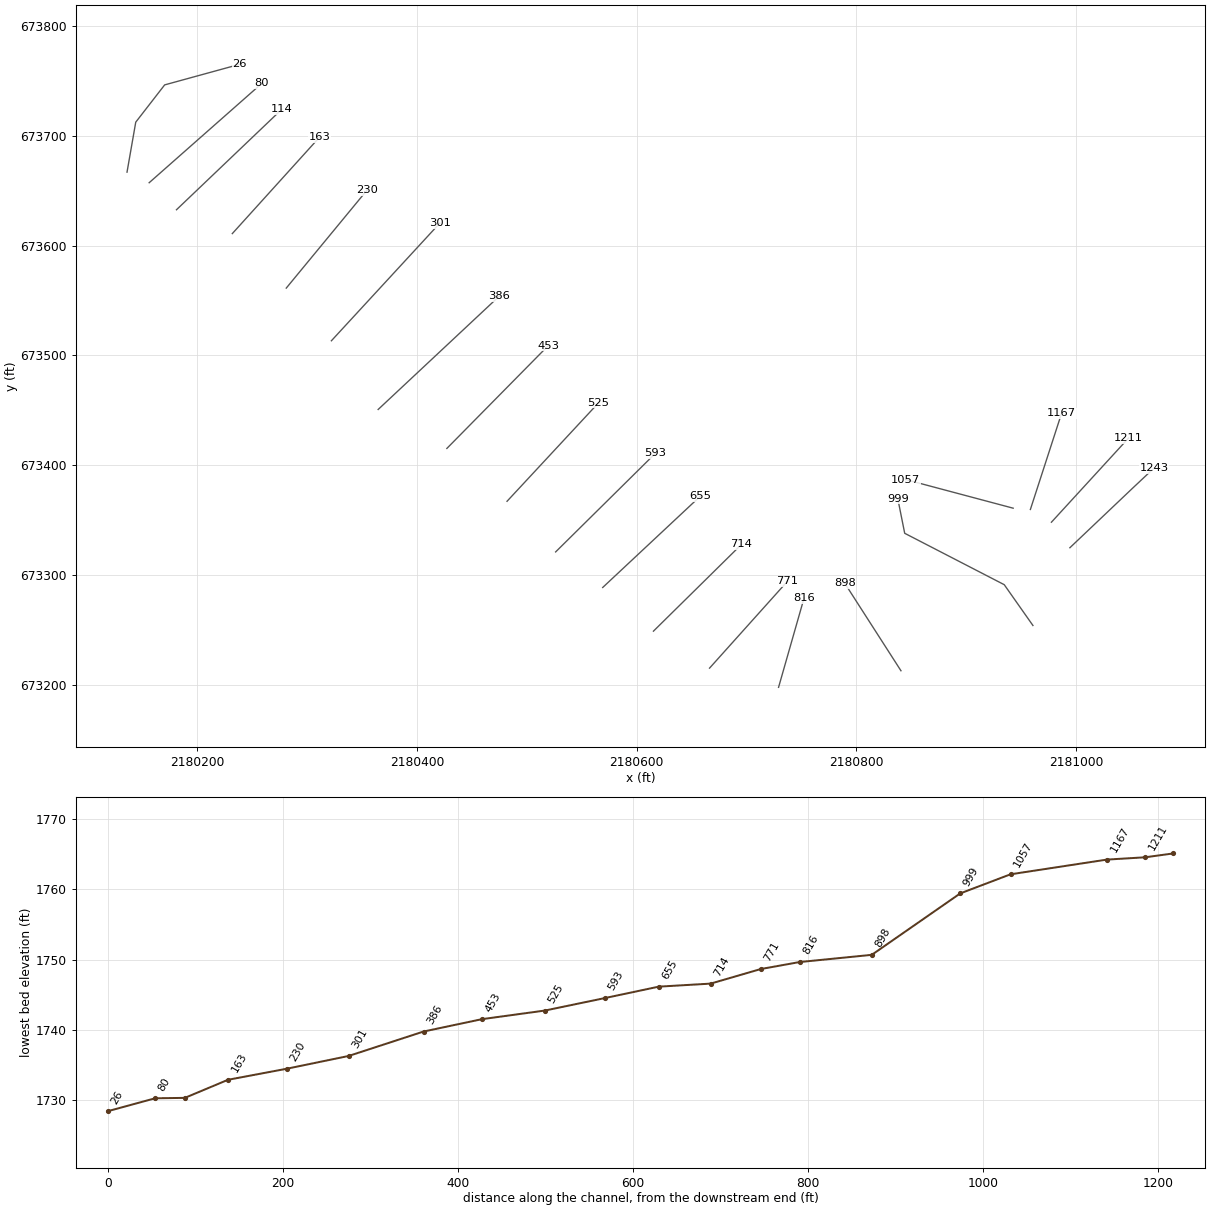
HEC-RAS study QUEENSFK.prj: QUEENSFK

--- QUEENSFK.g01 (geometry) --- (continued)

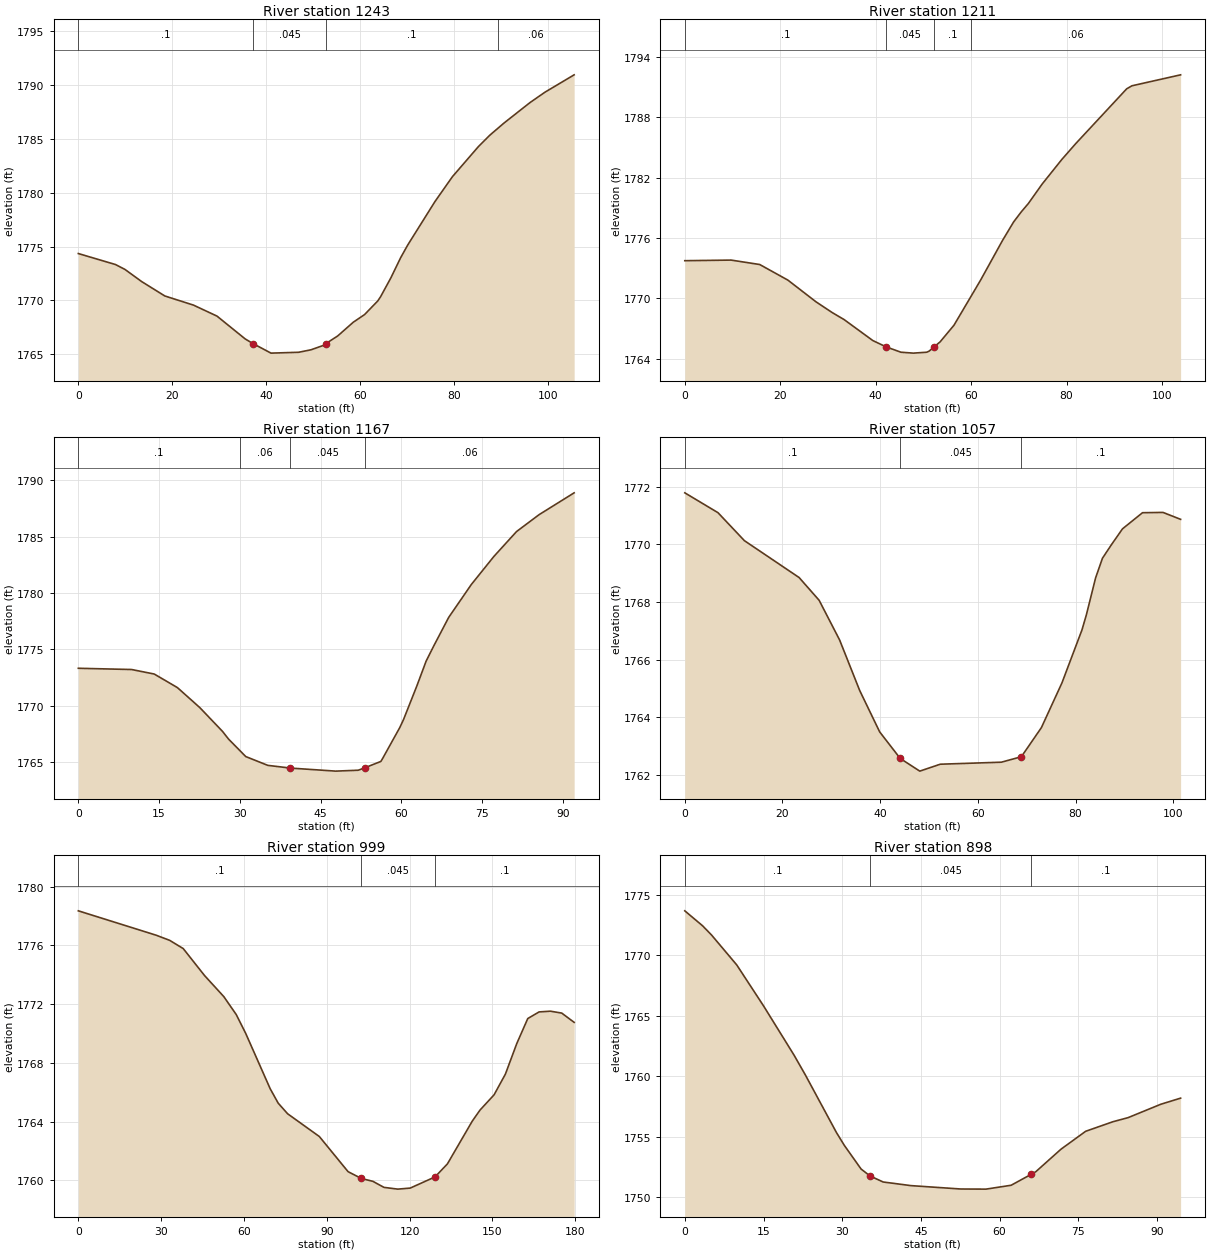
Type RM Length L Ch R = 1 ,1243    ,32.2,32.1,32.6
XS GIS Cut Line= 3
2180994.41891627673324.8974788642181051.87987809673379.456371901
2181071.03353203673397.449198327
#Sta/Elev= 30
       0 1774.35     7.9 1773.33     9.9 1772.88    13.5 1771.74    18.4 1770.41
    24.5 1769.56    29.5 1768.54    35.5 1766.42    37.21765.979      41  1765.1
    46.9 1765.18    49.5 1765.41    52.1 1765.81    52.7 1765.99    55.2  1766.7
    58.5 1767.97    60.9 1768.68    63.7 1769.94    64.3 1770.33    66.5 1772.09
    68.6 1773.98    70.1 1775.15    75.9 1779.19    79.6 1781.49    85.1 1784.27
    87.6 1785.36    90.6 1786.48    96.1 1788.37    99.3 1789.34   105.5 1790.95
#Mann= 4 ,-1,0
       0      .1       0    37.2    .045       0    52.7      .1       0
   89.24     .06       0
Bank Sta=37.2,52.7
XS Rating Curve= 0 ,0
Exp/Cntr(USF)=0,0
Exp/Cntr=0.3,0.1

Type RM Length L Ch R = 1 ,1211    ,38.9,43.9,48
XS GIS Cut Line= 2
2180977.58691736673348.114029093 2181047.8169818673424.728644846
#Sta/Elev= 27
       0 1773.74     9.7  1773.8    15.7 1773.36    21.6 1771.81    27.5 1769.65
    30.9 1768.58    33.4 1767.88    39.4  1765.8    42.2 1765.17    45.3 1764.64
    47.9 1764.55    50.7 1764.64    51.2 1764.75    52.3 1765.19    53.5 1765.67
    56.4 1767.32      62 1771.82    66.6 1775.77    68.9 1777.59    70.5 1778.59
      72 1779.43    74.9 1781.37      79  1783.8    81.9 1785.37    92.6 1790.83
    93.7 1791.13   103.9 1792.22
#Mann= 4 ,-1,0
       0      .1       0    42.2    .045       0    52.3      .1       0
      60     .06       0
Bank Sta=42.2,52.3
XS Rating Curve= 0 ,0
Exp/Cntr(USF)=0,0
Exp/Cntr=0.3,0.1

Type RM Length L Ch R = 1 ,1167    ,83.4,110.1,133.5
XS GIS Cut Line= 2
2180958.43326342673359.7223042072180986.87353745673447.364781318
#Sta/Elev= 27
       0 1773.33     9.9 1773.22    14.1 1772.82    18.4 1771.62    21.6 1770.26
    22.6 1769.83    26.8 1767.73    27.9 1767.06    31.1 1765.51    35.2 1764.73
    39.4 1764.49    47.8 1764.22      52  1764.3    53.3 1764.53    56.2 1765.08
    56.5 1765.32    59.7 1768.07    60.4 1768.78    62.9 1771.79    64.6 1773.96
      66 1775.29    68.8 1777.84      73 1780.75    77.2 1783.24    81.4 1785.44
    85.6 1786.94    92.1 1788.87
#Mann= 4 ,-1,0
       0      .1       0      30     .06       0    39.4    .045       0
    53.3     .06       0
Bank Sta=39.4,53.3
XS Rating Curve= 0 ,0
Exp/Cntr(USF)=0,0
Exp/Cntr=0.3,0.1

Type RM Length L Ch R = 1 ,1057    ,58.8,57.5,50.7
XS GIS Cut Line= 2
2180942.76209202673360.883131718 2180844.6721673673387.001750725
#Sta/Elev= 24
       0 1771.79     6.8  1771.1    12.2 1770.13    23.4 1768.85    27.5 1768.06
    31.7 1766.68    35.8 1764.93    39.9 1763.49    44.1 1762.57    48.1 1762.13
    52.3 1762.37    64.8 1762.44    68.9 1762.63      73 1763.64    77.2 1765.19
    81.3 1767.03    82.2 1767.55    84.1 1768.84    85.5 1769.52    87.3 1769.98
    89.6 1770.54    93.7  1771.1    97.9 1771.11   101.5 1770.87
#Mann= 3 ,-1,0
       0      .1       0    44.1    .045       0    68.9      .1       0
Bank Sta=44.1,68.9
XS Rating Curve= 0 ,0
Exp/Cntr(USF)=0,0
Exp/Cntr=0.3,0.1

Type RM Length L Ch R = 1 ,999     ,106.3,101,85
XS GIS Cut Line= 4
2180960.75491844673254.0870006682180934.63629944673291.233481033
2180844.01521091673338.0315572692180837.70720223673369.589338054
#Sta/Elev= 30
       0 1778.35    28.2 1776.69    33.1 1776.34      38 1775.78    45.7 1773.95
    52.7 1772.51    57.2 1771.29    60.6 1770.02    69.5 1766.24    72.4 1765.26
    75.8 1764.54    87.3 1762.99    97.7  1760.6   102.51760.136   106.7 1759.94
   110.7 1759.53   115.7 1759.41   120.2 1759.48   129.2 1760.24   133.7 1761.13
   142.7 1764.04   145.5 1764.79   150.6 1765.83   154.7 1767.24   158.8 1769.31
   162.8 1771.02   166.9 1771.47     171 1771.52   175.1 1771.39   179.6 1770.76
#Mann= 3 ,-1,0
       0      .1       0   102.5    .045       0   129.2      .1       0
Bank Sta=102.5,129.2
XS Rating Curve= 0 ,0
Exp/Cntr(USF)=0,0
Exp/Cntr=0.3,0.1

Type RM Length L Ch R = 1 ,898     ,96.8,82.3,67.2
XS GIS Cut Line= 2
2180840.60927101673212.8776240132180789.53286051673292.394308545
#Sta/Elev= 24
       0 1773.68     3.4 1772.44     5.1 1771.68     9.9 1769.21      15 1765.83
    20.8 1761.77      23  1760.1    28.9 1755.36    30.4  1754.3    33.6 1752.34
    35.3 1751.77    37.8 1751.27    43.1 1750.97    52.6 1750.69    57.4 1750.68
    62.2    1751      66  1751.9    66.9 1752.12    71.7 1753.98    76.4 1755.46
    81.6 1756.25    84.5 1756.59    90.7 1757.69    94.5  1758.2
#Mann= 3 ,-1,0
       0      .1       0    35.3    .045       0      66      .1       0
Bank Sta=35.3,66
XS Rating Curve= 0 ,0
Exp/Cntr(USF)=0,0
Exp/Cntr=0.3,0.1

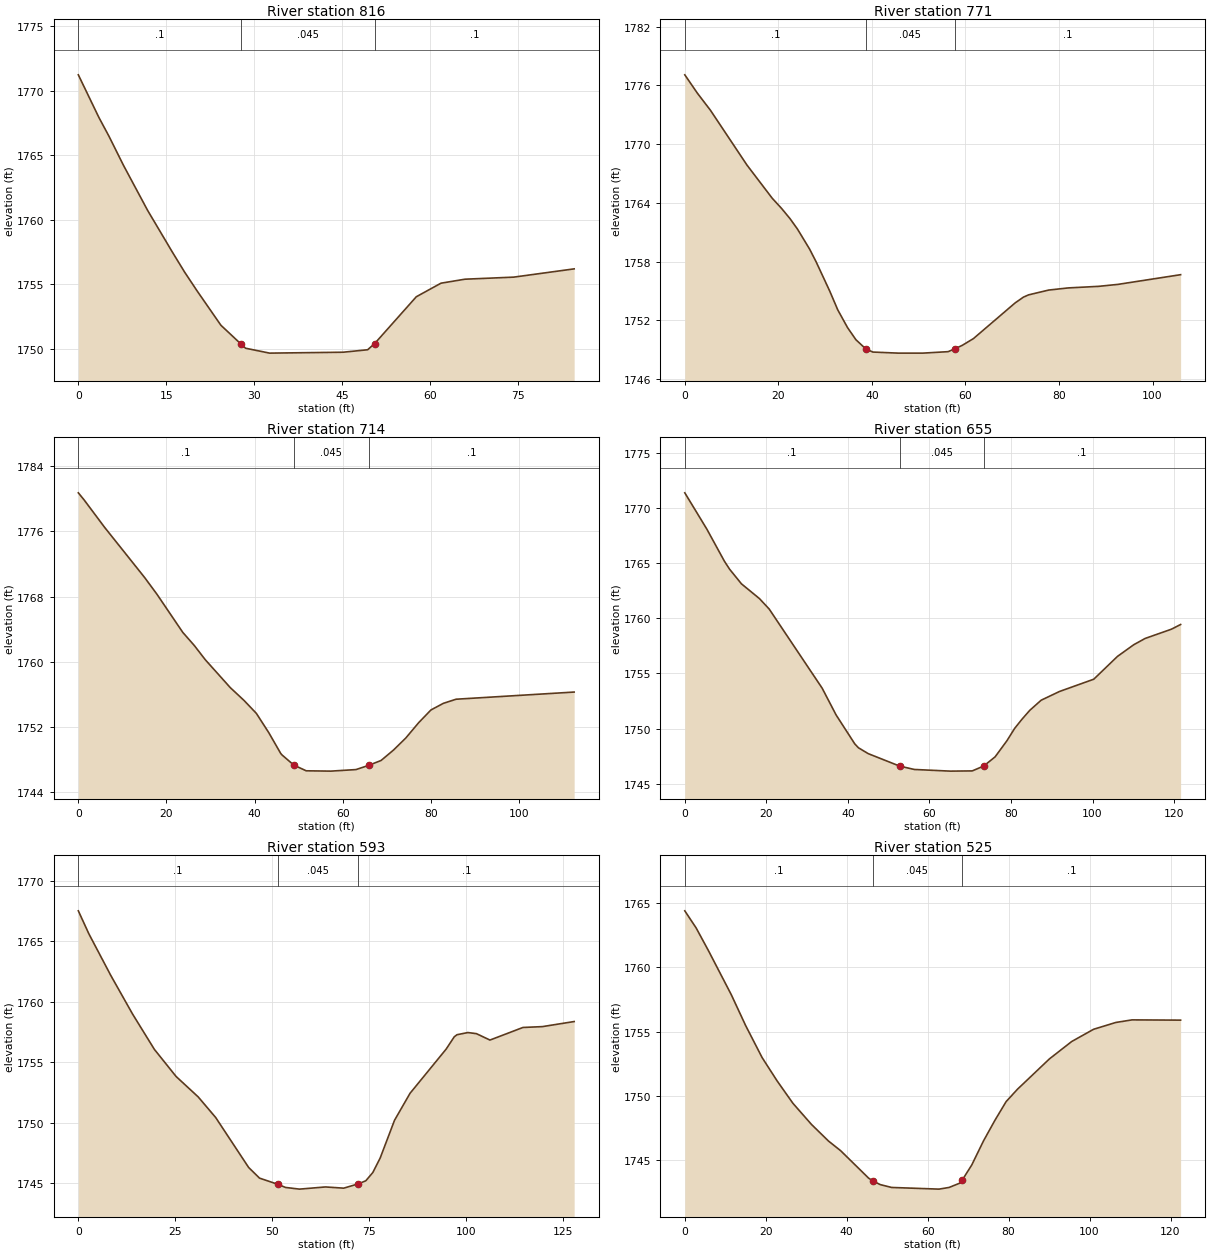
Type RM Length L Ch R = 1 ,816     ,51.4,44.6,38
XS GIS Cut Line= 2
2180729.16982992673197.7868663652180752.38638015673279.044792164
#Sta/Elev= 20
       0 1771.23     3.5 1767.93     5.2 1766.49     7.7 1764.21    11.8 1760.73
      16 1757.51    18.1 1755.95    20.2 1754.51    24.3 1751.82    27.8 1750.33
    28.5 1750.04    32.6 1749.66    45.1 1749.73    49.3 1749.92    50.5  1750.4
    57.6 1754.03    61.8 1755.08    65.9 1755.39    74.2 1755.55    84.5 1756.19
#Mann= 3 ,-1,0
       0      .1       0    27.8    .045       0    50.5      .1       0
Bank Sta=27.8,50.5
XS Rating Curve= 0 ,0
Exp/Cntr(USF)=0,0
Exp/Cntr=0.3,0.1

Type RM Length L Ch R = 1 ,771     ,58,57.2,56.4
XS GIS Cut Line= 2
2180666.34128729673215.2688789912180737.15176549673294.205149766
#Sta/Elev= 30
       0 1777.08     2.7  1775.2     5.5 1773.45    13.3 1767.86    18.7 1764.47
    20.7 1763.43    22.5 1762.39    24.1 1761.32    26.7 1759.27    28.1 1757.96
      31 1754.98    32.7 1753.08    34.8 1751.26    36.6 1750.02    38.7 1749.09
    40.2 1748.77    45.6 1748.66    50.9 1748.66    56.3 1748.81    57.71749.096
    59.3 1749.45    61.7 1750.14    70.6 1753.78    72.4 1754.38    73.5 1754.61
    77.8  1755.1      82 1755.32    88.5 1755.48    92.6 1755.68     106 1756.67
#Mann= 3 ,-1,0
       0      .1       0    38.7    .045       0    57.7      .1       0
Bank Sta=38.7,57.7
XS Rating Curve= 0 ,0
Exp/Cntr(USF)=0,0
Exp/Cntr=0.3,0.1

Type RM Length L Ch R = 1 ,714     ,59.6,59.2,58.8
XS GIS Cut Line= 2
2180615.26487679673248.9328768212180695.36197508673327.869147597
#Sta/Elev= 27
       0 1780.73     1.3 1779.87       6 1776.47      15 1770.37    17.8 1768.32
    23.7 1763.61    26.3 1762.01    28.8 1760.26    34.5 1756.82    37.6 1755.26
    40.4 1753.67    43.2 1751.32    45.9 1748.78    46.2 1748.58    48.9 1747.33
    51.7 1746.63    57.3 1746.59      63 1746.78    65.9  1747.3    68.7  1747.9
    71.5 1749.17    74.3 1750.65    77.2 1752.52      80 1754.09    82.8  1754.9
    85.7 1755.41   112.5 1756.29
#Mann= 3 ,-1,0
       0      .1       0    48.9    .045       0    65.9      .1       0
Bank Sta=48.9,65.9
XS Rating Curve= 0 ,0
Exp/Cntr(USF)=0,0
Exp/Cntr=0.3,0.1

Type RM Length L Ch R = 1 ,655     ,57.6,61.8,57.7
XS GIS Cut Line= 2
2180569.06394184673288.6912190872180657.86724646673371.748427529
#Sta/Elev= 30
       0 1771.35     5.4 1768.07     9.7 1765.17      11 1764.43    13.9 1763.11
    18.3 1761.78    20.7 1760.83    33.7 1753.66    37.1 1751.25    41.7 1748.62
    42.6 1748.27      45 1747.74    52.71746.614    56.3 1746.31    65.1 1746.16
    70.5 1746.18    73.3 1746.62    76.1 1747.45      79 1748.91    80.9 1750.03
    82.7 1750.86    84.6 1751.66    87.4 1752.58    91.9 1753.37   100.3 1754.48
   106.1 1756.54   110.1  1757.6   112.9 1758.17   119.3    1759   121.6 1759.43
#Mann= 3 ,-1,0
       0      .1       0    52.7    .045       0    73.3      .1       0
Bank Sta=52.7,73.3
XS Rating Curve= 0 ,0
Exp/Cntr(USF)=0,0
Exp/Cntr=0.3,0.1

Type RM Length L Ch R = 1 ,593     ,67.1,68.4,67.7
XS GIS Cut Line= 2
2180526.22940667673321.0783066562180617.12220081673410.926356039
#Sta/Elev= 30
       0 1767.53     2.7 1765.64     8.4 1762.17      14 1758.99    19.6 1756.08
    25.2 1753.84    30.9 1752.15    35.4 1750.45    43.9 1746.32    46.7 1745.44
    51.4 1744.93    53.4 1744.67      57 1744.53    63.7 1744.71    68.4 1744.61
    72.2 1744.97    74.1 1745.22    75.9  1745.9    77.8  1747.1    81.5 1750.22
    85.5 1752.45    94.8  1756.1    96.9 1757.12    97.6 1757.29   100.4 1757.47
   102.6 1757.38   106.1 1756.85   114.6 1757.89   119.6 1757.96   127.8 1758.38
#Mann= 3 ,-1,0
       0      .1       0    51.4    .045       0    72.2      .1       0
Bank Sta=51.4,72.2
XS Rating Curve= 0 ,0
Exp/Cntr(USF)=0,0
Exp/Cntr=0.3,0.1

Type RM Length L Ch R = 1 ,525     ,71.9,71.7,71.3
XS GIS Cut Line= 2
2180481.96621528673367.1636317882180565.32117598673456.865416905
#Sta/Elev= 30
       0  1764.4     2.8 1763.07     5.8 1761.33    11.5 1757.87      15  1755.5
    19.1 1752.99    22.8 1751.18    26.7 1749.44    31.3 1747.79    35.5  1746.5
    38.5 1745.75    45.4 1743.62    46.4 1743.41    48.3 1743.11    51.1 1742.89
    62.8 1742.76    65.3 1742.89    67.9 1743.22    68.5 1743.44    70.9 1744.64
    73.8 1746.51    76.6  1748.1    79.4 1749.57    82.2 1750.53    90.1 1752.89
    95.6 1754.24     101 1755.19   106.5 1755.72   110.5 1755.92   122.5  1755.9
#Mann= 3 ,-1,0
       0      .1       0    46.4    .045       0    68.5      .1       0
Bank Sta=46.4,68.5
XS Rating Curve= 0 ,0
Exp/Cntr(USF)=0,0
Exp/Cntr=0.3,0.1

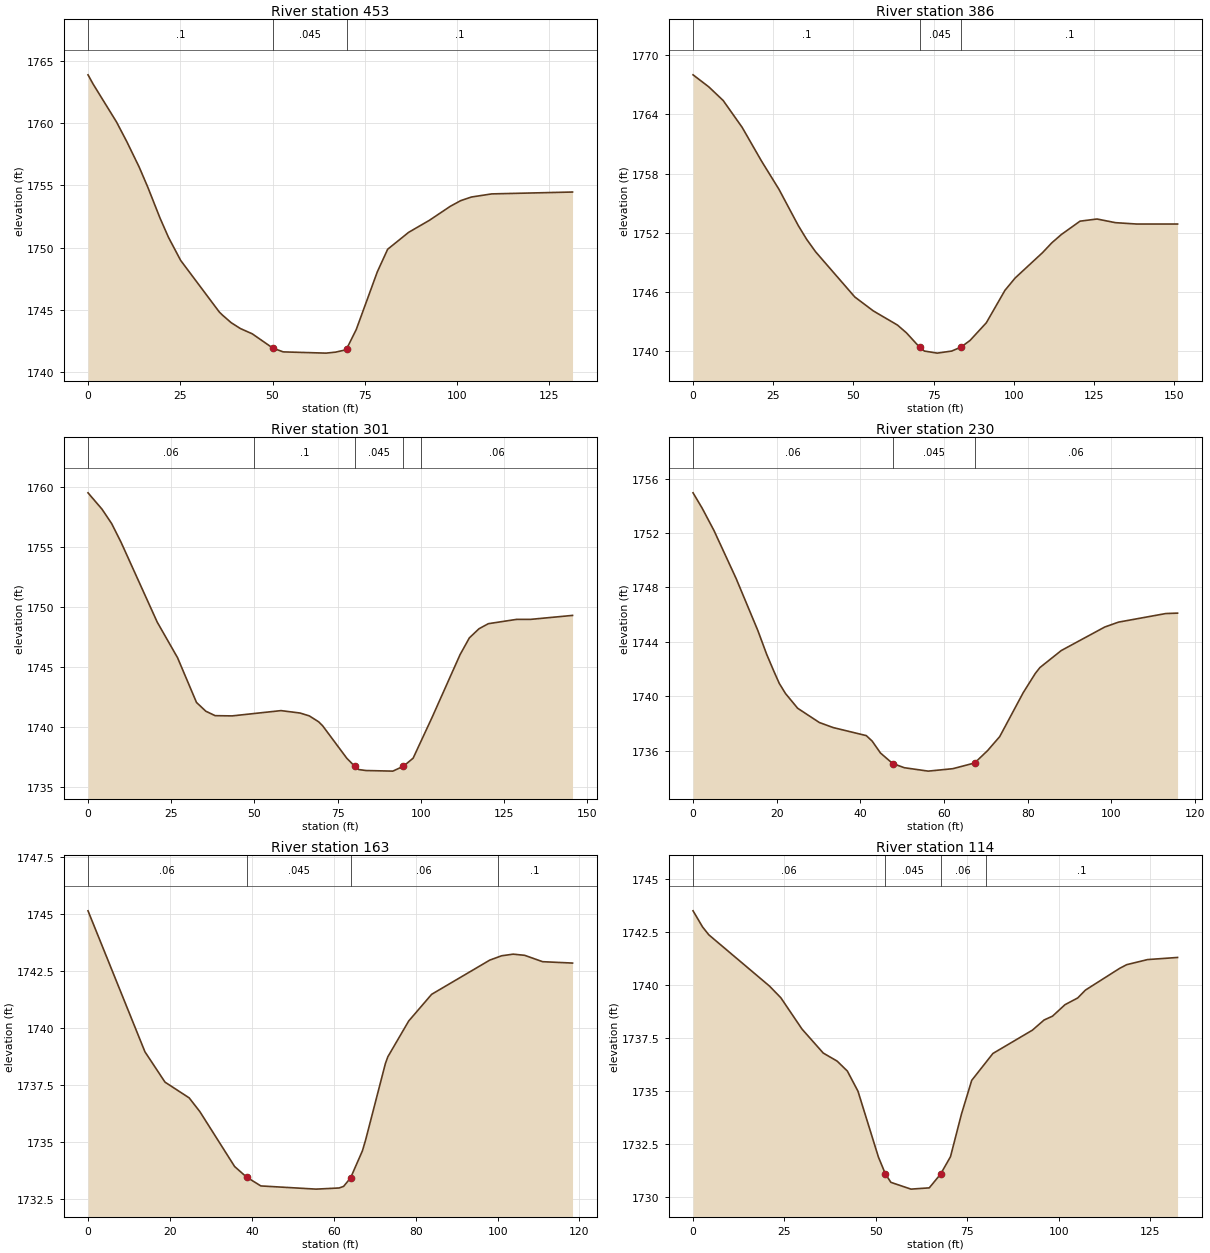
Type RM Length L Ch R = 1 ,453     ,66.8,66.8,66.2
XS GIS Cut Line= 2
2180427.18903105 673415.284835032180519.41032779673508.795940116
#Sta/Elev= 30
       0 1763.86     1.4 1763.11     7.7 1760.09    10.5 1758.51    13.9 1756.44
    16.2 1754.85    19.5 1752.38    21.8 1750.83    25.1 1748.98    35.6 1744.83
    36.4  1744.6    38.8 1743.98    41.3 1743.51    44.5 1743.09    50.1 1741.94
    52.9 1741.64    64.5 1741.54    67.1 1741.62    69.8  1741.8    70.1 1741.89
    72.7 1743.44    78.4 1748.06    81.2 1749.87    86.9 1751.23    92.5 1752.19
    98.2 1753.32     101 1753.77   103.9 1754.06   109.4 1754.31   131.3 1754.46
#Mann= 3 ,-1,0
       0      .1       0    50.1    .045       0    70.1      .1       0
Bank Sta=50.1,70.1
XS Rating Curve= 0 ,0
Exp/Cntr(USF)=0,0
Exp/Cntr=0.3,0.1

Type RM Length L Ch R = 1 ,386     ,85,85.5,87
XS GIS Cut Line= 2
2180364.63332627673450.7545645462180474.91193986673553.939232227
#Sta/Elev= 30
       0 1768.02     4.9  1766.8     9.4 1765.41    15.3 1762.69    21.3 1759.29
    26.8 1756.39    32.8 1752.72    35.4 1751.33    38.2 1750.06    50.4 1745.48
    56.2 1744.06    63.7 1742.63    66.5 1741.84    70.6 1740.38    72.1 1739.99
    76.1 1739.78    80.6 1739.99    83.5 1740.39    86.3 1741.06    91.4 1742.86
    97.2 1746.15   100.4 1747.41   108.9 1749.97   111.8 1750.97   114.8 1751.82
   120.6 1753.17   125.9 1753.39   131.6 1753.02   138.2 1752.88     151 1752.88
#Mann= 3 ,-1,0
       0      .1       0    70.6    .045       0    83.5      .1       0
Bank Sta=70.6,83.5
XS Rating Curve= 0 ,0
Exp/Cntr(USF)=0,0
Exp/Cntr=0.3,0.1

Type RM Length L Ch R = 1 ,301     ,70.9,70.4,70.8
XS GIS Cut Line= 2
2180322.06965085673513.3102693272180420.73998932673620.364362046
#Sta/Elev= 30
       0 1759.49     4.2 1758.13     7.1 1756.93     9.9 1755.39    20.8 1748.72
    26.9 1745.76    32.6 1742.03    35.4  1741.3    38.2 1740.93    43.3 1740.91
      58 1741.35    63.7 1741.15    66.5 1740.91    69.3 1740.42    70.5 1740.09
    77.8 1737.37    80.2  1736.7    81.4 1736.44    83.5 1736.36    91.6 1736.31
    94.8 1736.72    97.7 1737.39   103.4 1740.79   111.8 1746.01   114.6 1747.41
   117.5 1748.17   120.3 1748.59   128.8 1748.95     133 1748.95   145.6 1749.28
#Mann= 5 ,-1,0
       0     .06       0      50      .1       0    80.2    .045       0
    94.8      .1       0     100     .06       0
Bank Sta=80.2,94.8
XS Rating Curve= 0 ,0
Exp/Cntr(USF)=0,0
Exp/Cntr=0.3,0.1

Type RM Length L Ch R = 1 ,230     ,68.1,67.5,66.6
XS GIS Cut Line= 2
2180280.97011039673561.2552980282180354.62461599673650.580975031
#Sta/Elev= 30
       0 1754.95     2.2 1753.81       5 1752.18    10.3 1748.65    15.5 1744.82
    17.6 1743.08    19.3 1741.85    20.6 1740.95    22.1  1740.2      25 1739.12
    30.2 1738.07    33.5  1737.7    41.4 1737.11    42.8 1736.71    44.8 1735.83
    47.7 1735.06    50.5 1734.75    56.2  1734.5    62.1 1734.68    67.3  1735.1
    70.4 1736.01    73.3 1737.04    78.9 1740.26    81.8 1741.68    82.9 1742.11
      88 1743.36    98.4 1745.09   101.7 1745.45     113 1746.08   115.8 1746.11
#Mann= 3 ,-1,0
       0     .06       0    47.7    .045       0    67.3     .06       0
Bank Sta=47.7,67.3
XS Rating Curve= 0 ,0
Exp/Cntr(USF)=0,0
Exp/Cntr=0.3,0.1

Type RM Length L Ch R = 1 ,163     ,49.1,49.3,49.3
XS GIS Cut Line= 2
2180231.86710666673610.8806741412180311.26770844673698.639234004
#Sta/Elev= 24
       0 1745.12    13.9 1738.94    18.8 1737.61    24.7 1736.92    27.3 1736.32
    35.8 1733.91    38.7 1733.45    42.2 1733.06    55.7 1732.92    61.3 1732.97
    62.4 1733.04    64.1 1733.41      67  1734.6    67.8 1735.09    72.6 1738.42
    73.2 1738.72    78.3 1740.29    83.9 1741.46    98.1 1742.96     101 1743.15
   103.8 1743.22   106.6 1743.17     111 1742.89   118.3 1742.83
#Mann= 4 ,-1,0
       0     .06       0    38.7    .045       0    64.1     .06       0
     100      .1       0
Bank Sta=38.7,64.1
XS Rating Curve= 0 ,0
Exp/Cntr(USF)=0,0
Exp/Cntr=0.3,0.1

Type RM Length L Ch R = 1 ,114     ,33.8,34,33.8
XS GIS Cut Line= 2
2180181.03487413673632.5944806982180276.93199568 673724.07755563
#Sta/Elev= 30
       0 1743.48     2.6 1742.72     4.3 1742.35    20.9 1739.93      24 1739.38
    29.8  1737.9    35.6 1736.77    39.4 1736.39    42.2 1735.92    45.1 1734.97
    50.7 1731.86    52.61731.067    54.1 1730.67    59.6 1730.35    64.6 1730.41
    67.7 1731.06    70.4 1731.88    73.4 1733.89    76.2 1735.48      82 1736.75
    92.8 1737.85      96 1738.33    98.3 1738.51   101.7 1739.05   105.2 1739.37
   107.3 1739.74   116.7 1740.77   118.6 1740.94   124.3 1741.18   132.5 1741.28
#Mann= 4 ,-1,0
       0     .06       0    52.6    .045       0    67.7     .06       0
      80      .1       0
Bank Sta=52.6,67.7
XS Rating Curve= 0 ,0
Exp/Cntr(USF)=0,0
Exp/Cntr=0.3,0.1

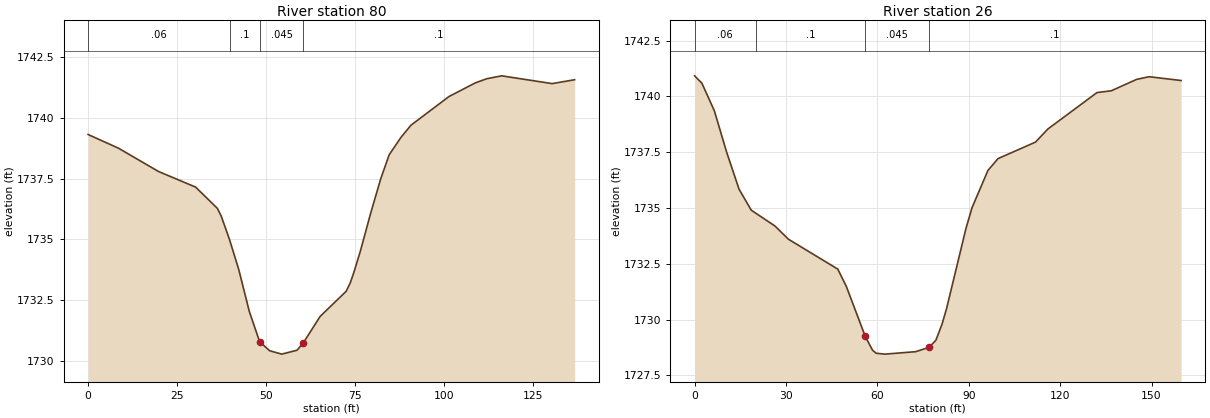
Type RM Length L Ch R = 1 ,80      ,54.2,54.2,54.2
XS GIS Cut Line= 2
2180156.15950139673657.1929960782180258.64896237673747.584312736
#Sta/Elev= 30
       0 1739.31     8.5 1738.75    19.8 1737.79    30.2 1737.15    36.3 1736.28
    37.4 1735.96    39.7 1735.01    42.3 1733.78    45.3 1732.04    48.2  1730.8
      51 1730.43    54.4 1730.29    58.7 1730.45    60.5 1730.76    65.2 1731.84
    72.5 1732.87    73.7 1733.23    74.7 1733.66    76.5 1734.52    79.4 1736.08
    82.2 1737.48    84.6 1738.48    87.9 1739.19    90.7 1739.69   101.4 1740.87
   108.8 1741.43     112  1741.6   116.2 1741.72   130.4  1741.4   136.7 1741.56
#Mann= 4 ,-1,0
       0     .06       0      40      .1       0    48.2    .045       0
    60.5      .1       0
Bank Sta=48.2,60.5
XS Rating Curve= 0 ,0
Exp/Cntr(USF)=0,0
Exp/Cntr=0.3,0.1

Type RM Length L Ch R = 1 ,26      ,,,
XS GIS Cut Line= 4
2180135.99632036673666.8158851472180143.94585972 673712.33447662
 2180170.2617125673746.2572555992180238.32178328673764.936408965
#Sta/Elev= 30
       0 1740.92     2.4 1740.59     6.5 1739.35    10.5 1737.51    14.6 1735.84
    18.6  1734.9    26.4 1734.19    30.8  1733.6      47 1732.26    49.8 1731.49
56.026491729.244    58.4 1728.63    59.6 1728.49    62.5 1728.45    72.6 1728.56
76.990231728.755    79.2 1729.07    81.2 1729.78    82.7 1730.48    89.1 1734.09
    91.1 1735.02    96.3 1736.68    99.6 1737.21   111.9 1737.95     116 1738.54
   132.1 1740.17   136.8 1740.25   145.1 1740.76   149.2 1740.88   159.7 1740.71
#Mann= 4 ,-1,0
       0     .06       0      20      .1       056.02649    .045       0
76.99023      .1       0
Bank Sta=56.02649,76.99023
XS Rating Curve= 0 ,0
Exp/Cntr(USF)=0,0
Exp/Cntr=0.3,0.1
LCMann Table=0

Chan Stop Cuts=-1
Use User Specified Reach Order=0
Composite Channel Slope=5